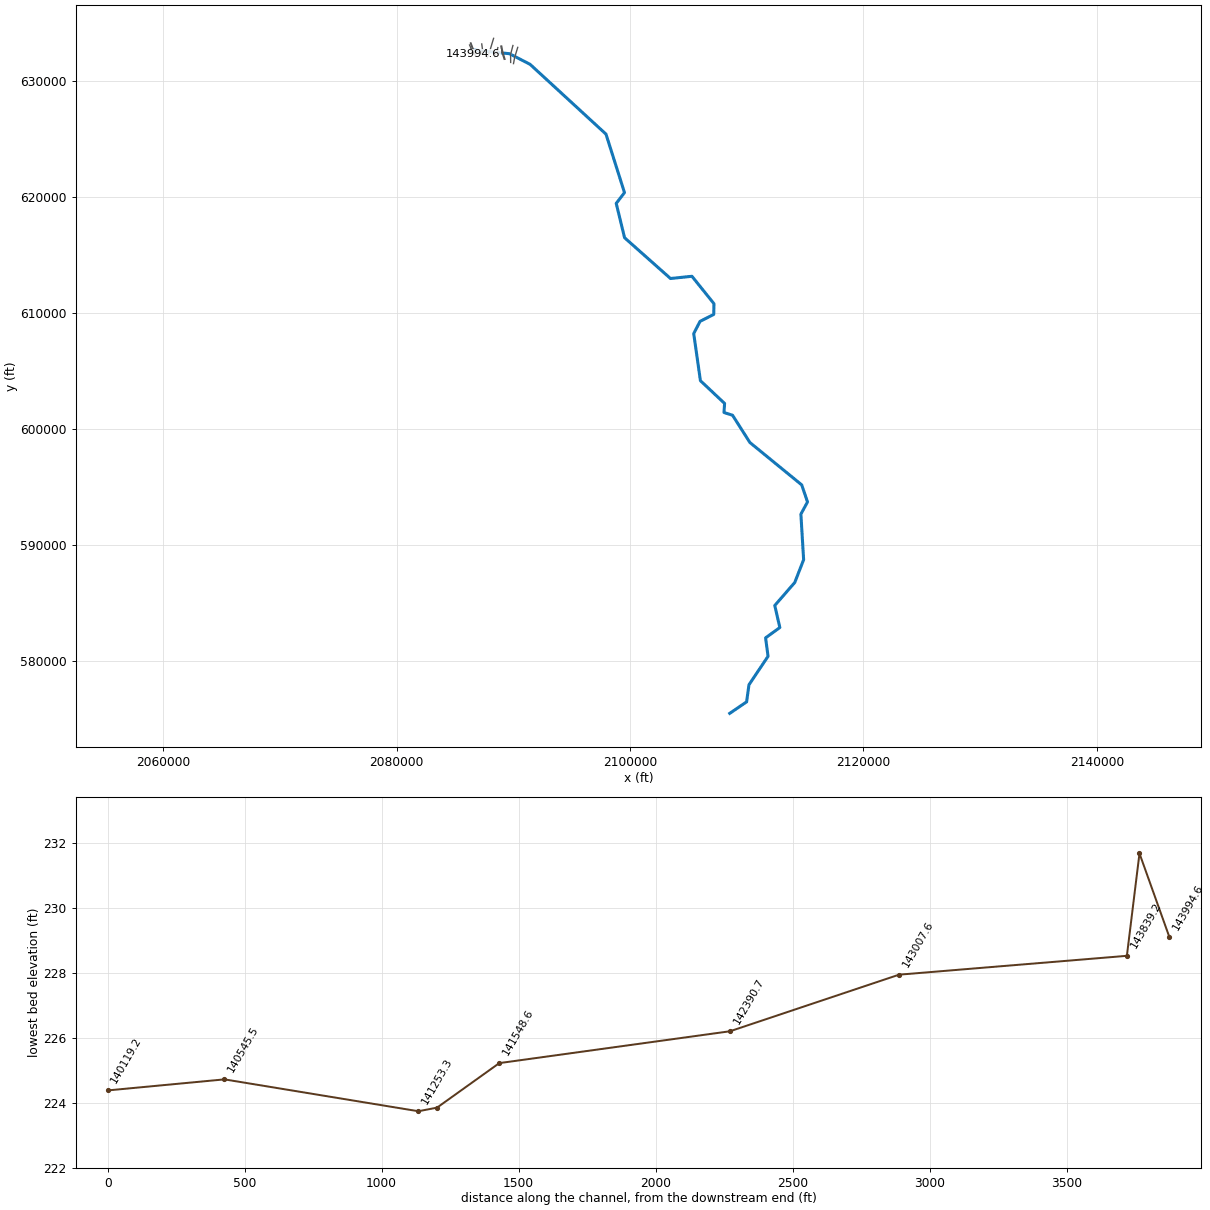
--- B4544BLACKRIVER.prj (project) ---

Proj Title=B4544 BLACK RIVER SR1722
Current Plan=p02
Default Exp/Contr=0.3,0.1
English Units
Geom File=g01
Geom File=g02
Geom File=g03
Flow File=f01
Plan File=p01
Plan File=p02
Plan File=p03
Y Axis Title=Elevation
X Axis Title(PF)=Main Channel Distance
X Axis Title(XS)=Station
BEGIN DESCRIPTION:
####(Watershed Name)####
BLACK RIVER
HCFCD Unit X###-##-##
(Flood Hazard, Floodway) Model
10, 2, 1, 0.2% Event
Filename:  N:\NC_flood\60273\Approximates\Eng\Mingo_Swamp\Eng\Black_River\Black River.prj
Prepared by:  ________     Date: ________
Reviewed by:  ________     Date: ________
STATUS (Draft RAS, SVSQ, FINAL)
END DESCRIPTION:
DSS Export Rating Curves= 0
DSS Export Rating Curve Sorted= 0
DSS Export Volume Flow Curves= 0
DXF Filename=..\BLACK_RIVER_US.
DXF OffsetX= 0
DXF OffsetY= 0
DXF ScaleX= 1
DXF ScaleY= 10

--- B4544BLACKRIVER.p02 (plan) ---

Plan Title=Corrected Effective
Program Version=4.10
Short Identifier=Corrected
Geom File=g02
Flow File=f01
Subcritical Flow
K Sum by GR= 0
Std Step Tol= 0.01
Critical Tol= 0.01
Num of Std Step Trials= 20
Max Error Tol= 0.3
Flow Tol Ratio= 0.001
Split Flow NTrial= 30
Split Flow Tol= 0.02
Split Flow Ratio= 0.02
Log Output Level= 0
Friction Slope Method= 1
Unsteady Friction Slope Method= 2
Unsteady Bridges Friction Slope Method= 1
Parabolic Critical Depth
Global Vel Dist= 0 , 0 , 0
Global Log Level= 0
CheckData=True
Encroach Param=-1 ,10,10, 2
Encroach River=Black River
Encroach Reach=Reach - 1
Encroach Node=143994.6
       1 4941.56 5136.88
Encroach Node=143885.2
       1  4959.3  5040.4
Encroach Node=143839.2
       1  4959.3  5040.4
Encroach Node=143007.6
       1 4848.19 5199.44
Encroach Node=142390.7
       1 4687.49 5140.75
Encroach Node=141548.6
       1  4793.8 5128.24
Encroach Node=141321.3
       1 4955.63 5138.41
Encroach Node=141253.3
       1 4955.63 5138.41
Encroach Node=140545.5
       1 4779.93 5081.51
Encroach Node=140119.2
       1  4841.2 5211.59
Encroach Node=139514.0
       1 4803.93 5220.89
Encroach Node=139102.9
       1 4846.23 5273.67
Encroach Node=138552.6
       1 4805.64 5148.47
Encroach Node=137847.9
       1    4700    5200
Encroach Node=137139.2
       1  4672.7  5395.7
Encroach Node=136610.9
       1    4700  5366.5
Encroach Node=135954.5
       1    4510  5258.2
Encroach Node=135338.0
       1  4238.3  5499.3
Encroach Node=134705.7
       1    3900    5110
Encroach Node=134488.2
       1  4447.2  5020.8
Encroach Node=134384.3
       1 4600.63 5171.71
Encroach Node=133647.1
       1 4365.61  5030.3
Encroach Node=133145.7
       1 4419.93  5020.7
Encroach Node=132585.8
       1 4284.73 5109.66
Encroach Node=131930.9
       1 4527.74 5086.83
Encroach Node=131259.3
       1 4486.15 5118.94
Encroach Node=130738.6
       1  4236.2 5037.22
Encroach Node=130075.4
       1 4326.58 5038.55
Encroach Node=129470.9
       1    4941    5059
Encroach Node=129420.9
       1    4941    5059
Encroach Node=128844.8
       1 4386.08 5451.94
Encroach Node=128319.9
       1 4413.03 5522.35
Encroach Node=127754.6
       1  4371.9 5479.81
Encroach Node=127007.4
       1  4492.2 5267.67
Encroach Node=126357.7
       1 4329.67 5249.43
Encroach Node=125459.6
       1  4556.7 5443.89
Encroach Node=124311.5
       1 4663.03 5371.83
Encroach Node=123413.1
       1 4924.64 5469.88
Encroach Node=122289.7
       1 4632.63 5202.75
Encroach Node=121291.1
       1 4330.64 5292.12
Encroach Node=120482.7
       1 4086.08  5435.5
Encroach Node=119830.1
       1 4324.66 5406.53
Encroach Node=118826.2
       1    4279  5025.6
Encroach Node=117965.2
       1 4116.65 5202.78
Encroach Node=117339.9
       1 4176.59 5169.59
Encroach Node=116831.8
       1 4438.61  5041.5
Encroach Node=116779.8
       1 4438.61  5041.5
Encroach Node=115900.6
       1 3982.42  5025.5
Encroach Node=115046.5
       1  3928.5  5025.9
Encroach Node=114391.4
       1 4001.45 5271.51
Encroach Node=113597.7
       1 3815.98    5277
Encroach Node=112879.1
       1  3987.6 5426.02
Encroach Node=112185.3
       1 4626.99 5785.76
Encroach Node=111299.7
       1 4568.77 5646.96
Encroach Node=110791.0
       1 4700.44 5758.56
Encroach Node=110212.5
       1 4183.19 5760.74
Encroach Node=109394.1
       1 4378.85 6352.04
Encroach Node=108567.7
       1 4576.33 6993.55
Encroach Node=107676.6
       1  4971.3  6841.5
Encroach Node=107045.6
       1 4906.64 6594.71
Encroach Node=106975.6
       1 4906.64 6594.71
Encroach Node=105925.9
       1 4762.14 5513.23
Encroach Node=105105.1
       1 4424.85 5467.96
Encroach Node=104155.3
       1 4259.83 5606.78
Encroach Node=103521.3
       1 4477.58 5333.69
Encroach Node=102929.8
       1 4665.28 5543.76
Encroach Node=102061.8
       1  4024.4  5583.5
Encroach Node=102003.8
       1  4024.4  5583.5
Encroach Node=101325.1
       1 3932.55 5209.08
Encroach Node=100495.9
       1 3364.29  5030.4
Encroach Node=99729.6
       1 3717.85 5055.92
Encroach Node=98671.3
       1 4691.31 5796.41
Encroach Node=97741.4
       1 4253.05 5821.18
Encroach Node=96806.0
       1  4014.8 5493.89
Encroach Node=96015.8
       1 4580.45 5748.75
Encroach Node=95120.1
       1 3979.48 5451.24
Encroach Node=94243.5
       1  4174.5    5840
Encroach Node=93265.3
       1 3784.71  5031.8
Encroach Node=92467.5
       1 3941.65 5076.55
Encroach Node=91829.2
       1 3844.72  5032.3
Encroach Node=90898.0
       1  3961.1 5109.71
Encroach Node=89741.9
       1 4221.82 5128.96
Encroach Node=88934.5
       1 3968.68 5259.94
Encroach Node=88166.1
       1 3991.33 5433.48
Encroach Node=87433.8
       1    4943    5057
Encroach Node=87389.3
       1    4943    5057
Encroach Node=87176.6
       1  4503.5 5537.96
Encroach Node=86391.7
       1 3667.91 5286.02
Encroach Node=85479.8
       1 3997.01 5642.89
Encroach Node=84829.4
       1  3698.4 5274.85
Encroach Node=84151.1
       1 3725.52 5220.48
Encroach Node=83495.6
       1 3939.01 5324.58
Encroach Node=82881.3
       1 4050.01  5293.3
Encroach Node=82048.9
       1 4873.23  5983.1
Encroach Node=81458.1
       1 4545.11 6259.98
Encroach Node=80776.2
       1 4711.49 6333.55
Encroach Node=80176.9
       1 4639.98 5905.43
Encroach Node=79730.6
       1 4623.39 5977.91
Encroach Node=79126.2
       1 4736.29 6048.58
Encroach Node=78567.5
       1 4687.84 6248.88
Encroach Node=77995.4
       1  4583.4 5859.96
Encroach Node=77348.3
       1 4238.03 5303.88
Encroach Node=76735.6
       1 4075.82 5513.93
Encroach Node=75954.6
       1    3819 5559.36
Encroach Node=75156.6
       1  3913.5 5362.72
Encroach Node=74445.2
       1  4680.7  6232.3
Encroach Node=73884.1
       1  4965.2 6416.44
Encroach Node=73361.4
       1  4965.3 6459.25
Encroach Node=72721.2
       1 4466.35 6148.68
Encroach Node=72059.8
       1    3815    5687
Encroach Node=71440
       1    4396    5067
Encroach Node=71321
       1    4408    5054
Encroach Node=70654.9
       1    4200 5333.04
Encroach Node=70016.6
       1 4757.67 5696.45
Encroach Node=69509.5
       1 4842.69 5658.74
Encroach Node=68942.5
       1  4610.3 5896.02
Encroach Node=68477.7
       1 4488.31 6206.86
Encroach Node=67968.5
       1 4762.19 6235.34
Encroach Node=67463.1
       1  4964.4 6059.97
Encroach Node=66820.6
       1 4689.89 6201.81
Encroach Node=66159.1
       1 4736.28  6241.5
Encroach Node=65378.6
       1 4877.95 6480.15
Encroach Node=64601.4
       1 4901.39 6918.45
Encroach Node=64071.4
       1    4900    6500
Encroach Node=63185.5
       1    4950    5570
Encroach Node=63135.5
       1    4950    5570
Encroach Node=63058.5
       1    4950    5650
Computation Interval=1HOUR
Output Interval=1HOUR
Run HTab= 0
Run UNet= 0
Run PostProcess= 0
Run WQNet= 0
UNET Theta= 1
UNET Theta Warmup= 1
UNET ZTol= 0.02
UNET ZSATol= 0.05
UNET MxIter= 20
UNET MaxInSteps= 1
UNET DtIC= 0
UNET DtMin= 0
UNET MaxCRTS= 20
UNET WFStab= 2
UNET SFStab= 1
UNET WFX= 1
UNET SFX= 1
UNET DSS MLevel= 4
UNET DZMax Abort= 100
UNET Convert EG Bridges=-1
UNET Use Existing IB Tables=-1
UNET Froude Reduction=False
UNET Froude Limit= 1
UNET Froude Power= 10
UNET Time Slicing=0,0, 5
UNET Junction Losses=0
Instantaneous Interval=1HOUR
Write IC File= 0
Write IC File at Sim End=0
Echo Input=False
Echo Parameters=False
Echo Output=False
Write Detailed= 0
WQ AD Non Conservative
WQ ULTIMATE=-1
WQ Max Comp Step=1HOUR
WQ Output Interval=15MIN
WQ Output Selected Increments= 0
WQ Output face flow=0
WQ Output face velocity=0
WQ Output face area=0
WQ Output face dispersion=0
WQ Output cell volume=0
WQ Output cell surface area=0
WQ Output cell continuity=0
WQ Output cumulative cell continuity=0
WQ Output face conc=0
WQ Output face dconc_dx=0
WQ Output face courant=0
WQ Output face peclet=0
WQ Output face adv mass=0
WQ Output face disp mass=0
WQ Output cell mass=0
WQ Output cell source sink temp=0
WQ Output cell source sink nsm=0
WQ Output MaxMinRange=-1
WQ Daily Max Min Mean=-1
WQ Daily Range=0
WQ Daily Time=0
WQ Create Restart=0
WQ Fixed Restart=0
WQ System Summary=0
WQ Use Fixed Temperature=0
Sorting and Armoring Iterations= 10
XS Update Threshold= 0.02
Hydraulics Update Threshold= 0.02
Energy Slope Method= 1
Volume Change Method= 0
XS Weighting Method= 0
Number of US Weighted Cross Sections= 1
Number of DS Weighted Cross Sections= 1
Upstream XS Weight=0.25
Main XS Weight=0.5
Downstream XS Weight=0.25
Number of DS XS's Weighted with US Boundary= 1
Upstream Boundary Weight= 1
Weight of XSs Associated with US Boundary= 0
Number of US XS's Weighted with DS Boundary= 1
Downstream Boundary Weight= 0.5
Weight of XSs Associated with DS Boundary= 0.5
Sediment Output Level= 4
Mass or Volume Output= 0
Output Increment Type= 1
Profile and TS Output Increment= 10
XS Output Flag= 0
XS Output Increment= 10
Disregard all LS=0
Disregard all Conn=0
Disregard all Breaches=0
Disregard all Pumps=0

--- B4544BLACKRIVER.p01 (plan) ---

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Plan Title=Duplicate Effective
Short Identifier=Duplicate
Geom File=g01
Flow File=f01
Encroach Node=143862.2
Encroach Node=141287.3
       4 4955.63 5138.41
Encroach Node=134688.2
       4    3900    5110
Encroach Node=129445.9
Encroach Node=116805.8
Encroach Node=107010.6
       4 4906.64 6594.71
Encroach Node=102032.8
       4  4024.4  5583.5
Encroach Node=87411.5
       1 4009.89 6002.99
Encroach Node=71410.8
       1    4960    5040
Encroach Node=71387.8
       1    4960    5040
Encroach Node=71364.8
       1    4960    5040
Encroach Node=63160.5

--- B4544BLACKRIVER.p03 (plan) ---

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Plan Title=Revised
Short Identifier=Revised
Geom File=g03
Flow File=f01

--- B4544BLACKRIVER.f01 (steady flow) ---

Flow Title= 100-Year-Single
Program Version=4.10
Number of Profiles= 2
Profile Names=100-Year,AFW
River Rch & RM=Black River,Reach - 1       ,143994.6
    1490    1490
River Rch & RM=Black River,Reach - 1       ,142390.7
    1907    1907
River Rch & RM=Black River,Reach - 1       ,140545.5
    1992    1992
River Rch & RM=Black River,Reach - 1       ,138552.6
    2131    2131
River Rch & RM=Black River,Reach - 1       ,135954.5
    2286    2286
River Rch & RM=Black River,Reach - 1       ,131930.9
    2347    2347
River Rch & RM=Black River,Reach - 1       ,129470.9
    2528    2528
River Rch & RM=Black River,Reach - 1       ,129420.9
    2583    2583
River Rch & RM=Black River,Reach - 1       ,127007.4
    2701    2701
River Rch & RM=Black River,Reach - 1       ,124311.5
    2778    2778
River Rch & RM=Black River,Reach - 1       ,121291.1
    2791    2791
River Rch & RM=Black River,Reach - 1       ,119830.1
    2980    2980
River Rch & RM=Black River,Reach - 1       ,118826.2
    3090    3090
River Rch & RM=Black River,Reach - 1       ,115046.5
    3154    3154
River Rch & RM=Black River,Reach - 1       ,111299.7
    3411    3411
River Rch & RM=Black River,Reach - 1       ,108567.7
    3532    3532
River Rch & RM=Black River,Reach - 1       ,105105.1
    3667    3667
River Rch & RM=Black River,Reach - 1       ,103521.3
    3698    3698
River Rch & RM=Black River,Reach - 1       ,100495.9
    3806    3806
River Rch & RM=Black River,Reach - 1       ,98671.3
    3880    3880
River Rch & RM=Black River,Reach - 1       ,94243.5
    3937    3937
River Rch & RM=Black River,Reach - 1       ,93265.3
    4077    4077
River Rch & RM=Black River,Reach - 1       ,91829.2
    4142    4142
River Rch & RM=Black River,Reach - 1       ,88934.5
    4226    4226
River Rch & RM=Black River,Reach - 1       ,87433.8
    4309    4309
River Rch & RM=Black River,Reach - 1       ,85479.8
    4345    4345
River Rch & RM=Black River,Reach - 1       ,83495.6
    4421    4421
River Rch & RM=Black River,Reach - 1       ,79126.2
    4485    4485
River Rch & RM=Black River,Reach - 1       ,75954.6
    4549    4549
River Rch & RM=Black River,Reach - 1       ,71440
    4604    4604
River Rch & RM=Black River,Reach - 1       ,68477.7
    4686    4686
River Rch & RM=Black River,Reach - 1       ,65378.6
    4742    4742
Boundary for River Rch & Prof#=Black River,Reach - 1       , 1
Up Type= 0
Dn Type= 1
Dn Known WS=172.98
Boundary for River Rch & Prof#=Black River,Reach - 1       , 2
Up Type= 0
Dn Type= 1
Dn Known WS=173.98
DSS Import GetInterval= 0
DSS Import GetPeak= 0
DSS Import FillOption= 0

--- B4544BLACKRIVER.g02 (geometry) ---

Geom Title=Corrected Effective
Program Version=4.10

River Reach=Black River     ,Reach - 1
Reach XY= 30
2086416.01100026632636.0003025382089657.67384702632307.466973612
2091426.44176939631392.6477040352097932.00768825625381.776797762
2099518.27376139  620345.47576652098809.26657724619419.966388603
2099524.52382472616462.4964214862103461.81372005612950.080831279
2105299.58234158613143.2127882242107187.10146722610782.438867241
2107167.10126457609857.429494411 2105992.5893636609260.113441994
 2105451.0838767608207.2227733832106025.58969799 604152.25168563
2108097.61069313602193.9718429942108043.36014342601414.093940735
2108780.11760876601177.6515449382110264.13264582598830.687763889
2114707.67767087595181.8407912652115204.68270686 593711.26589039
2114637.42695904 592663.135270012114871.17932758588738.595503877
2114111.42162919586775.7556150352112397.90426666584794.805542688
2112832.90867442582898.3463264612111610.89629215582009.957324693
2111823.14844283580424.3812585472110185.63185039577965.916347692
 2109985.3798213576500.5915000142108536.86514395575507.391436229

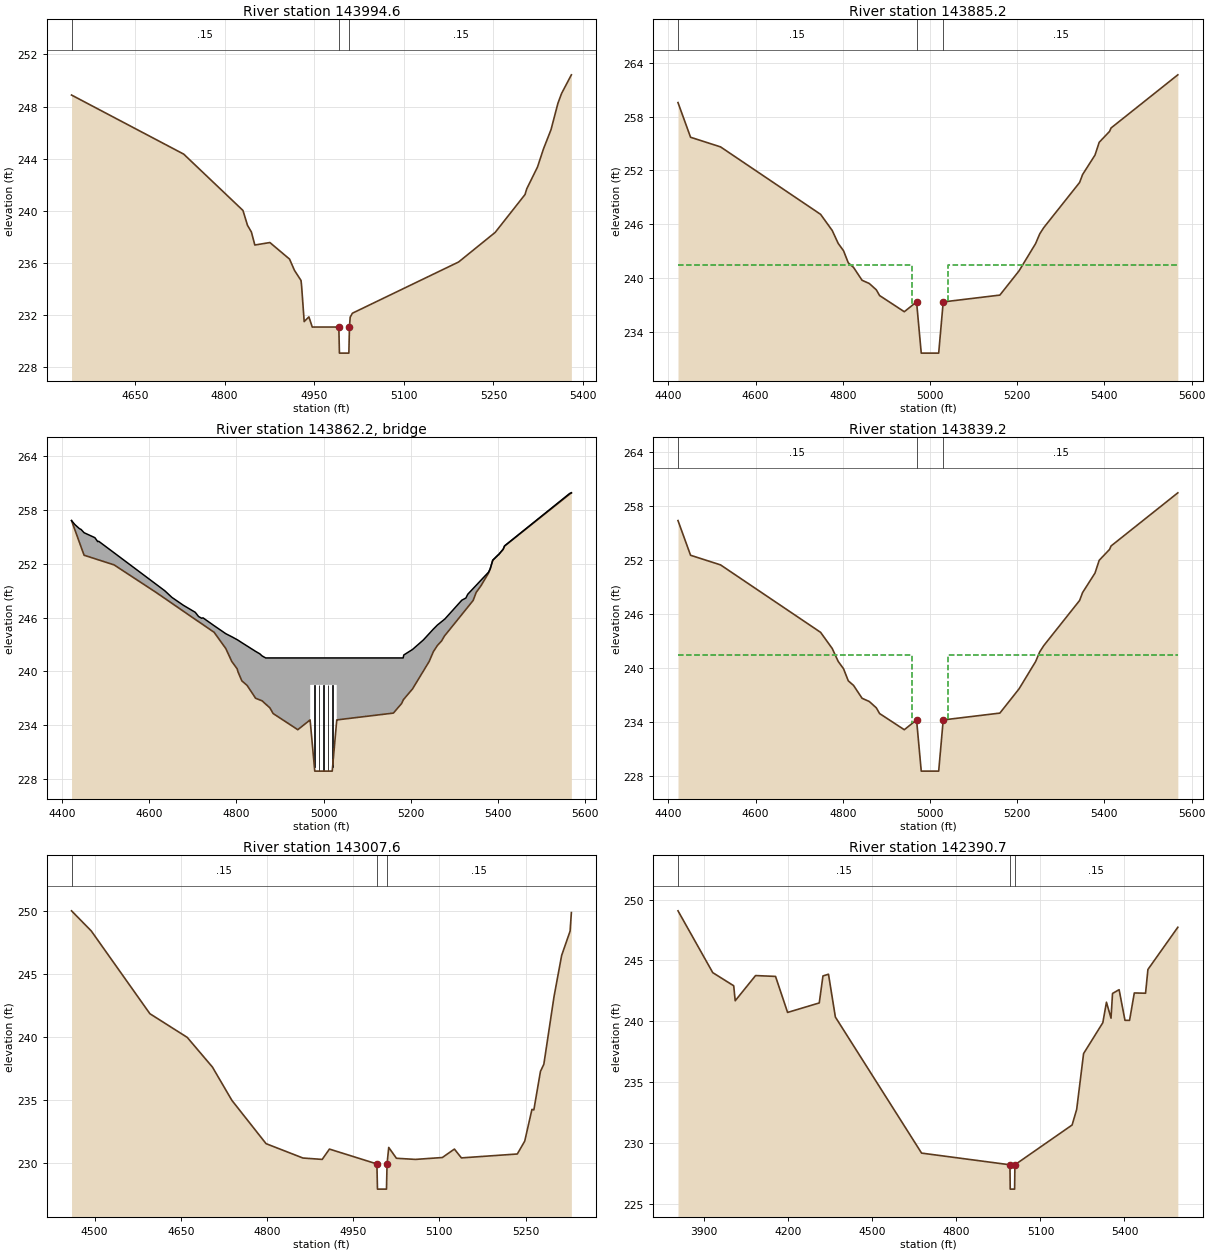
Type RM Length L Ch R = 1 ,143994.6,109.4011,109.4011,109.4011
BEGIN DESCRIPTION:
Black River 175.0
END DESCRIPTION:
XS GIS Cut Line= 3
2086241.86923574633057.8745772582086415.72099733632636.960312265
2086528.20213706632272.516619471
#Sta/Elev= 30
  4543.6  248.88  4731.4  244.35  4830.6  240.03  4838.2  238.89  4844.7  238.38
  4850.5  237.38  4875.7  237.57  4908.6   236.3  4916.8  235.44  4927.8  234.66
  4928.7  234.29  4933.1  231.51    4941  231.87  4946.6  231.09  4991.1  231.09
  4992.1  229.09  5007.9  229.09  5008.9  231.09  5010.1  231.84  5013.8  232.15
  5191.7  236.08  5252.9  238.35  5302.8  241.25  5305.7  241.69  5323.7  243.36
  5333.7  244.75  5346.3  246.22  5357.9  248.25    5364     249  5380.4  250.43
#Mann= 3 , 1 , 0
  4543.6     .15       0  4991.1    .045       0  5008.9     .15       0
Bank Sta=4991.1,5008.9
XS Rating Curve= 0 ,0
Exp/Cntr=0.5,0.3

Type RM Length L Ch R = 1 ,143885.2,46.0005,46.0005,46.0005
BEGIN DESCRIPTION:
Upstream Section of Bridge/Culvert/Weir
END DESCRIPTION:
XS GIS Cut Line= 4
2086315.12997807633212.0061390252086505.21190411632705.121002916
2086620.90307637632433.6882525732086726.77414913632142.535302411
#Sta/Elev= 30
  4422.2  259.56    4451   255.7  4519.7  254.63  4749.2  247.12  4775.9  245.32
  4789.6  243.88  4801.8  243.07  4812.7  241.72  4824.8  241.21  4844.3  239.78
  4860.9  239.42  4876.9  238.72  4884.5  238.08  4941.1  236.28  4969.3  237.37
    4980  231.67    5020  231.67  5030.4  237.37  5160.3  238.13  5204.3  240.83
  5242.2  243.86  5251.9  244.96  5261.1  245.65  5343.2  250.67    5350  251.55
  5378.5  253.72  5388.1  255.14    5412  256.36  5415.2  256.73  5568.4  262.65
#Mann= 3 , 1 , 0
  4422.2     .15       0  4969.3     .05       0  5030.4     .15       0
#XS Ineff= 2 , 0
       0    4959   241.5    5041       0   241.5
Permanent Ineff=
       F       F
Bank Sta=4969.3,5030.4
XS Rating Curve= 0 ,0
Exp/Cntr=0.5,0.3

Type RM Length L Ch R = 3 ,143862.2,,,
BEGIN DESCRIPTION:
Guy Road Bridge - TOR
Structure ID: Guy Road - Bridge
Approximate Survey Structure
END DESCRIPTION:
Bridge Culvert--1,0,-1,-1, 0
Deck Dist Width WeirC Skew NumUp NumDn MinLoCord MaxHiCord MaxSubmerge Is_Ogee
10,26,2.6,0, 60, 60, , , 0.95, 0, 1,1,,
  4422.2    4430  4440.3  4443.9    4451  4475.7  4482.3  4484.4  4519.7    4636
  4652.4  4678.4  4705.9  4713.5  4720.5  4723.8  4749.2  4775.9  4789.6  4801.8
  4804.2  4812.7  4824.8  4844.3  4854.2    4859  4867.4  4876.9  4884.5  4941.1
  4969.3 4969.41  4969.5 5030.29  5030.4  5160.3  5179.2  5182.6  5184.1  5204.3
  5228.9  5242.2  5251.9  5261.1  5270.8  5278.4  5317.2  5326.5  5330.8  5343.2
    5350  5362.4  5378.5  5382.2  5388.1  5401.7    5412  5415.2  5564.5  5568.4
  256.79  256.34  255.89  255.81  255.44  254.89  254.45  254.49  253.21  248.98
  248.24  247.37  246.58  246.11  245.92  245.96  245.09   244.2  243.86  243.54
  243.47   243.2  242.83  242.23  241.95  241.73   241.5   241.5   241.5   241.5
   241.5   241.5   241.5   241.5   241.5   241.5   241.5   241.5  241.83  242.45
   243.5   244.2  244.71  245.16  245.54  245.84  247.93  248.17  248.59  249.23
  249.58  250.22  251.05  251.41  252.38  253.01   253.6  253.97  259.81  259.88
  256.79  255.74  254.36  253.88  252.93  252.55  252.44  252.41  251.86  248.13
  247.58  246.71  245.79  245.54  245.31   245.2  244.35  242.55  241.11   240.3
  239.92  238.95  238.44  237.01  236.82  236.73  236.36  235.95  235.31  233.51
   234.6  234.54   238.5   238.5   234.6  235.36  236.43  236.78   236.9  238.06
  240.03  241.09  242.19  242.88  243.39     244  246.33  246.89  247.15   247.9
  248.78  249.62  250.95   251.4  252.37     253  253.59  253.96  259.73  259.88
  4422.2    4430  4440.3  4443.9    4451  4475.7  4482.3  4484.4  4519.7    4636
  4652.4  4678.4  4705.9  4713.5  4720.5  4723.8  4749.2  4775.9  4789.6  4801.8
  4804.2  4812.7  4824.8  4844.3  4854.2    4859  4867.4  4876.9  4884.5  4941.1
  4969.3 4969.41  4969.5 5030.29  5030.4  5160.3  5179.2  5182.6  5184.1  5204.3
  5228.9  5242.2  5251.9  5261.1  5270.8  5278.4  5317.2  5326.5  5330.8  5343.2
    5350  5362.4  5378.5  5382.2  5388.1  5401.7    5412  5415.2  5564.5  5568.4
  256.79  256.34  255.89  255.81  255.44  254.89  254.45  254.49  253.21  248.98
  248.24  247.37  246.58  246.11  245.92  245.96  245.09   244.2  243.86  243.54
  243.47   243.2  242.83  242.23  241.95  241.73   241.5   241.5   241.5   241.5
   241.5   241.5   241.5   241.5   241.5   241.5   241.5   241.5  241.83  242.45
   243.5   244.2  244.71  245.16  245.54  245.84  247.93  248.17  248.59  249.23
  249.58  250.22  251.05  251.41  252.38  253.01   253.6  253.97  259.81  259.88
  256.54  255.49  254.11  253.63  252.68   252.3  252.19  252.16  251.61  247.88
  247.33  246.46  245.54  245.29  245.06  244.95   244.1   242.3  240.86  240.05
  239.67   238.7  238.19  236.76  236.57  236.48  236.11   235.7  235.06  233.26
  234.35  234.29  238.25  238.25  234.35  235.11  236.18  236.53  236.65  237.81
  239.78  240.84  241.94  242.63  243.14  243.75  246.08  246.64   246.9  247.65
  248.53  249.37   250.7  251.15  252.12  252.75  253.34  253.71  259.48  259.63
Pier Skew, UpSta & Num, DnSta & Num=  ,4979.2, 2 ,4979.2, 2 , 0 , 0 , 0 ,,
       1       1
  228.06   239.5
       1       1
  227.81  239.25
Pier Skew, UpSta & Num, DnSta & Num=  ,4989.6, 2 ,4989.6, 2 , 0 , 0 , 0 ,,
       1       1
   227.9   239.5
       1       1
  227.65  239.25
Pier Skew, UpSta & Num, DnSta & Num=  ,5000, 2 ,5000, 2 , 0 , 0 , 0 ,,
       1       1
   227.9   239.5
       1       1
  227.65  239.25
Pier Skew, UpSta & Num, DnSta & Num=  ,5010.4, 2 ,5010.4, 2 , 0 , 0 , 0 ,,
       1       1
   227.9   239.5
       1       1
  227.65  239.25
Pier Skew, UpSta & Num, DnSta & Num=  ,5020.8, 2 ,5020.8, 2 , 0 , 0 , 0 ,,
       1       1
  228.06   239.5
       1       1
  227.81  239.25
Abutment Skew #Up #Dn= , 2 , 2
  4969.3    4974
   238.5   232.1
  4969.3    4974
  238.25  231.85
Abutment Skew #Up #Dn= , 2 , 2
    5026 5030.49
  232.19   238.5
    5026 5030.49
  231.94  238.25
BR Coef= 1 , 1 , 0 ,1.25, 0 ,,,0.8,0,2,0,
WSPro=,,,, 1 ,,,, 0 ,,,, 0 ,,,,-1 ,-1 ,-1 , 0 , 0 , 0 , 0 , 0
BR U #Sta/Elev= 94
  4422.2  256.79    4430  255.74  4430.8  255.64  4440.3  254.36  4443.9  253.88
  4449.5  253.13    4451  252.93  4456.9  252.84  4475.7  252.55  4482.3  252.44
  4484.4  252.41  4519.7  251.86  4614.9  248.83    4636  248.13  4652.4  247.58
  4678.4  246.71  4705.9  245.79  4713.5  245.54  4720.5  245.31  4723.8   245.2
  4749.2  244.35  4772.6  242.77  4775.9  242.55  4789.6  241.11  4797.9  240.56
  4801.8   240.3  4804.2  239.92  4812.7  238.95  4824.8  238.44  4844.3  237.01
  4849.6  236.91  4851.1  236.88  4854.2  236.82    4859  236.73  4860.9  236.65
  4867.4  236.36  4876.9  235.95  4884.5  235.31  4941.1  233.51  4969.3   234.6
 4969.41  234.54  4969.5  234.49    4974   232.1    4980   228.9    5000   228.9
    5020   228.9    5026  232.19 5030.29  234.54  5030.4   234.6  5030.5   234.6
  5160.3  235.36  5179.2  236.43  5182.6  236.78  5183.4  236.86  5183.7  236.88
  5183.8  236.88  5183.9  236.89  5184.1   236.9  5201.9  237.92  5204.3  238.06
  5228.9  240.03  5242.2  241.09  5251.9  242.19  5258.6  242.69  5261.1  242.88
  5270.8  243.39  5277.3  243.93  5278.4     244  5281.1  244.16  5317.2  246.33
  5326.5  246.89  5330.8  247.15  5343.2   247.9    5350  248.78  5362.4  249.62
  5362.7  249.66  5378.5  250.95  5382.2   251.4  5388.1  252.37  5389.6  252.44
  5392.1  252.57  5400.1  252.96  5400.3  252.97  5401.7     253    5412  253.59
  5415.2  253.96  5444.8   255.1  5447.5  255.21  5452.2  255.39  5456.1  255.54
    5468     256  5477.3  256.36  5564.5  259.73  5568.4  259.88
BR U #Mann= 3
  4422.2     .15  4969.3     .05  5030.4     .15
BR U Banks=4969.3,5030.4
BR D #Sta/Elev= 94
  4422.2  256.54    4430  255.49  4430.8  255.39  4440.3  254.11  4443.9  253.63
  4449.5  252.88    4451  252.68  4456.9  252.59  4475.7   252.3  4482.3  252.19
  4484.4  252.16  4519.7  251.61  4614.9  248.58    4636  247.88  4652.4  247.33
  4678.4  246.46  4705.9  245.54  4713.5  245.29  4720.5  245.06  4723.8  244.95
  4749.2   244.1  4772.6  242.52  4775.9   242.3  4789.6  240.86  4797.9  240.31
  4801.8  240.05  4804.2  239.67  4812.7   238.7  4824.8  238.19  4844.3  236.76
  4849.6  236.66  4851.1  236.63  4854.2  236.57    4859  236.48  4860.9   236.4
  4867.4  236.11  4876.9   235.7  4884.5  235.06  4941.1  233.26  4969.3  234.35
 4969.41  234.29  4969.5  234.24    4974  231.85    4980  228.65    5000  228.65
    5020  228.65    5026  231.94 5030.29  234.29  5030.4  234.35  5030.5  234.35
  5160.3  235.11  5179.2  236.18  5182.6  236.53  5183.4  236.61  5183.7  236.63
  5183.8  236.63  5183.9  236.64  5184.1  236.65  5201.9  237.67  5204.3  237.81
  5228.9  239.78  5242.2  240.84  5251.9  241.94  5258.6  242.44  5261.1  242.63
  5270.8  243.14  5277.3  243.68  5278.4  243.75  5281.1  243.91  5317.2  246.08
  5326.5  246.64  5330.8   246.9  5343.2  247.65    5350  248.53  5362.4  249.37
  5362.7  249.41  5378.5   250.7  5382.2  251.15  5388.1  252.12  5389.6  252.19
  5392.1  252.32  5400.1  252.71  5400.3  252.72  5401.7  252.75    5412  253.34
  5415.2  253.71  5444.8  254.85  5447.5  254.96  5452.2  255.14  5456.1  255.29
    5468  255.75  5477.3  256.11  5564.5  259.48  5568.4  259.63
BR D #Mann= 3
  4422.2     .15  4969.3     .05  5030.4     .15
BR D Banks=4969.3,5030.4
BC Design=,, 0 ,, 0 ,,,,,,
BC HTab HWMax=262.65
BC Use User HTab Curves=0
BC User HTab FreeFlow(D)= 0

Type RM Length L Ch R = 1 ,143839.2,831.6084,831.6084,831.6084
BEGIN DESCRIPTION:
Downstream Section of Bridge/Culvert/Weir
END DESCRIPTION:
XS GIS Cut Line= 4
2086358.63041885 633226.956290512086548.71234489632720.081154503
2086664.40351715 632448.648404162086770.28459001632157.495453998
#Sta/Elev= 30
  4422.2  256.41    4451  252.55  4519.7  251.48  4749.2  243.97  4775.9  242.17
  4789.6  240.73  4801.8  239.92  4812.7  238.57  4824.8  238.06  4844.3  236.63
  4860.9  236.27  4876.9  235.57  4884.5  234.93  4941.1  233.13  4969.3  234.22
    4980  228.52    5020  228.52  5030.4  234.22  5160.3  234.98  5204.3  237.68
  5242.2  240.71  5251.9  241.81  5261.1   242.5  5343.2  247.52    5350   248.4
  5378.5  250.57  5388.1  251.99    5412  253.21  5415.2  253.58  5568.4   259.5
#Mann= 3 , 1 , 0
  4422.2     .15       0  4969.3     .05       0  5030.4     .15       0
#XS Ineff= 2 , 0
       0    4959   241.5    5041       0   241.5
Permanent Ineff=
       F       F
Bank Sta=4969.3,5030.4
XS Rating Curve= 0 ,0
Exp/Cntr=0.5,0.3

Type RM Length L Ch R = 1 ,143007.6,616.9063,616.9063,616.9063
BEGIN DESCRIPTION:
Black River 174.0
END DESCRIPTION:
XS GIS Cut Line= 3
2087283.64979178633146.775478063 2087356.8705337632599.559933299
 2087280.0297551632291.066807435
#Sta/Elev= 30
  4459.7  250.04  4494.1  248.44  4596.1  241.87  4661.1  239.99    4705  237.63
  4738.8  234.99  4798.3  231.55  4862.5  230.41    4896   230.3  4908.6  231.12
  4991.2  229.94  4992.2  227.94  5007.9  227.94  5008.9  229.94  5011.8  231.25
  5025.2  230.39  5058.2   230.3  5105.1  230.45  5126.1  231.12  5138.3  230.42
  5235.6  230.73  5248.5  231.75  5261.1  234.27  5264.4  234.23  5275.9  237.29
  5281.8  237.86  5299.6  243.25  5312.8   246.5  5327.5  248.43  5329.7   249.9
#Mann= 3 , 1 , 0
  4459.7     .15       0  4991.2    .045       0  5008.9     .15       0
Bank Sta=4991.2,5008.9
XS Rating Curve= 0 ,0
Exp/Cntr=0.3,0.1

Type RM Length L Ch R = 1 ,142390.7,842.1085,842.1085,842.1085
BEGIN DESCRIPTION:
Black River 173.0
END DESCRIPTION:
XS GIS Cut Line= 3
2088299.62008629633630.6203807122087955.69660142632482.448746648
2087749.67451386631934.233191751
#Sta/Elev= 30
  3806.2  249.07  3930.3  243.99  4005.1  242.91  4010.4  241.68  4083.1  243.75
  4154.4  243.68  4197.4  240.72  4310.4   241.5  4323.7  243.72  4343.4  243.86
    4368  240.34  4675.7  229.16  4991.1   228.2  4992.1   226.2  5007.8   226.2
  5008.8   228.2    5213  231.47  5229.3  232.75    5254  237.34  5322.7  239.88
  5335.6  241.56  5351.9  240.25  5357.3  242.28  5380.8  242.59  5401.7  240.07
  5418.1  240.07    5435  242.32  5475.2   242.3  5483.6  244.25  5590.4  247.72
#Mann= 3 , 1 , 0
  3806.2     .15       0  4991.1    .045       0  5008.8     .15       0
Bank Sta=4991.1,5008.8
XS Rating Curve= 0 ,0
Exp/Cntr=0.3,0.1

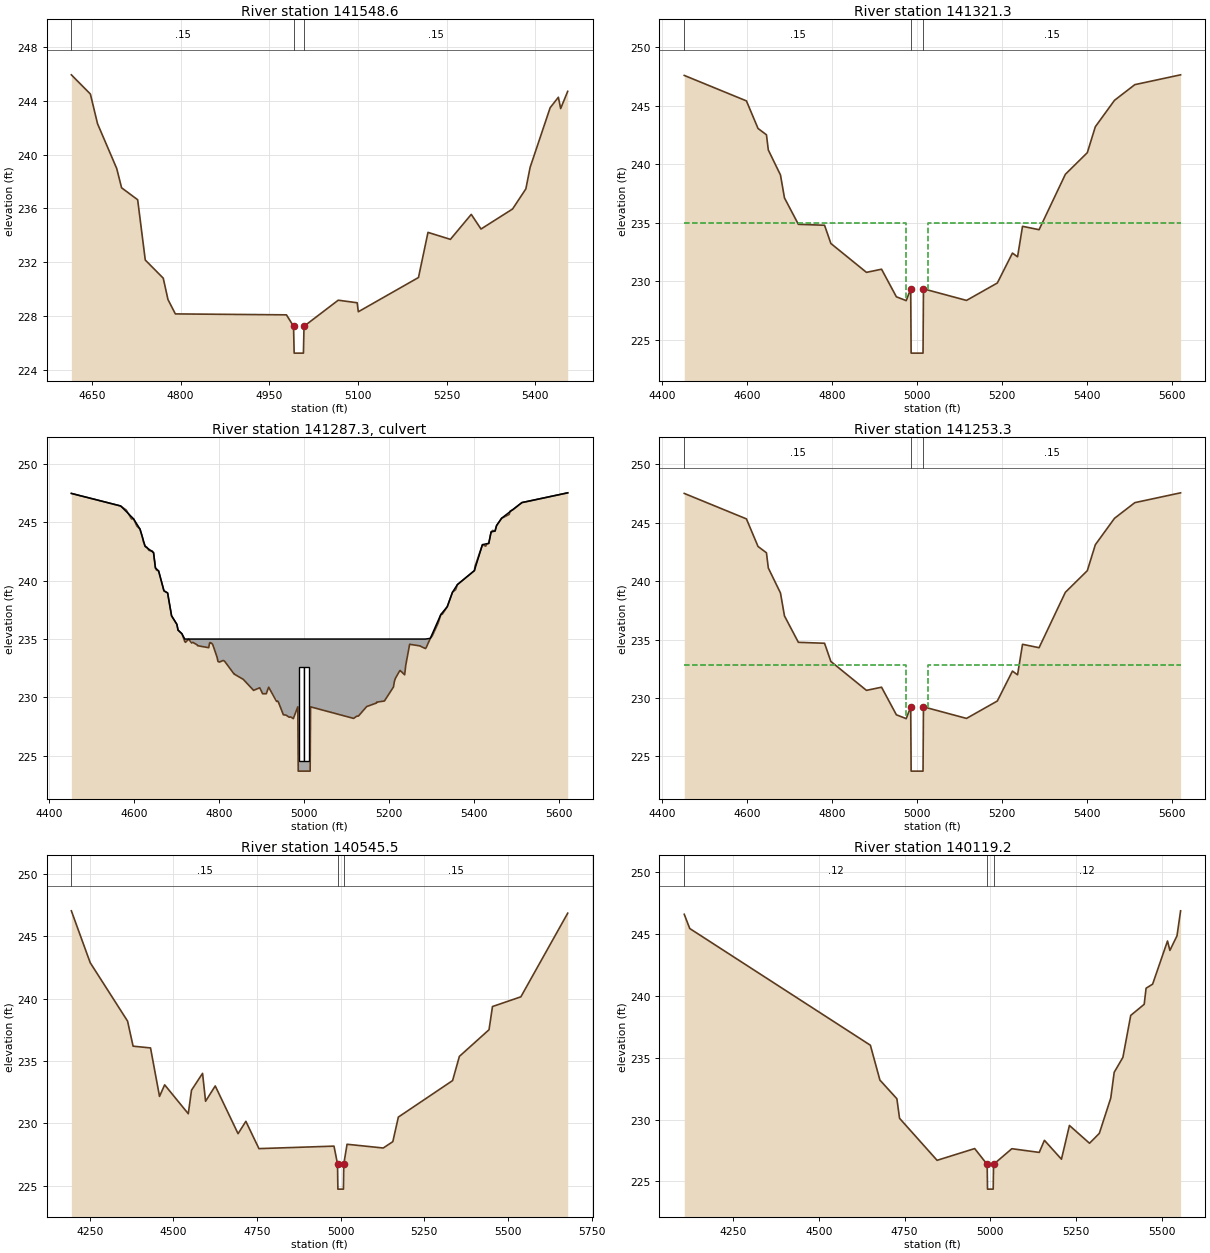
Type RM Length L Ch R = 1 ,141548.6,227.3023,227.3023,227.3023
BEGIN DESCRIPTION:
Black River 172.0
END DESCRIPTION:
XS GIS Cut Line= 3
2088664.74378597632830.7022753922088568.04280613632479.728719087
2088417.56128135632028.294144841
#Sta/Elev= 30
  4615.1  245.94  4647.3  244.51  4659.4   242.3  4691.9  238.96  4700.1  237.53
  4727.3  236.64  4740.2  232.15  4770.6   230.8  4778.6  229.21  4791.1  228.14
  4979.1  228.07  4991.1  227.22  4992.1  225.22  5007.8  225.22  5008.8  227.22
  5066.7  229.16  5098.8  228.97  5100.7   228.3  5202.5  230.85  5218.6  234.21
  5256.5  233.69  5291.8  235.55  5308.3  234.46  5361.7  235.95  5384.2  237.45
  5391.4  239.05  5425.3  243.49  5439.2  244.27  5443.1  243.43    5455  244.71
#Mann= 3 , 1 , 0
  4615.1     .15       0  4991.1    .045       0  5008.8     .15       0
Bank Sta=4991.1,5008.8
XS Rating Curve= 0 ,0
Exp/Cntr=0.5,0.3

Type RM Length L Ch R = 1 ,141321.3,68.0007,68.0007,68.0007
BEGIN DESCRIPTION:
Upstream Section of Bridge/Culvert/Weir
END DESCRIPTION:
XS GIS Cut Line= 3
2088923.87641168 632959.843583942089021.00739588 632428.84820353
2089208.94930023 631829.62213176
#Sta/Elev= 30
  4452.2  247.61  4598.5  245.43  4625.8  243.07  4645.6  242.53    4650  241.23
  4678.6  239.09    4688  237.13  4720.7  234.87  4782.3  234.79  4797.2  233.23
  4880.9  230.76  4916.4  231.03  4951.3  228.67  4974.4  228.34    4985  229.35
    4986  223.85    5014  223.85    5015  229.35  5116.3  228.36  5188.8  229.85
  5224.4  232.41  5236.4  232.09  5248.1   234.7    5287  234.41  5348.9  239.15
  5400.5     241  5419.4  243.22  5464.5  245.48  5512.3  246.82    5620  247.66
#Mann= 3 , 1 , 0
  4452.2     .15       0    4985     .05       0    5015     .15       0
#XS Ineff= 2 , 0
       0    4974     235    5026       0     235
Permanent Ineff=
       F       F
Bank Sta=4985,5015
XS Rating Curve= 0 ,0
Exp/Cntr=0.5,0.3

Type RM Length L Ch R = 2 ,141287.3,,,
BEGIN DESCRIPTION:
Old Stage Road TOR
Structure ID: Old Stage Road
Approximate Survey Structure
END DESCRIPTION:
Bridge Culvert--1,0,-1,-1, 0
Deck Dist Width WeirC Skew NumUp NumDn MinLoCord MaxHiCord MaxSubmerge Is_Ogee
10,48,3,0, 60, 60, , , 0.95, 0, 1,1,,
  4452.2  4568.1  4598.5  4613.7  4625.8  4645.6    4650  4657.5  4670.1  4678.6
    4688  4700.5  4703.2  4712.3  4719.1  4728.1  4749.2  4775.4  4777.2  4782.3
  4797.2    4813  4835.4  4880.9  4895.5  4902.1  4910.8  4916.4    4939  4951.3
  4974.4    4985    4986    5014    5015  5116.3  5127.6    5147  5188.8  5210.1
  5214.4  5225.8  5236.4    5239  5248.1  5285.3  5296.7  5321.6  5336.6  5348.9
  5360.4  5400.5  5419.4  5434.3  5439.7    5449  5452.6  5464.5  5512.3    5620
  247.46  246.39  245.29  244.41  242.93  242.39  241.09  240.83  239.13  238.95
  236.99  236.26  235.77  235.46     235     235     235     235     235     235
     235     235     235     235     235     235     235     235     235     235
     235     235     235     235     235     235     235     235     235     235
     235     235     235     235     235     235  235.06  237.11  237.77  239.01
  239.66  240.86  243.08  243.19  244.16  244.24  244.71  245.34  246.68  247.51
  247.46  246.38  245.28   244.4  242.92  242.38  241.08  240.82  239.12  238.94
  236.98  236.25  235.76  235.45  234.79  234.99  234.43  234.26  234.63  234.64
  233.08  233.09  231.99  230.61  230.83  230.32  230.32  230.88  229.63  228.52
  228.19   229.2   223.7   223.7   229.2  228.21  228.41  229.22   229.7   230.9
  231.62  232.31  231.94  232.76  234.55  234.19  235.05   237.1  237.76     239
  239.65  240.85  243.07  243.18  244.15  244.23   244.7  245.33  246.67  247.51
  4452.2  4568.1  4598.5  4613.7  4625.8  4645.6    4650  4657.5  4670.1  4678.6
    4688  4700.5  4703.2  4712.3  4719.1  4728.1  4749.2  4775.4  4777.2  4782.3
  4797.2    4813  4835.4  4880.9  4895.5  4902.1  4910.8  4916.4    4939  4951.3
  4974.4    4985    4986    5014    5015  5116.3  5127.6    5147  5188.8  5210.1
  5214.4  5225.8  5236.4    5239  5248.1  5285.3  5296.7  5321.6  5336.6  5348.9
  5360.4  5400.5  5419.4  5434.3  5439.7    5449  5452.6  5464.5  5512.3    5620
  247.46  246.39  245.29  244.41  242.93  242.39  241.09  240.83  239.13  238.95
  236.99  236.26  235.77  235.46     235     235     235     235     235     235
     235     235     235     235     235     235     235     235     235     235
     235     235     235     235     235     235     235     235     235     235
     235     235     235     235     235     235  235.06  237.11  237.77  239.01
  239.66  240.86  243.08  243.19  244.16  244.24  244.71  245.34  246.68  247.51
  247.22  246.14  245.04  244.16  242.68  242.14  240.84  240.58  238.88   238.7
  236.74  236.01  235.52  235.21  234.55  234.75  234.19  234.02  234.39   234.4
  232.84  232.85  231.75  230.37  230.59  230.08  230.08  230.64  229.39  228.28
  227.95  228.96  223.46  223.46  228.96  227.97  228.17  228.98  229.46  230.66
  231.38  232.07   231.7  232.52  234.31  233.95  234.81  236.86  237.52  238.76
  239.41  240.61  242.83  242.94  243.91  243.99  244.46  245.09  246.43  247.27
BR Coef= 1 , 0 , 0 ,1.25, 0 ,,,0.8,-1,2,0,
WSPro=,,,, 1 ,,,, 0 ,,,, 0 ,,,,-1 ,-1 ,-1 , 0 , 0 , 0 , 0 , 0
Culvert=2,8,12,48,0.015,0.4,1,8,1,224.6,4993.47,224.36,4993.47,Culvert #1  , 0 ,10
Culvert Bottom n=0.015
Culvert=2,8,12,48,0.015,0.4,1,8,1,224.6,5006.47,224.36,5006.47,Culvert #2  , 0 ,10
Culvert Bottom n=0.015
BR U #Sta/Elev= 169
  4452.2  247.46  4458.9   247.4  4466.7  247.32  4472.1  247.27  4482.2  247.18
  4482.6  247.18  4484.9  247.16    4491   247.1  4529.4  246.74  4529.8  246.74
  4538.2  246.66  4551.7  246.53    4557  246.48  4565.5   246.4  4568.1  246.38
  4570.1  246.33  4580.7  246.05  4581.4  246.03  4590.8  245.46  4593.8  245.28
  4593.9  245.28  4597.2  245.28  4598.5  245.28  4600.8   245.1  4605.5  244.74
  4606.4  244.67  4613.7   244.4  4619.2  243.74  4621.5  243.35  4622.4  243.26
  4625.8  242.92  4628.6   242.9  4630.5  242.81  4635.1  242.58  4638.9  242.56
  4641.9  242.55  4645.6  242.38    4650  241.08  4652.6   240.9  4654.6  240.87
  4657.5  240.82  4658.8  240.64  4661.5  240.28  4669.1  239.24  4669.7  239.16
  4670.1  239.12  4673.2  239.05  4677.4  238.97  4678.6  238.94  4679.6  238.81
  4680.7   238.5    4688  236.98  4700.5  236.25  4703.2  235.76  4712.3  235.45
  4719.1  234.79  4720.7  234.72  4728.1  234.99  4735.3  234.66  4737.7  234.72
  4748.2   234.5  4749.2  234.43  4775.4  234.26  4777.2  234.63  4778.7   234.7
  4782.3  234.64  4784.9  234.52  4794.9  233.46  4797.2  233.08  4800.6  233.03
  4809.6  233.17    4813  233.09  4835.4  231.99  4835.5     232  4856.7  231.55
  4880.9  230.61  4895.5  230.83  4902.1  230.32  4910.8  230.32  4916.4  230.88
  4935.1  229.66  4937.3   229.7    4939  229.63  4950.9  228.53  4951.3  228.52
  4957.3  228.49  4964.9  228.31  4968.1  228.34  4974.4  228.19    4985   229.2
    4986   223.7    5000   223.7    5014   223.7    5015   229.2  5116.3  228.21
  5123.6   228.4  5127.6  228.41    5147  229.22  5170.3  229.53  5170.5   229.6
  5188.8   229.7  5210.1   230.9  5212.1  231.35  5214.4  231.62  5224.4  232.26
  5225.8  232.31  5236.4  231.94    5239  232.76  5248.1  234.55  5272.9  234.41
  5273.8  234.38  5285.3  234.19    5287  234.26  5296.7  235.05  5301.3  235.27
  5315.2  236.37  5321.6   237.1  5324.8  237.12  5336.6  237.76  5348.9     239
  5356.4  239.23  5360.4  239.65  5363.1  239.73  5382.9  240.32  5384.6  240.37
  5392.8  240.62  5397.6  240.76  5400.5  240.85  5401.8   241.2  5405.7  241.61
  5419.4  243.07  5427.2  242.95  5429.3  243.12  5431.1  243.14  5434.3  243.18
  5439.7  244.15  5441.7  244.23  5443.4  244.29    5449  244.23  5452.6   244.7
  5464.5  245.33  5473.7   245.5  5478.5  245.59  5482.3  245.66    5483  245.75
  5484.6  245.95  5484.7  245.95  5491.3  246.07  5500.6  246.34  5500.9  246.34
  5506.9  246.52  5512.3  246.67  5519.3  246.72  5529.5   246.8  5533.3  246.83
  5536.9  246.86  5545.9  246.93  5554.7     247  5555.8  247.01  5561.8  247.06
    5563  247.07  5566.2  247.09    5579  247.19  5579.9   247.2  5586.7  247.25
  5590.8  247.28  5597.3  247.33  5603.7  247.38    5620  247.51
BR U #Mann= 3
  4452.2     .15    4985     .05    5015     .15
BR U Banks=4985,5015
BR D #Sta/Elev= 169
  4452.2  247.22  4458.9  247.16  4466.7  247.08  4472.1  247.03  4482.2  246.94
  4482.6  246.94  4484.9  246.92    4491  246.86  4529.4   246.5  4529.8   246.5
  4538.2  246.42  4551.7  246.29    4557  246.24  4565.5  246.16  4568.1  246.14
  4570.1  246.09  4580.7  245.81  4581.4  245.79  4590.8  245.22  4593.8  245.04
  4593.9  245.04  4597.2  245.04  4598.5  245.04  4600.8  244.86  4605.5   244.5
  4606.4  244.43  4613.7  244.16  4619.2   243.5  4621.5  243.11  4622.4  243.02
  4625.8  242.68  4628.6  242.66  4630.5  242.57  4635.1  242.34  4638.9  242.32
  4641.9  242.31  4645.6  242.14    4650  240.84  4652.6  240.66  4654.6  240.63
  4657.5  240.58  4658.8   240.4  4661.5  240.04  4669.1     239  4669.7  238.92
  4670.1  238.88  4673.2  238.81  4677.4  238.73  4678.6   238.7  4679.6  238.57
  4680.7  238.26    4688  236.74  4700.5  236.01  4703.2  235.52  4712.3  235.21
  4719.1  234.55  4720.7  234.48  4728.1  234.75  4735.3  234.42  4737.7  234.48
  4748.2  234.26  4749.2  234.19  4775.4  234.02  4777.2  234.39  4778.7  234.46
  4782.3   234.4  4784.9  234.28  4794.9  233.22  4797.2  232.84  4800.6  232.79
  4809.6  232.93    4813  232.85  4835.4  231.75  4835.5  231.76  4856.7  231.31
  4880.9  230.37  4895.5  230.59  4902.1  230.08  4910.8  230.08  4916.4  230.64
  4935.1  229.42  4937.3  229.46    4939  229.39  4950.9  228.29  4951.3  228.28
  4957.3  228.25  4964.9  228.07  4968.1   228.1  4974.4  227.95    4985  228.96
    4986  223.46    5000  223.46    5014  223.46    5015  228.96  5116.3  227.97
  5123.6  228.16  5127.6  228.17    5147  228.98  5170.3  229.29  5170.5  229.36
  5188.8  229.46  5210.1  230.66  5212.1  231.11  5214.4  231.38  5224.4  232.02
  5225.8  232.07  5236.4   231.7    5239  232.52  5248.1  234.31  5272.9  234.17
  5273.8  234.14  5285.3  233.95    5287  234.02  5296.7  234.81  5301.3  235.03
  5315.2  236.13  5321.6  236.86  5324.8  236.88  5336.6  237.52  5348.9  238.76
  5356.4  238.99  5360.4  239.41  5363.1  239.49  5382.9  240.08  5384.6  240.13
  5392.8  240.38  5397.6  240.52  5400.5  240.61  5401.8  240.96  5405.7  241.37
  5419.4  242.83  5427.2  242.71  5429.3  242.88  5431.1   242.9  5434.3  242.94
  5439.7  243.91  5441.7  243.99  5443.4  244.05    5449  243.99  5452.6  244.46
  5464.5  245.09  5473.7  245.26  5478.5  245.35  5482.3  245.42    5483  245.51
  5484.6  245.71  5484.7  245.71  5491.3  245.83  5500.6   246.1  5500.9   246.1
  5506.9  246.28  5512.3  246.43  5519.3  246.48  5529.5  246.56  5533.3  246.59
  5536.9  246.62  5545.9  246.69  5554.7  246.76  5555.8  246.77  5561.8  246.82
    5563  246.83  5566.2  246.85    5579  246.95  5579.9  246.96  5586.7  247.01
  5590.8  247.04  5597.3  247.09  5603.7  247.14    5620  247.27
BR D #Mann= 3
  4452.2     .15    4985     .05    5015     .15
BR D Banks=4985,5015
BC Design=,, 0 ,, 0 ,,,,,,
BC HTab HWMax=247.66
BC Use User HTab Curves=0
BC User HTab FreeFlow(D)= 0

Type RM Length L Ch R = 1 ,141253.3,707.8072,707.8072,707.8072
BEGIN DESCRIPTION:
Downstream Section of Bridge/Culvert/Weir
END DESCRIPTION:
XS GIS Cut Line= 3
2088991.87710071 632959.843583942089089.00808491 632428.84820353
2089276.94998926 631829.62213176
#Sta/Elev= 30
  4452.2   247.5  4598.5  245.32  4625.8  242.96  4645.6  242.42    4650  241.12
  4678.6  238.98    4688  237.02  4720.7  234.76  4782.3  234.68  4797.2  233.12
  4880.9  230.65  4916.4  230.92  4951.3  228.56  4974.4  228.23    4985  229.24
    4986  223.74    5014  223.74    5015  229.24  5116.3  228.25  5188.8  229.74
  5224.4   232.3  5236.4  231.98  5248.1  234.59    5287   234.3  5348.9  239.04
  5400.5  240.89  5419.4  243.11  5464.5  245.37  5512.3  246.71    5620  247.55
#Mann= 3 , 1 , 0
  4452.2     .15       0    4985     .05       0    5015     .15       0
#XS Ineff= 2 , 0
       0    4974   232.8    5026       0   232.8
Permanent Ineff=
       F       F
Bank Sta=4985,5015
XS Rating Curve= 0 ,0
Exp/Cntr=0.5,0.3

Type RM Length L Ch R = 1 ,140545.5,426.3043,426.3043,426.3043
BEGIN DESCRIPTION:
Black River 169.0
END DESCRIPTION:
XS GIS Cut Line= 3
2089955.45686436633014.4541372922089755.81484145632244.376334335
2089762.12490539 631556.62936561
#Sta/Elev= 30
  4195.2  247.05  4251.5  242.89  4363.2   238.2  4379.7  236.19  4431.8  236.05
  4458.7  232.16    4474  233.09  4544.6  230.77  4554.3  232.66  4587.3  234.01
  4596.3  231.77  4625.2     233  4693.4  229.17  4716.7  230.16  4755.8  227.97
  4980.1  228.17  4990.6  226.74  4991.7  224.72  5008.3  224.72  5009.3  226.72
  5019.1  228.32  5127.3  228.02  5155.9  228.53  5172.4   230.5  5334.5  233.43
  5354.8  235.37  5443.4  237.51  5453.7  239.37  5538.5  240.15  5678.5  246.86
#Mann= 3 , 1 , 0
  4195.2     .15       0  4990.6    .045       0  5009.3     .15       0
Bank Sta=4990.6,5009.3
XS Rating Curve= 0 ,0
Exp/Cntr=0.3,0.1

Type RM Length L Ch R = 1 ,140119.2,605.2061,605.2061,605.2061
BEGIN DESCRIPTION:
Black River 168.0
END DESCRIPTION:
XS GIS Cut Line= 3
2090368.56105022632853.2725040892090104.60837567631986.003716326
2090005.25736897631453.738323047
#Sta/Elev= 30
    4107  246.61    4123  245.46    4650  236.02  4677.8   233.2  4727.3  231.69
  4735.1  230.11  4844.6  226.71  4954.3  227.66  4990.7  226.38  4991.7  224.38
  5008.3  224.38  5009.3  226.38  5062.7  227.65  5142.6  227.35  5157.7  228.33
  5207.4   226.8  5230.7  229.53  5289.3  228.09  5317.9  228.89  5351.3  231.75
  5361.3  233.83  5386.7  235.04  5409.5  238.43  5448.8  239.33  5454.3  240.63
  5473.4  240.96  5516.8  244.45  5523.8  243.69  5544.5  244.87    5555  246.89
#Mann= 3 , 1 , 0
    4107     .12       0  4990.7     .04       0  5009.3     .12       0
Bank Sta=4990.7,5009.3
XS Rating Curve= 0 ,0
Exp/Cntr=0.3,0.1