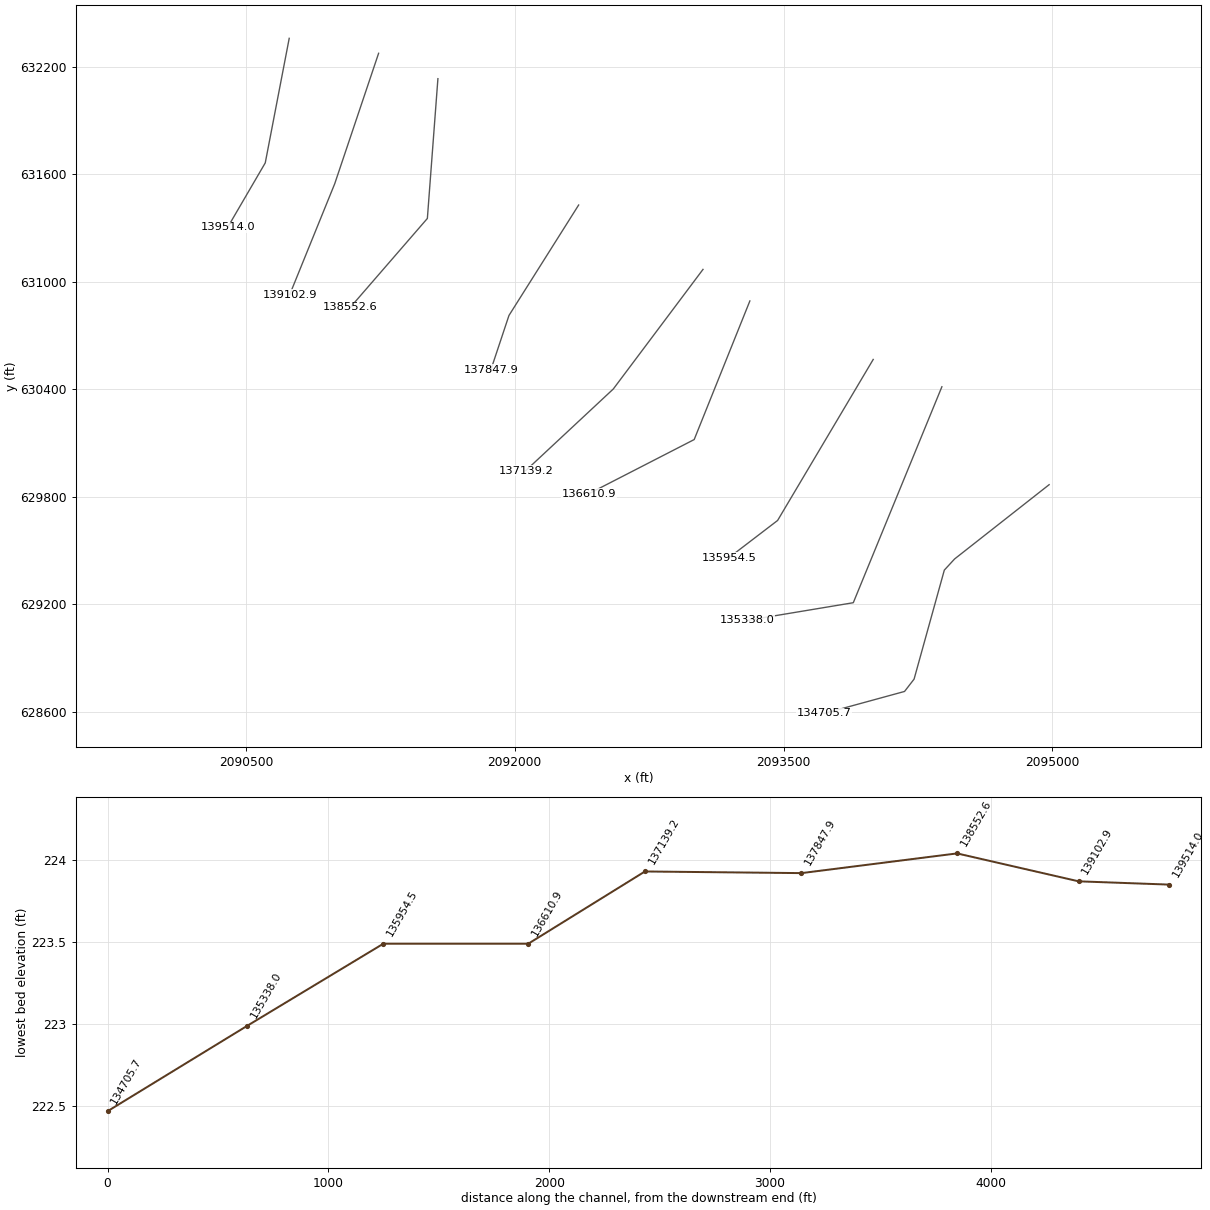
HEC-RAS study B4544BLACKRIVER.prj: B4544 BLACK RIVER SR1722

--- B4544BLACKRIVER.g02 (geometry) --- (continued)

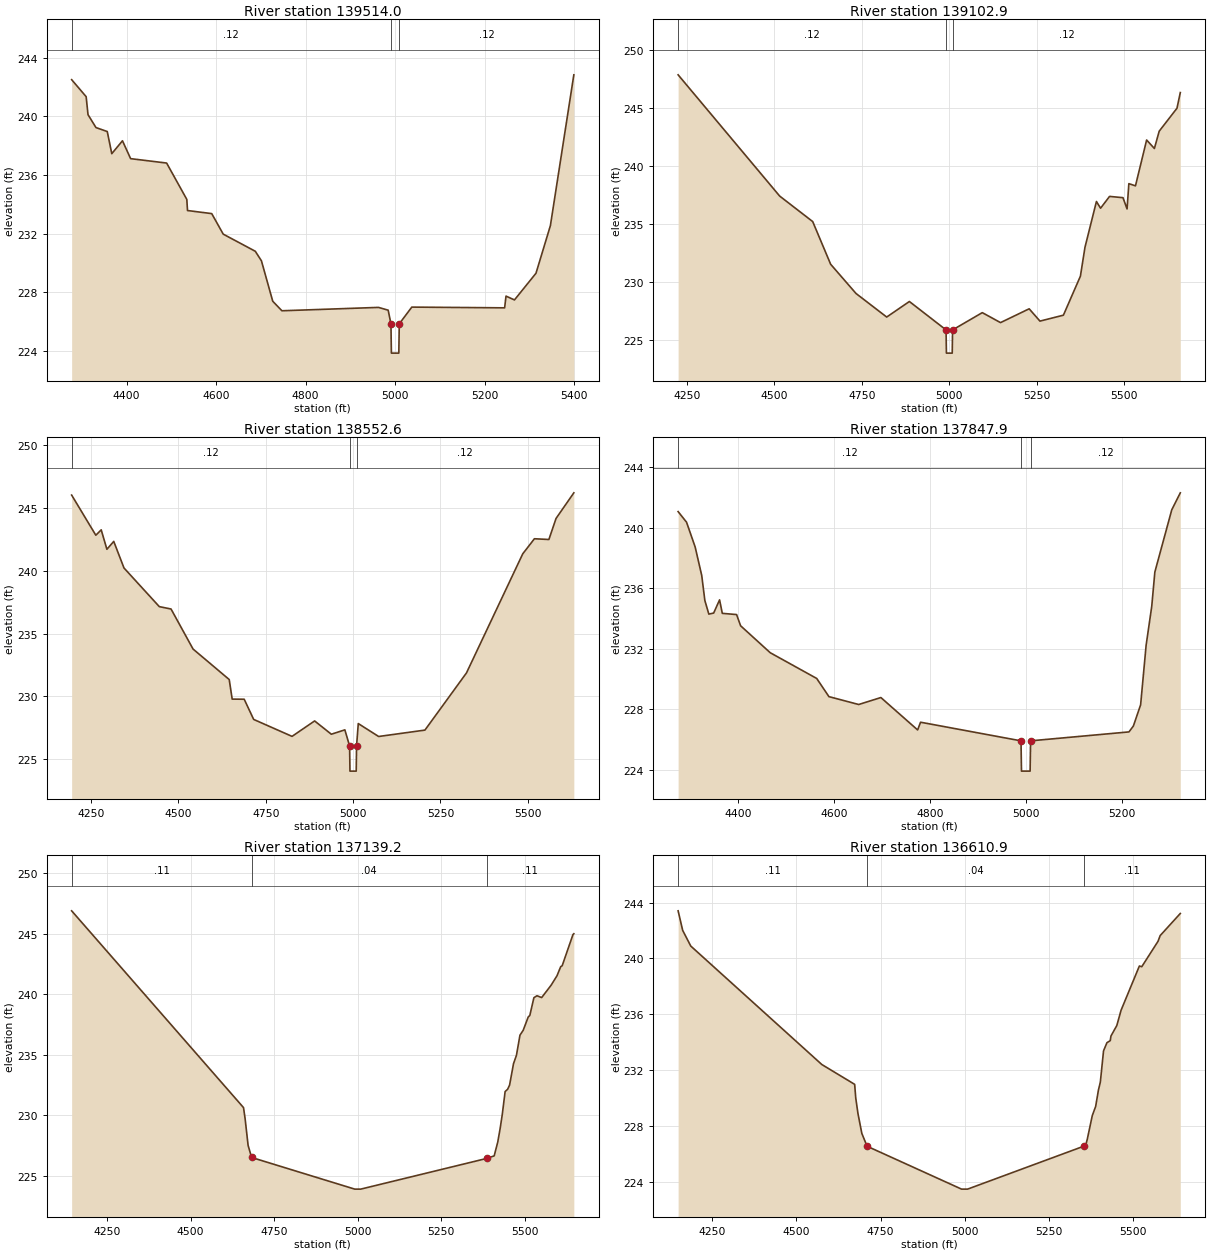
Type RM Length L Ch R = 1 ,139514.0,411.1042,411.1042,411.1042
BEGIN DESCRIPTION:
Black River 167.0
END DESCRIPTION:
XS GIS Cut Line= 3
2090742.04483461632357.8374840012090608.43348077 631663.04044384
 2090399.3413621631304.586811742
#Sta/Elev= 30
    4277  242.51  4309.4  241.35  4313.6  240.12  4331.4  239.24  4356.6  238.97
  4366.7  237.46  4390.6  238.34  4408.8  237.12  4489.3  236.82  4534.4  234.34
    4536  233.58  4590.1  233.37  4615.8  231.97  4687.5   230.8  4701.2  230.15
  4726.5  227.39    4747  226.74  4962.9  226.97  4984.5  226.78  4990.7  225.85
  4991.7  223.85  5008.3  223.85  5009.3  225.85  5037.3  226.99  5244.8  226.94
  5247.9  227.74  5266.8  227.48  5314.9   229.3  5347.1  232.55  5399.5  242.84
#Mann= 3 , 1 , 0
    4277     .12       0  4990.7     .04       0  5009.3     .12       0
Bank Sta=4990.7,5009.3
XS Rating Curve= 0 ,0
Exp/Cntr=0.3,0.1

Type RM Length L Ch R = 1 ,139102.9,550.3056,550.3056,550.3056
BEGIN DESCRIPTION:
Black River 166.0
END DESCRIPTION:
XS GIS Cut Line= 3
2091240.76988804632274.4866394332090995.98740773631546.779265802
2090745.13486592630928.813004143
#Sta/Elev= 30
  4225.2  247.86  4515.3  237.41  4609.7  235.21    4661  231.53  4733.5  229.01
  4821.1  226.98  4885.9  228.32  4990.7  225.87  4991.7  223.87  5008.3  223.87
  5009.3  225.87  5094.2  227.36  5146.3   226.5  5228.1  227.69    5259  226.63
  5325.9  227.14  5374.5   230.5  5387.6     233  5420.3  236.94  5432.1  236.36
  5457.8  237.38  5496.1  237.27  5507.8   236.3  5512.9  238.48  5531.8  238.29
  5563.7  242.24  5585.9  241.51  5599.6     243  5650.4  244.98  5659.9  246.33
#Mann= 3 , 1 , 0
  4225.2     .12       0  4990.7     .04       0  5009.3     .12       0
Bank Sta=4990.7,5009.3
XS Rating Curve= 0 ,0
Exp/Cntr=0.3,0.1

Type RM Length L Ch R = 1 ,138552.6,704.7071,704.7071,704.7071
BEGIN DESCRIPTION:
Black River 165.0
END DESCRIPTION:
XS GIS Cut Line= 3
2091571.59324017632132.8752045292091512.73264375 631352.99730227
2091083.54829496630857.782284411
#Sta/Elev= 30
  4194.4  246.04  4263.6  242.84    4279  243.27  4295.3  241.72  4314.9  242.35
  4344.2  240.23  4445.3  237.15  4478.9  236.96  4541.9  233.77  4645.4  231.34
  4653.9  229.78  4688.3  229.77  4715.4  228.16  4825.2  226.81  4889.9  228.04
  4937.7  226.98  4976.4  227.33    4990  226.04    4991  224.04  5008.9  224.04
  5009.9  226.04  5014.8  227.83  5073.1   226.8  5205.6  227.31  5324.6  231.87
  5485.6  241.36    5519  242.56  5560.4   242.5  5580.9  244.18  5631.8  246.22
#Mann= 3 , 1 , 0
  4194.4     .12       0    4990     .04       0  5009.9     .12       0
Bank Sta=4990,5009.9
XS Rating Curve= 0 ,0
Exp/Cntr=0.3,0.1

Type RM Length L Ch R = 1 ,137847.9,708.7072,708.7072,708.7072
BEGIN DESCRIPTION:
Black River 163.0
END DESCRIPTION:
XS GIS Cut Line= 3
2092356.70119542631427.998062229 2091967.9572564630811.871819215
2091867.01623359630508.848748777
#Sta/Elev= 30
  4274.5  241.06  4292.1  240.36  4310.1  238.72  4323.8  236.84  4330.3  235.19
  4338.6  234.29  4348.7  234.36    4361  235.23  4366.7  234.34  4396.5  234.26
  4404.9  233.52  4466.7  231.74  4563.7  230.04  4589.2  228.84  4651.3  228.32
  4697.6  228.78  4774.3  226.64  4780.4  227.15    4990  225.92    4991  223.92
    5009  223.92    5010  225.92  5215.3  226.51  5224.5   226.9  5239.6   228.3
  5251.1  232.24  5262.8   234.8  5269.3  237.07  5304.6  241.18  5322.4   242.3
#Mann= 3 , 1 , 0
  4274.5     .12       0    4990     .04       0    5010     .12       0
Bank Sta=4990,5010
XS Rating Curve= 0 ,0
Exp/Cntr=0.3,0.1

Type RM Length L Ch R = 1 ,137139.2,528.3054,528.3054,528.3054
BEGIN DESCRIPTION:
Black River 162.0
END DESCRIPTION:
XS GIS Cut Line= 3
2093050.38822433631068.8744233422092549.94315348630401.617662238
2092061.70820635629946.373049387
#Sta/Elev= 30
  4144.6  246.87  4658.5  230.65  4663.2  229.75  4672.2  227.54  4682.7  226.54
  4991.1  223.93    5009  223.93  5385.7  226.46    5408  226.67  5418.8  227.82
  5425.8  228.92  5432.2  230.08  5440.7  231.97  5448.2  232.16  5454.1  232.51
  5465.8  234.27  5474.6  234.96  5485.1  236.62  5494.7  237.02  5509.7  238.11
  5514.6  238.25  5526.8  239.71  5535.9  239.87    5550  239.72  5578.3  240.74
  5595.9  241.52    5607  242.27  5611.3  242.34  5643.7  244.92  5646.2  244.98
#Mann= 3 , 1 , 0
  4144.6     .11       0  4682.7     .04       0  5385.7     .11       0
Bank Sta=4682.7,5385.7
XS Rating Curve= 0 ,0
Exp/Cntr=0.3,0.1

Type RM Length L Ch R = 1 ,136610.9,656.4067,656.4067,656.4067
BEGIN DESCRIPTION:
Black River 161.0
END DESCRIPTION:
XS GIS Cut Line= 3
2093311.87087385630892.882640072 2093001.2277262630119.564804285
2092414.14177745629817.941748033
#Sta/Elev= 30
  4148.1  243.41  4161.7  242.01  4185.7  240.89  4575.4  232.41  4673.1  230.99
  4676.3  230.02  4682.8  228.92  4694.4  227.48    4710  226.56    4991  223.49
  5008.9  223.49  5356.5  226.58  5359.5  226.58  5364.8  227.05  5379.7  228.75
  5389.8  229.41    5398  230.58  5403.7  231.15  5413.1  233.36  5413.8  233.42
  5423.3  233.97  5433.2  234.12  5435.3  234.45  5452.7   235.2  5465.3  236.29
  5519.8  239.46  5526.9  239.41  5575.3  241.23  5581.7  241.64  5641.5  243.22
#Mann= 3 , 1 , 0
  4148.1     .11       0    4710     .04       0  5356.5     .11       0
Bank Sta=4710,5356.5
XS Rating Curve= 0 ,0
Exp/Cntr=0.3,0.1

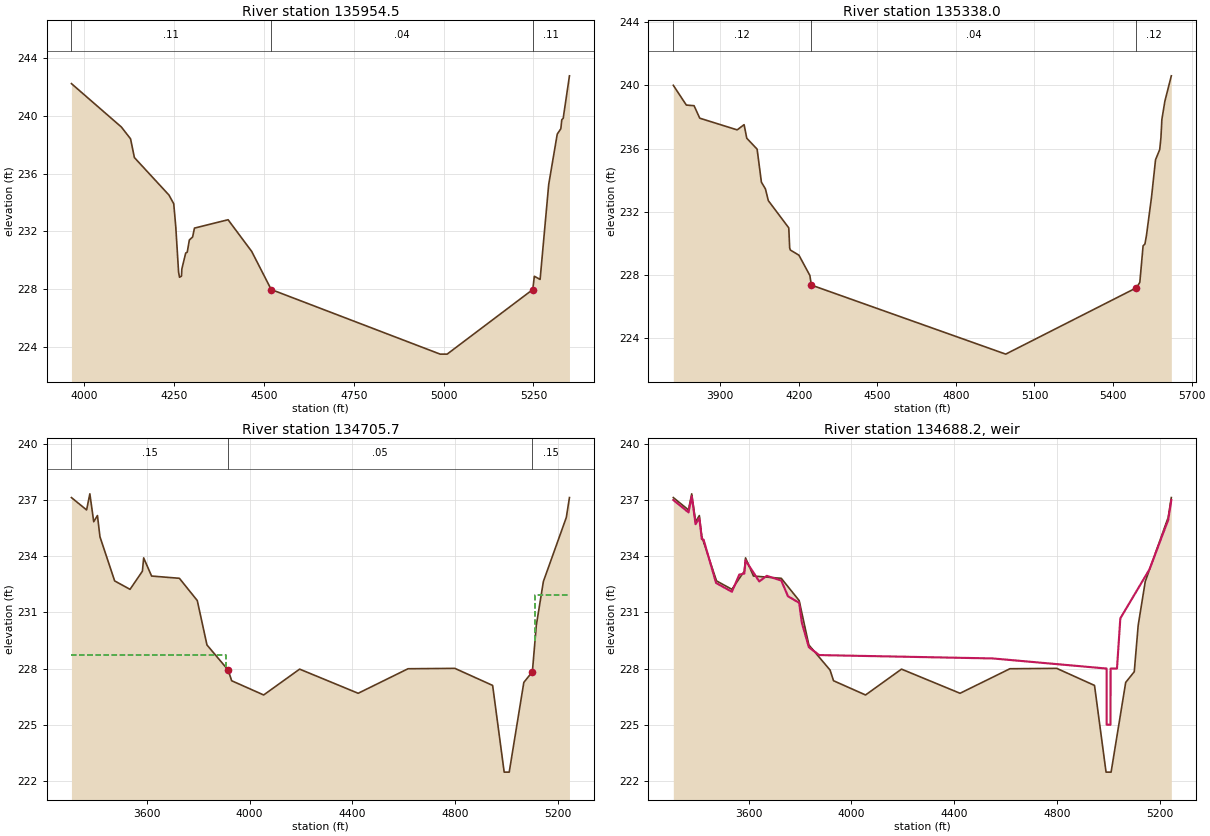
Type RM Length L Ch R = 1 ,135954.5,616.5062,616.5062,616.5062
BEGIN DESCRIPTION:
Black River 160.0
END DESCRIPTION:
XS GIS Cut Line= 3
2093999.93784582630566.529333236 2093466.6124418629668.290231661
2093195.03969004629460.618127384
#Sta/Elev= 30
  3963.8  242.25  4102.8  239.24  4128.4  238.42  4139.1  237.12  4235.4  234.52
  4248.6  233.92  4254.2  232.35  4262.1  229.18  4264.7  228.82  4270.2   228.9
  4271.1  229.39  4281.9   230.5  4286.2  230.56  4292.1  231.41  4301.1  231.61
  4306.3  232.23  4399.9  232.81  4465.7  230.61    4520  227.97  4990.3  223.49
  5009.8  223.49  5248.2  227.97  5252.5  228.89  5268.6  228.67  5292.5  235.25
  5316.3  238.75  5326.3  239.12  5328.9  239.74  5332.9  239.85  5350.3  242.79
#Mann= 3 , 1 , 0
  3963.8     .11       0    4520     .04       0  5248.2     .11       0
Bank Sta=4520,5248.2
XS Rating Curve= 0 ,0
Exp/Cntr=0.3,0.1

Type RM Length L Ch R = 1 ,135338.0,632.3064,632.3064,632.3064
BEGIN DESCRIPTION:
Black River 159.0
END DESCRIPTION:
XS GIS Cut Line= 3
2094383.02172749630414.1477892022093888.83672007629209.475582635
2093298.04073372629111.174586582
#Sta/Elev= 30
  3721.4     240  3771.1  238.75  3800.6  238.71  3822.3  237.92  3965.1  237.18
  3991.6  237.51  4001.8  236.65  4041.3  235.96  4057.7  233.87  4073.1  233.44
  4084.1   232.7  4162.1  230.98  4165.6  229.71    4168  229.58  4200.9  229.25
  4242.6  227.97  4248.3  227.36  4990.2  222.99  5489.3  227.19  5502.1  227.53
  5514.6  229.84  5521.6  229.96  5527.4  230.49  5546.9  232.94  5562.1  235.29
    5578  235.93  5582.7  236.68  5586.3  237.84  5597.8     239  5622.4   240.6
#Mann= 3 , 1 , 0
  3721.4     .12       0  4248.3     .04       0  5489.3     .12       0
Bank Sta=4248.3,5489.3
XS Rating Curve= 0 ,0
Exp/Cntr=0.3,0.1

Type RM Length L Ch R = 1 ,134705.7,217.5022,217.5022,217.5022
BEGIN DESCRIPTION:
Upstream Section of Bridge/Culvert/Weir
END DESCRIPTION:
XS GIS Cut Line= 6
2094981.34779014629867.9122543682094454.03244702629453.588056151
 2094396.6218653629391.347425486  2094227.930156628783.181263129
2094174.65961622628714.3805659932093727.38508413628592.099326955
#Sta/Elev= 30
    3307  237.13    3366  236.47  3378.6  237.33  3393.7  235.84  3408.2  236.17
  3417.9  235.04  3475.1  232.68  3534.9  232.23  3583.1   233.2  3587.9  233.91
  3618.8  232.94  3726.9  232.82  3796.5  231.63  3834.2  229.26  3916.7  227.92
  3930.2  227.35  4054.7  226.59  4194.6  227.97  4422.3  226.68  4616.2  227.99
  4798.4  228.01  4945.3   227.1  4990.2  222.47  5009.8  222.47  5066.6  227.26
  5099.9  227.83  5115.2  230.31  5142.7  232.65  5231.9  236.07  5244.1  237.13
#Mann= 3 , 1 , 0
    3307     .15       0  3916.7     .05       0  5099.9     .15       0
#XS Ineff= 2 , 0
       0  3906.7  228.71  5109.9       0  231.95
Permanent Ineff=
       F       F
Bank Sta=3916.7,5099.9
XS Rating Curve= 0 ,0
Exp/Cntr=0.5,0.3

Type RM Length L Ch R = 5 ,134688.2,,,
BEGIN DESCRIPTION:
Pope Lake Dam TOR
Structure ID: Pope Lake Dam
Approximate Survey Structure
END DESCRIPTION:
IW Pilot Flow=0
#Inline Weir SE= 30
    3307     237    3366  236.34  3378.6   237.2  3393.7  235.71  3408.2  236.04
  3417.9  234.91  3424.8  234.88  3473.3  232.57  3534.9   232.1  3563.7  233.02
  3583.1  233.07  3587.9  233.78  3641.2  232.65  3670.6  232.95  3726.9   232.7
    3753  231.86  3796.5  231.51  3806.8  230.45  3834.2  229.14  3874.4  228.72
  4549.9  228.54  4992.3     228  4992.5     225  5007.5     225  5007.8     228
  5032.7     228  5045.7  230.68  5159.2   233.3  5231.9  235.94  5244.1     237
IW Dist,WD,Coef,Skew,MaxSub,Min_El,Is_Ogee,SpillHt,DesHd
10,15,3,0,0.95,, 0 ,,,1,1,