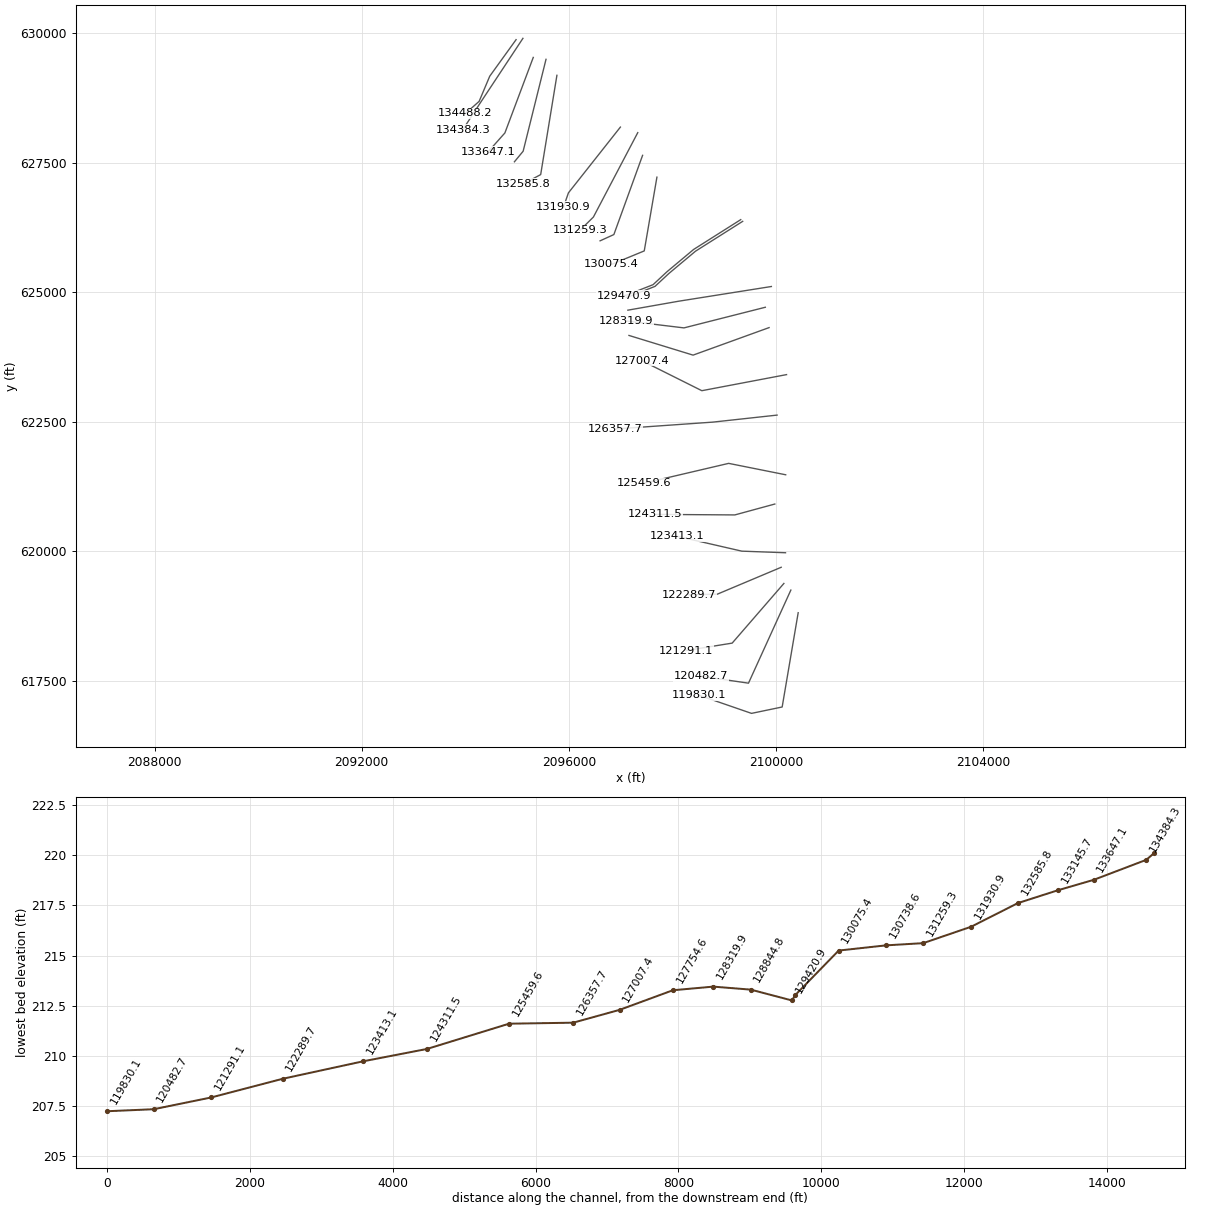
HEC-RAS study B4544BLACKRIVER.prj: B4544 BLACK RIVER SR1722

--- B4544BLACKRIVER.g02 (geometry) --- (continued)

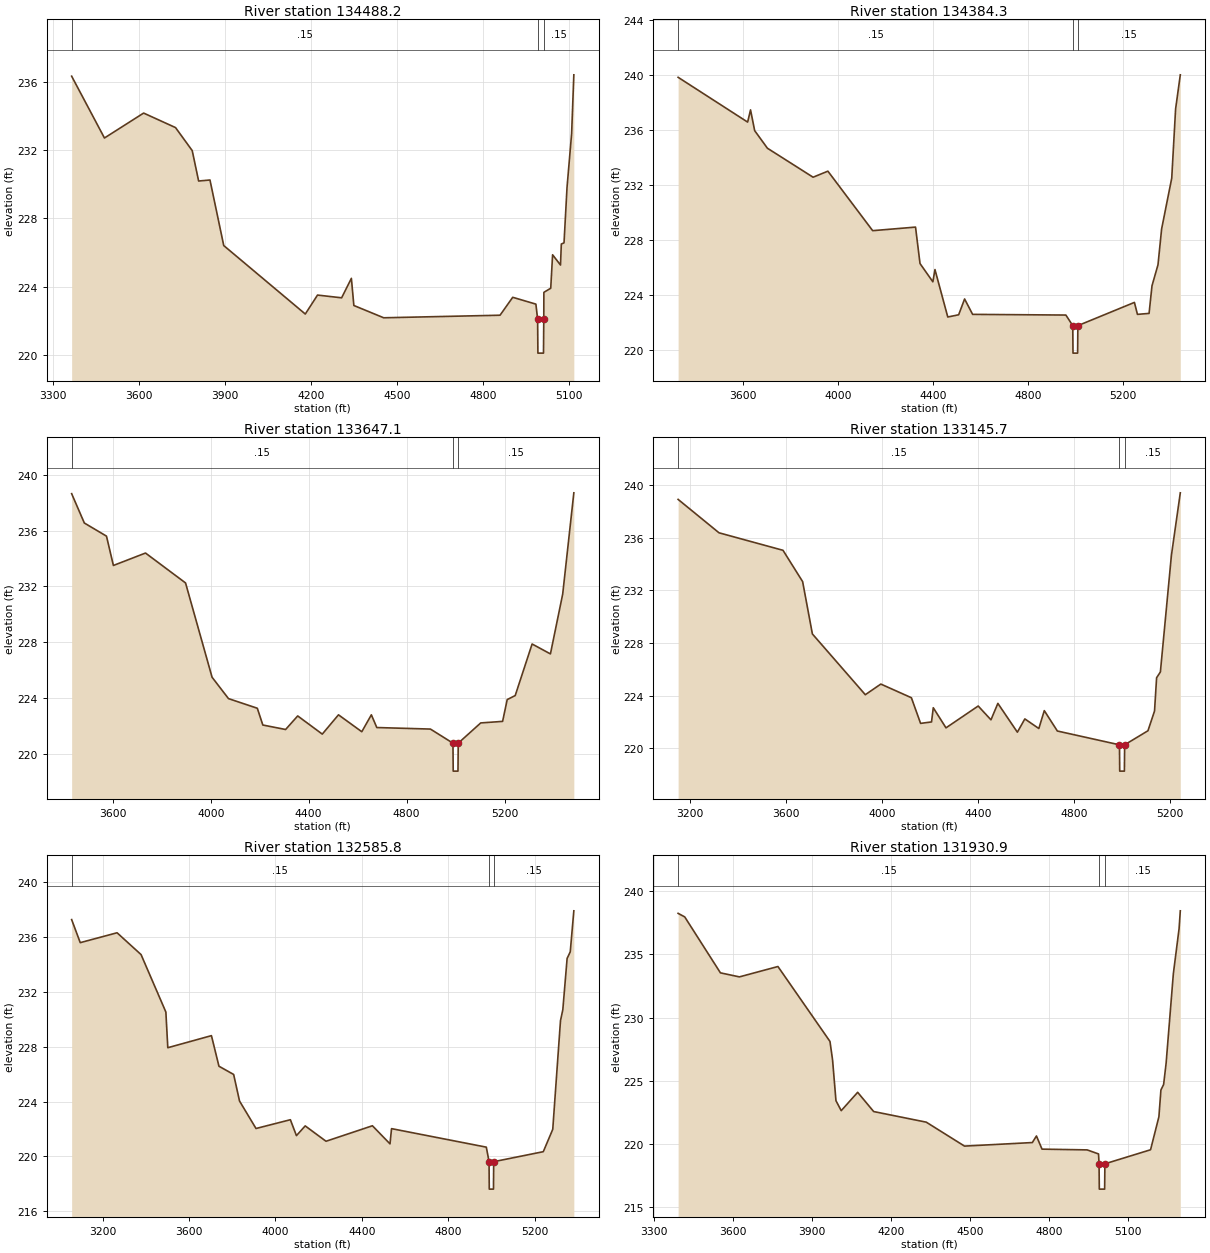
Type RM Length L Ch R = 1 ,134488.2,103.9011,103.9011,103.9011
BEGIN DESCRIPTION:
Pope Lake Dam DS
END DESCRIPTION:
XS GIS Cut Line= 4
2094980.11777768629875.9223355322094471.48262384629170.495187659
2094266.98055168628684.8002662652094002.68787369628450.877896002
#Sta/Elev= 30
  3365.9  236.32  3480.2   232.7  3616.7  234.16  3727.8  233.31    3786  231.96
  3808.3  230.18  3847.8  230.24  3895.8   226.4  4179.9  222.39  4222.5   223.5
  4306.5  223.34  4340.5  224.48  4349.1  222.89  4453.1  222.17  4858.4  222.32
  4902.6  223.37  4983.3  222.97  4989.3   222.1  4990.3   220.1  5009.8   220.1
  5010.8   222.1  5011.1  223.66    5035   223.9  5041.5  225.86    5069  225.26
  5071.9  226.49  5081.3  226.56  5091.8  229.81  5107.8  232.96  5115.5   236.4
#Mann= 3 , 1 , 0
  3365.9     .15       0  4989.3     .05       0  5010.8     .15       0
Bank Sta=4989.3,5010.8
XS Rating Curve= 0 ,0
Exp/Cntr=0.3,0.1

Type RM Length L Ch R = 1 ,134384.3,737.2075,737.2075,737.2075
BEGIN DESCRIPTION:
Black River 157.0
END DESCRIPTION:
XS GIS Cut Line= 3
2095112.35911764629901.5325950322094286.95075403628652.129935226
2093948.36732327628134.074685935
#Sta/Elev= 30
  3326.1  239.85  3619.1  236.59  3631.3  237.48  3648.7  235.97  3702.4  234.69
  3894.9  232.58  3957.3  233.02    4146  228.69  4326.6  228.95  4345.5   226.3
  4399.6  224.97  4408.5  225.86  4462.5  222.41  4508.4  222.57  4533.4  223.72
  4567.2   222.6  4960.2  222.55  4989.2  221.78  4990.2  219.78  5009.7  219.78
  5010.7  221.78    5249  223.47  5261.8   222.6  5310.8  222.67  5323.1  224.68
  5348.4  226.21  5363.7  228.82  5406.3  232.51  5422.6  237.55  5442.4  240.03
#Mann= 3 , 1 , 0
  3326.1     .15       0  4989.2    .046       0  5010.7     .15       0
Bank Sta=4989.2,5010.7
XS Rating Curve= 0 ,0
Exp/Cntr=0.3,0.1

Type RM Length L Ch R = 1 ,133647.1,501.4051,501.4051,501.4051
BEGIN DESCRIPTION:
Black River 156.0
END DESCRIPTION:
XS GIS Cut Line= 3
2095311.90113953629532.9788605932094764.03558818628074.704084351
2094436.28226716627706.530353762
#Sta/Elev= 30
  3432.2  238.64    3484  236.54  3574.4   235.6  3602.7   233.5  3733.8  234.39
  3897.3  232.25  4005.6   225.5  4072.7  223.97  4190.4  223.28  4212.9  222.08
  4305.9  221.76  4355.3  222.73  4455.7  221.43  4521.8  222.81    4617   221.6
  4656.1  222.81  4678.3   221.9  4897.4  221.79  4989.3  220.78  4990.3  218.78
  5009.8  218.78  5010.8  220.78  5102.7  222.23    5192  222.34  5210.8   223.9
  5243.5  224.19  5312.5  227.88  5387.3  227.17  5437.4  231.45  5482.9   238.7
#Mann= 3 , 1 , 0
  3432.2     .15       0  4989.3    .046       0  5010.8     .15       0
Bank Sta=4989.3,5010.8
XS Rating Curve= 0 ,0
Exp/Cntr=0.3,0.1

Type RM Length L Ch R = 1 ,133145.7,559.9057,559.9057,559.9057
BEGIN DESCRIPTION:
Black River 155.0
END DESCRIPTION:
XS GIS Cut Line= 3
2095558.01363332629496.428490239 2095116.5991606627722.140511935
2094948.32745556627518.008443528
#Sta/Elev= 30
  3149.8  238.92  3320.3  236.38  3586.9  235.05  3668.7  232.67  3709.4  228.69
    3930  224.07  3994.6  224.88    4122  223.84  4160.3  221.89  4205.9     222
  4213.2  223.08  4266.2  221.55  4400.4  223.21  4453.6  222.16  4482.4  223.41
  4563.7  221.22  4594.8  222.23  4653.1   221.5  4675.9  222.86  4730.3  221.31
  4989.2  220.26  4990.2  218.26  5009.7  218.26  5010.7  220.26  5107.9  221.33
  5135.3  222.83  5143.9  225.36  5159.7   225.8  5205.6  234.66  5242.7  239.42
#Mann= 3 , 1 , 0
  3149.8     .15       0  4989.2    .046       0  5010.7     .15       0
Bank Sta=4989.2,5010.7
XS Rating Curve= 0 ,0
Exp/Cntr=0.3,0.1

Type RM Length L Ch R = 1 ,132585.8,654.9066,654.9066,654.9066
BEGIN DESCRIPTION:
Black River 154.0
END DESCRIPTION:
XS GIS Cut Line= 3
2095768.59576708629187.8553635642095455.06259015627270.855939209
2095118.23917722 627090.12410791
#Sta/Elev= 30
    3057  237.27  3096.8  235.59  3267.3  236.31  3378.3  234.72  3493.2  230.53
  3502.1  227.93  3704.1  228.81  3738.9  226.58  3806.9  225.98  3834.2  224.04
  3910.4  222.04  4069.5  222.68  4097.6  221.52  4138.1  222.23  4234.5  221.11
  4449.3  222.24  4530.7  220.92  4537.8  222.03  4976.6  220.68  4989.2  219.62
  4990.2  217.62  5009.7  217.62  5010.7  219.62  5240.3  220.35  5284.1  221.98
  5319.9   229.9  5330.7   230.7  5350.6  234.44  5365.1  234.92  5381.7  237.91
#Mann= 3 , 1 , 0
    3057     .15       0  4989.2    .046       0  5010.7     .15       0
Bank Sta=4989.2,5010.7
XS Rating Curve= 0 ,0
Exp/Cntr=0.3,0.1

Type RM Length L Ch R = 1 ,131930.9,671.6068,671.6068,671.6068
BEGIN DESCRIPTION:
Black River 153.0
END DESCRIPTION:
XS GIS Cut Line= 3
2096994.09818471628187.8252305722095990.95802021626918.292366793
2095896.24706053626646.209609864
#Sta/Elev= 30
  3391.2  238.23  3416.3  237.95  3551.8  233.53  3623.8  233.21  3770.1  234.03
  3967.6  228.11  3977.5  226.64  3990.3  223.43  4010.3  222.64  4072.7  224.09
  4133.4  222.57  4333.2  221.73  4478.2  219.84  4735.7  220.12  4751.3  220.64
  4772.4   219.6  4943.7  219.54  4986.9  219.22  4988.9  218.44  4989.9  216.44
  5010.1  216.44  5011.1  218.44  5184.4  219.55  5216.1  222.16  5223.7  224.27
    5234  224.71  5243.4  226.38  5270.9  233.46  5292.7  237.03  5297.3  238.43
#Mann= 3 , 1 , 0
  3391.2     .15       0  4988.9    .046       0  5011.1     .15       0
Bank Sta=4988.9,5011.1
XS Rating Curve= 0 ,0
Exp/Cntr=0.3,0.1

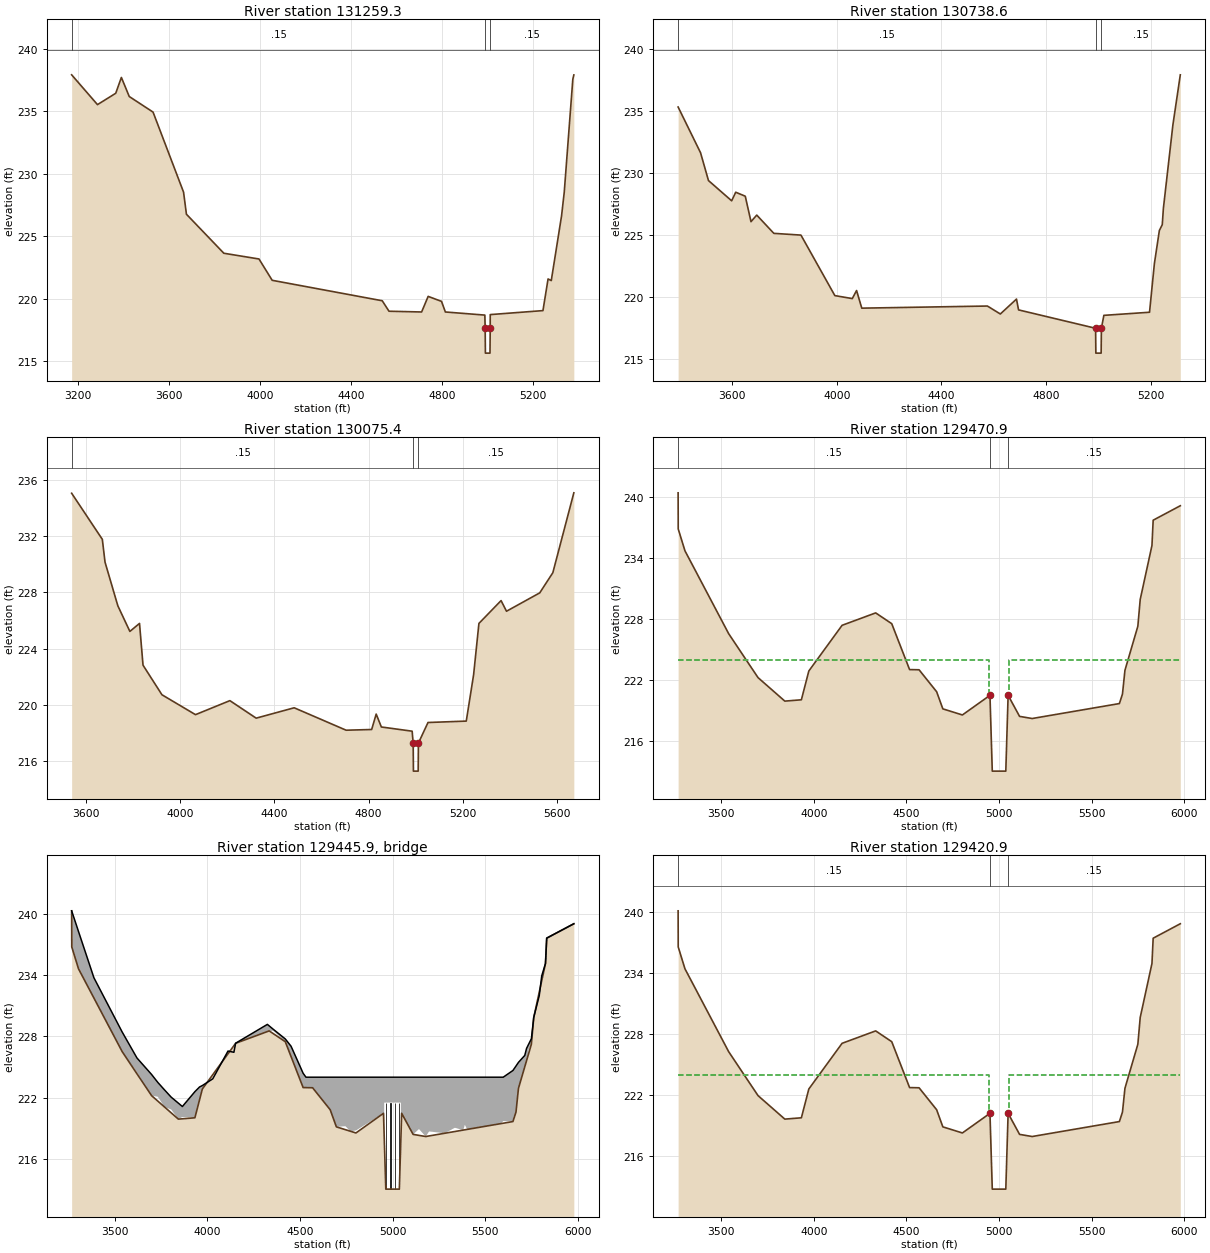
Type RM Length L Ch R = 1 ,131259.3,520.7053,520.7053,520.7053
BEGIN DESCRIPTION:
Black River 152.0
END DESCRIPTION:
XS GIS Cut Line= 3
2097329.47158294628080.8341464652096473.26290725626451.497636908
2096211.67025661626193.215019811
#Sta/Elev= 30
  3170.6  237.94  3284.2  235.55  3364.4  236.46  3389.3  237.73  3423.9   236.2
  3528.6  234.95  3662.7  228.53  3675.3  226.76  3839.8  223.63  3994.4  223.17
  4052.4  221.46  4536.3  219.82    4566  218.98  4709.5  218.92  4738.2  220.17
    4797  219.77  4813.9  218.92  4987.5  218.67  4988.9  217.62  4989.9  215.62
  5010.1  215.62  5011.1  217.62  5011.2  218.71    5243  219.03  5265.5  221.57
  5279.6  221.44  5324.8  226.63  5336.7  228.54  5374.3  237.58  5378.8  237.93
#Mann= 3 , 1 , 0
  3170.6     .15       0  4988.9    .046       0  5011.1     .15       0
Bank Sta=4988.9,5011.1
XS Rating Curve= 0 ,0
Exp/Cntr=0.3,0.1

Type RM Length L Ch R = 1 ,130738.6,663.2067,663.2067,663.2067
BEGIN DESCRIPTION:
Black River 151.0
END DESCRIPTION:
XS GIS Cut Line= 3
2097422.68252742627642.3997039462096868.13690838626113.034207364
2096602.28421458625991.972980689
#Sta/Elev= 30
  3393.7  235.32  3479.4  231.64  3509.7   229.4  3598.3  227.77  3613.8  228.46
  3650.3  228.14  3672.2  226.09  3694.1  226.62  3759.5  225.15  3863.1  225.01
  3992.6  220.14  4059.2   219.9  4075.6  220.55  4095.5  219.13  4575.5   219.3
  4624.9  218.66  4686.6  219.86  4694.6  218.99  4988.9  217.51  4989.9  215.51
  5010.1  215.51  5011.1  217.51  5020.5  218.55    5195   218.8  5213.6  222.72
  5232.6  225.38  5243.7  225.85    5248  227.17  5284.3  233.88  5312.6  237.91
#Mann= 3 , 1 , 0
  3393.7     .15       0  4988.9    .046       0  5011.1     .15       0
Bank Sta=4988.9,5011.1
XS Rating Curve= 0 ,0
Exp/Cntr=0.3,0.1

Type RM Length L Ch R = 1 ,130075.4,604.5061,604.5061,604.5061
BEGIN DESCRIPTION:
Black River 150.0
END DESCRIPTION:
XS GIS Cut Line= 3
2097699.41533147627221.3354374342097454.80285289625797.141006517
2096820.40642475625535.668357097
#Sta/Elev= 30
  3539.5  235.08  3669.7  231.79  3681.2  230.16  3735.5  227.05  3786.6  225.22
  3827.5  225.79  3842.4  222.81  3922.7   220.7  4065.1  219.28    4211  220.28
  4322.6  219.03  4483.9  219.77  4704.3  218.17  4812.7  218.22  4831.9  219.32
  4853.9   218.4  4984.5   218.1  4988.9  217.25  4989.9  215.25  5010.1  215.25
  5011.1  217.25  5051.8  218.72  5214.2  218.82  5245.3  222.12  5267.9  225.79
  5361.9  227.42  5384.9  226.66    5526  227.97  5581.6  229.41  5670.7  235.11
#Mann= 3 , 1 , 0
  3539.5     .15       0  4988.9    .046       0  5011.1     .15       0
Bank Sta=4988.9,5011.1
XS Rating Curve= 0 ,0
Exp/Cntr=0.5,0.3

Type RM Length L Ch R = 1 ,129470.9,50.0005,50.0005,50.0005
BEGIN DESCRIPTION:
Upstream Section of Bridge/Culvert/Weir
END DESCRIPTION:
XS GIS Cut Line= 6
2099317.62172825626400.947124696 2098408.3225146625825.681295707
2097893.41729723625395.0269320212097625.04457789625145.374402371
2097106.50932374624941.4523360922097068.46893829624933.542255942
#Sta/Elev= 30
  3268.3  240.39  3268.9  236.84  3305.3  234.69    3541  226.55  3699.5  222.23
  3844.1  219.92  3933.4  220.05  3973.6  222.88  4153.1  227.37  4334.3  228.59
    4421  227.53  4517.3  223.02  4568.5     223  4663.4  220.84  4696.7  219.16
  4802.3  218.56    4951  220.49  4963.5  213.04  5036.5  213.04    5049  220.49
  5110.8  218.42  5178.8  218.21  5649.4  219.68    5666  220.61  5679.4  222.95
    5749  227.28  5761.8  229.91  5825.1  235.21  5831.7   237.7  5978.1  239.12
#Mann= 3 , 1 , 0
  3268.3     .15       0    4951     .05       0    5049     .15       0
#XS Ineff= 2 , 0
       0    4944     224    5056       0     224
Permanent Ineff=
       F       F
Bank Sta=4951,5049
XS Rating Curve= 0 ,0
Exp/Cntr=0.5,0.3

Type RM Length L Ch R = 3 ,129445.9,,,
BEGIN DESCRIPTION:
Langdon Road TOR
Structure ID: Langdon Road
Approximate Survey Structure
END DESCRIPTION:
Bridge Culvert--1,0,-1,-1, 0
Deck Dist Width WeirC Skew NumUp NumDn MinLoCord MaxHiCord MaxSubmerge Is_Ogee
10,30,2.6,0, 60, 60, , , 0.95, 0, 1,1,,
  3268.3  3268.9  3305.3  3388.5    3541  3620.7  3699.5  3733.1  3769.5  3805.3
  3844.1  3865.8  3933.4  3958.5  3973.6  4029.7    4112  4143.8  4153.1  4324.4
  4356.2    4421  4452.3  4517.3  4532.6  4568.5  4663.4  4696.7  4745.8  4772.7
    4951 4954.91    4955 5044.89    5045    5049  5110.8  5142.6  5178.8  5196.9
  5281.1    5336  5381.2    5390  5402.4  5585.1    5597  5649.4    5666  5679.4
  5713.3    5723    5735    5749  5761.8  5791.6  5804.9  5825.1  5831.7  5978.1
  240.35  240.32  238.32  233.77  228.44  225.89  224.27  223.49  222.75  222.04
  221.45  221.12  222.58  223.04  223.18  223.84  226.57  226.45  227.34  229.19
  228.71  227.76  227.04  224.39     224     224     224     224     224     224
     224     224     224     224     224     224     224     224     224     224
     224     224     224     224     224     224     224  224.66   225.1  225.46
  226.14  226.83  227.27  227.78  229.88  232.03  233.96  235.18  237.67  239.08
  240.35   236.8  234.65  231.78  226.51  224.47  222.19  222.08  220.91  220.83
  219.88  220.09  220.01  221.41  222.84  223.71  226.56  226.44  227.33  228.46
  228.56  227.49  226.07  222.98  222.89  222.96   220.8  219.12  219.18  218.43
  220.45  218.12   221.5   221.5  218.07  220.45  218.38   218.9  218.17  218.67
  218.27  219.03  218.74  219.32  218.84  219.06  219.69  219.64  220.57  222.91
  224.95  225.33  226.73  227.24  229.87  232.02  233.95  235.17  237.66  239.08
  3268.3  3268.9  3305.3  3388.5    3541  3620.7  3699.5  3733.1  3769.5  3805.3
  3844.1  3865.8  3933.4  3958.5  3973.6  4029.7    4112  4143.8  4153.1  4324.4
  4356.2    4421  4452.3  4517.3  4532.6  4568.5  4663.4  4696.7  4745.8  4772.7
    4951 4954.91    4955 5044.89    5045    5049  5110.8  5142.6  5178.8  5196.9
  5281.1    5336  5381.2    5390  5402.4  5585.1    5597  5649.4    5666  5679.4
  5713.3    5723    5735    5749  5761.8  5791.6  5804.9  5825.1  5831.7  5978.1
  240.35  240.32  238.32  233.77  228.44  225.89  224.27  223.49  222.75  222.04
  221.45  221.12  222.58  223.04  223.18  223.84  226.57  226.45  227.34  229.19
  228.71  227.76  227.04  224.39     224     224     224     224     224     224
     224     224     224     224     224     224     224     224     224     224
     224     224     224     224     224     224     224  224.66   225.1  225.46
  226.14  226.83  227.27  227.78  229.88  232.03  233.96  235.18  237.67  239.08
   240.1  236.55   234.4  231.53  226.26  224.22  221.94  221.83  220.66  220.58
  219.63  219.84  219.76  221.16  222.59  223.46  226.31  226.19  227.08  228.21
  228.31  227.24  225.82  222.73  222.64  222.71  220.55  218.87  218.93  218.18
   220.2  217.87  221.25  221.25  217.82   220.2  218.13  218.65  217.92  218.42
  218.02  218.78  218.49  219.07  218.59  218.81  219.44  219.39  220.32  222.66
   224.7  225.08  226.48  226.99  229.62  231.77   233.7  234.92  237.41  238.83
Pier Skew, UpSta & Num, DnSta & Num=  ,4966.3, 2 ,4966.3, 2 , 0 , 0 , 0 ,,
       1       1
     212   222.5
       1       1
  211.75  222.25
Pier Skew, UpSta & Num, DnSta & Num=  ,4988.8, 2 ,4988.8, 2 , 0 , 0 , 0 ,,
       1       1
     212   222.5
       1       1
  211.75  222.25
Pier Skew, UpSta & Num, DnSta & Num=  ,5011.3, 2 ,5011.3, 2 , 0 , 0 , 0 ,,
       1       1
     212   222.5
       1       1
  211.75  222.25
Pier Skew, UpSta & Num, DnSta & Num=  ,5033.8, 2 ,5033.8, 2 , 0 , 0 , 0 ,,
       1       1
     212   222.5
       1       1
  211.75  222.25
BR Coef= 1 , 1 , 0 ,1.25, 0 ,,,0.8,0,2,0,
WSPro=,,,, 1 ,,,, 0 ,,,, 0 ,,,,-1 ,-1 ,-1 , 0 , 0 , 0 , 0 , 0
BR U #Sta/Elev= 30
  3268.3  240.35  3268.9   236.8  3305.3  234.65    3541  226.51  3699.5  222.19
  3844.1  219.88  3933.4  220.01  3973.6  222.84  4153.1  227.33  4334.3  228.55
    4421  227.49  4517.3  222.98  4568.5  222.96  4663.4   220.8  4696.7  219.12
  4802.3  218.52    4951  220.45  4963.5     213  5036.5     213    5049  220.45
  5110.8  218.38  5178.8  218.17  5649.4  219.64    5666  220.57  5679.4  222.91
    5749  227.24  5761.8  229.87  5825.1  235.17  5831.7  237.66  5978.1  239.08
BR U #Mann= 3
  3268.3     .15    4951     .05    5049     .15
BR U Banks=4951,5049
BR D #Sta/Elev= 30
  3268.3   240.1  3268.9  236.55  3305.3   234.4    3541  226.26  3699.5  221.94
  3844.1  219.63  3933.4  219.76  3973.6  222.59  4153.1  227.08  4334.3   228.3
    4421  227.24  4517.3  222.73  4568.5  222.71  4663.4  220.55  4696.7  218.87
  4802.3  218.27    4951   220.2  4963.5  212.75  5036.5  212.75    5049   220.2
  5110.8  218.13  5178.8  217.92  5649.4  219.39    5666  220.32  5679.4  222.66
    5749  226.99  5761.8  229.62  5825.1  234.92  5831.7  237.41  5978.1  238.83
BR D #Mann= 3
  3268.3     .15    4951     .05    5049     .15
BR D Banks=4951,5049
BC Design=,, 0 ,, 0 ,,,,,,
BC HTab HWMax=240.39
BC Use User HTab Curves=0
BC User HTab FreeFlow(D)= 0

Type RM Length L Ch R = 1 ,129420.9,576.1058,576.1058,576.1058
BEGIN DESCRIPTION:
Downstream Section of Bridge/Culvert/Weir
END DESCRIPTION:
XS GIS Cut Line= 6
2099355.34211046626368.1167920362098446.04289681625792.860963149
2097931.13767944625362.206599463 2097662.7649601625112.554069812
2097144.22970595624908.632003534 2097106.1893205624900.721923384
#Sta/Elev= 30
  3268.3  240.11  3268.9  236.56  3305.3  234.41    3541  226.27  3699.5  221.95
  3844.1  219.64  3933.4  219.77  3973.6   222.6  4153.1  227.09  4334.3  228.31
    4421  227.25  4517.3  222.74  4568.5  222.72  4663.4  220.56  4696.7  218.88
  4802.3  218.28    4951  220.21  4963.5  212.76  5036.5  212.76    5049  220.21
  5110.8  218.14  5178.8  217.93  5649.4   219.4    5666  220.33  5679.4  222.67
    5749     227  5761.8  229.63  5825.1  234.93  5831.7  237.42  5978.1  238.84
#Mann= 3 , 1 , 0
  3268.3     .15       0    4951     .05       0    5049     .15       0
#XS Ineff= 2 , 0
       0    4944     224    5056       0     224
Permanent Ineff=
       F       F
Bank Sta=4951,5049
XS Rating Curve= 0 ,0
Exp/Cntr=0.5,0.3

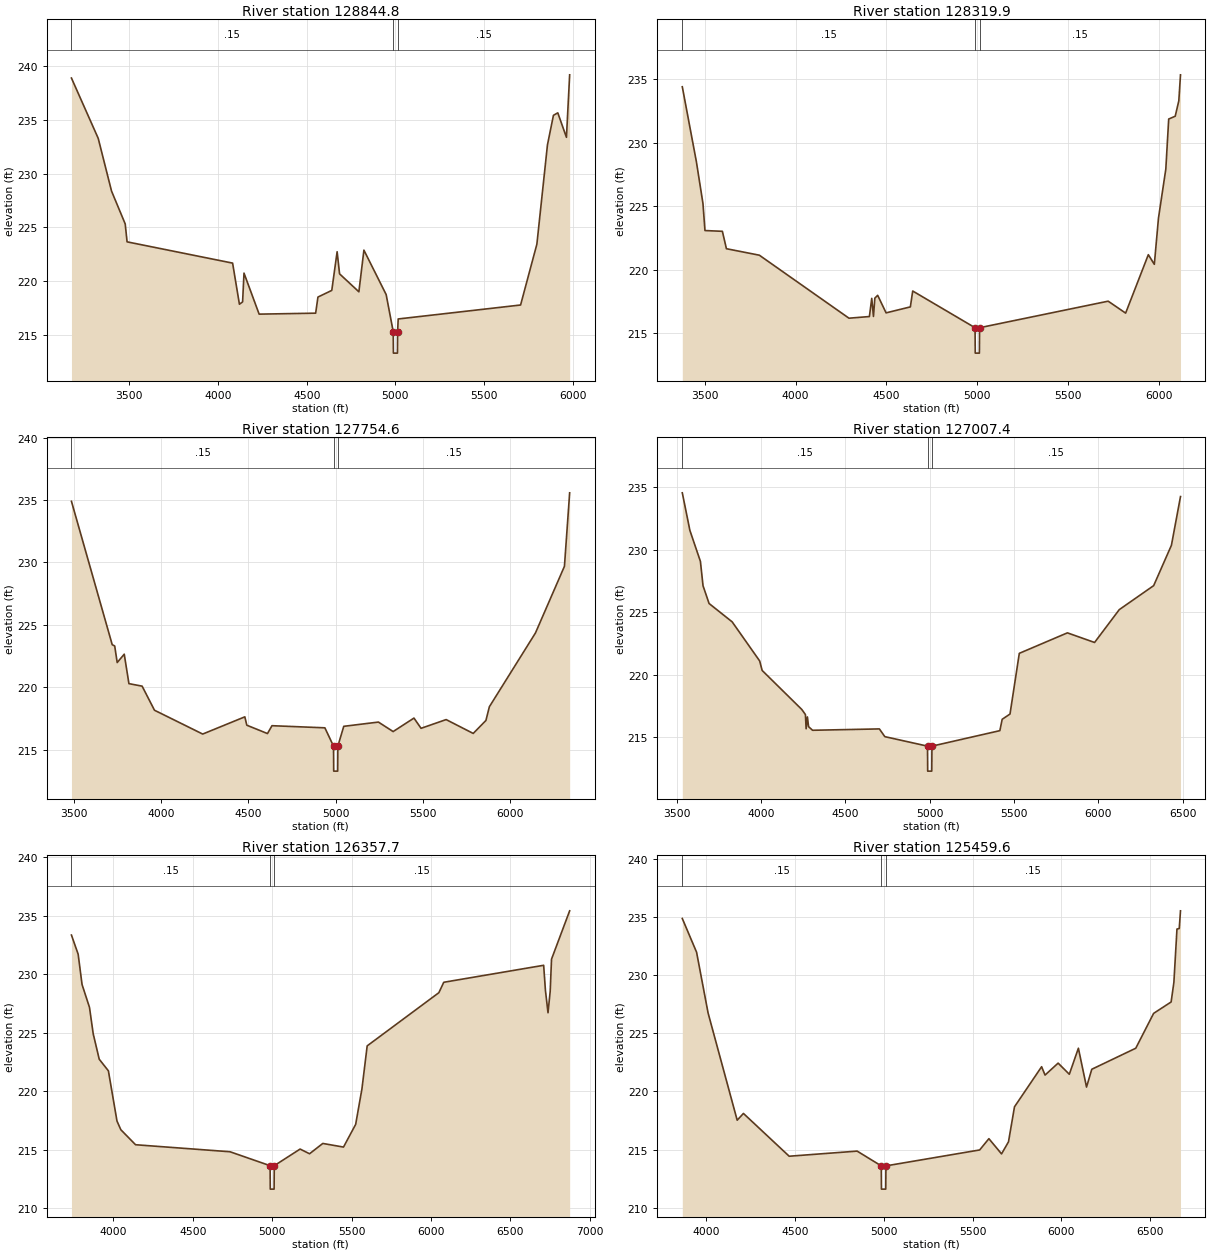
Type RM Length L Ch R = 1 ,128844.8,524.9053,524.9053,524.9053
BEGIN DESCRIPTION:
Black River 147.0
END DESCRIPTION:
XS GIS Cut Line= 3
2099909.11772169625110.0340442782098121.12960457624826.431170619
2097138.39964687624653.149414809
#Sta/Elev= 30
  3173.9  238.91  3324.7   233.3  3399.8  228.39  3476.9  225.33  3487.5  223.66
  4082.3  221.68  4120.7  217.85  4138.6  218.07  4146.5  220.75  4231.8  216.93
  4550.4  217.02  4563.3  218.52  4641.3  219.14  4671.4  222.74  4685.2  220.68
    4794  219.01  4822.4  222.89  4947.8  218.75  4987.6   215.3  4988.6   213.3
  5011.4   213.3  5012.4   215.3  5015.6  216.48  5705.5  217.78  5797.3  223.44
    5857  232.69  5890.7  235.44  5915.3  235.67    5964  233.39  5982.1  239.21
#Mann= 3 , 1 , 0
  3173.9     .15       0  4987.6    .045       0  5012.4     .15       0
Bank Sta=4987.6,5012.4
XS Rating Curve= 0 ,0
Exp/Cntr=0.3,0.1

Type RM Length L Ch R = 1 ,128319.9,565.3057,565.3057,565.3057
BEGIN DESCRIPTION:
Black River 146.0
END DESCRIPTION:
XS GIS Cut Line= 3
2099792.32653828624709.3299840692098221.37062028624310.895946861
2097109.00934907624445.147307188
#Sta/Elev= 30
  3376.8  234.42  3454.2  228.53  3490.5  225.23  3501.5   223.1  3597.3  223.04
  3619.6  221.67  3800.7  221.16  4293.8   216.2  4406.2  216.33  4419.1  217.76
  4428.6  216.34  4436.2  217.78  4451.8     218  4498.1  216.62  4631.6  217.09
  4644.5  218.34  4987.6  215.45  4988.6  213.45  5011.4  213.45  5012.4  215.45
  5719.9  217.54    5816   216.6  5940.9   221.2  5973.9  220.44  5996.7  224.08
  6037.1  227.94    6053  231.88  6088.8   232.1  6108.6  233.31  6117.9  235.36
#Mann= 3 , 1 , 0
  3376.8     .15       0  4987.6    .045       0  5012.4     .15       0
Bank Sta=4987.6,5012.4
XS Rating Curve= 0 ,0
Exp/Cntr=0.3,0.1

Type RM Length L Ch R = 1 ,127754.6,747.2076,747.2076,747.2076
BEGIN DESCRIPTION:
Black River 145.0
END DESCRIPTION:
XS GIS Cut Line= 3
2099864.91727382624316.4760034022098397.44240436623785.230620459
 2097159.6598623624165.074469298
#Sta/Elev= 30
  3485.5  234.89  3719.2   223.4  3733.4   223.3  3747.7  221.97  3788.1  222.64
  3814.9  220.28  3890.5  220.08  3961.4  218.15  4237.7  216.24  4479.2  217.62
  4490.5  216.95    4609  216.28  4634.9  216.91    4938  216.74  4987.6  215.27
  4988.6  213.27  5011.4  213.27  5012.4  215.27  5046.2  216.86  5244.8   217.2
  5329.2  216.44  5448.6  217.52  5489.2   216.7    5633   217.4  5788.2  216.29
    5861  217.33  5880.8  218.43  6144.9  224.34    6311  229.68  6340.9  235.57
#Mann= 3 , 1 , 0
  3485.5     .15       0  4987.6    .045       0  5012.4     .15       0
Bank Sta=4987.6,5012.4
XS Rating Curve= 0 ,0
Exp/Cntr=0.3,0.1

Type RM Length L Ch R = 1 ,127007.4,649.7066,649.7066,649.7066
BEGIN DESCRIPTION:
Black River 144.0
END DESCRIPTION:
XS GIS Cut Line= 3
2100201.92068857623408.8868070852098566.63411873623098.483661867
2097414.84244798623674.389497341
#Sta/Elev= 30
  3533.8  234.57  3578.8  231.56  3641.2  229.08  3656.7  227.13  3692.5  225.71
  3829.3  224.24  3992.3  221.11    4007  220.35  4241.6  217.23  4263.4  216.82
  4267.5  215.68  4275.1  216.63  4282.1  215.85  4305.7  215.56  4701.6  215.67
    4734  215.05  4986.9  214.29  4987.9  212.29  5012.1  212.29  5013.1  214.29
  5415.5  215.53  5429.3  216.44  5475.7  216.86  5530.8  221.72  5815.8  223.36
  5976.8  222.59  6123.3  225.22    6327  227.14  6432.2  230.37    6486  234.27
#Mann= 3 , 1 , 0
  3533.8     .15       0  4986.9    .045       0  5013.1     .15       0
Bank Sta=4986.9,5013.1
XS Rating Curve= 0 ,0
Exp/Cntr=0.3,0.1

Type RM Length L Ch R = 1 ,126357.7,898.1091,898.1091,898.1091
BEGIN DESCRIPTION:
Black River 143.0
END DESCRIPTION:
XS GIS Cut Line= 3
2100019.53884055622627.1588860812098775.64623658622491.367510149
2096892.15715177 622358.82616715
#Sta/Elev= 30
  3735.1  233.34  3777.3  231.71  3801.9  229.12  3848.7  227.17  3872.2  224.91
  3910.2  222.74  3967.9  221.75  4022.1  217.46  4046.4  216.72  4139.1  215.44
  4734.6  214.84  4986.9  213.65  4987.9  211.65  5012.1  211.65  5013.1  213.65
  5175.9  215.07  5235.5  214.67    5319  215.55  5449.4  215.24  5526.1  217.18
  5565.5   220.2  5598.6  223.88  6050.3  228.42  6081.2  229.31  6710.7  230.76
  6721.7  228.64  6738.1  226.71    6752  228.56  6760.2  231.28  6874.5  235.41
#Mann= 3 , 1 , 0
  3735.1     .15       0  4986.9    .045       0  5013.1     .15       0
Bank Sta=4986.9,5013.1
XS Rating Curve= 0 ,0
Exp/Cntr=0.3,0.1

Type RM Length L Ch R = 1 ,125459.6,1148.112,1148.112,1148.112
BEGIN DESCRIPTION:
Black River 141.0
END DESCRIPTION:
XS GIS Cut Line= 3
2100185.70052422621474.9472110812099084.17936285621695.149442321
 2097449.6528007621312.535565414
#Sta/Elev= 30
  3867.8  234.88  3948.1  231.98  4012.9  226.75  4176.5  217.53  4211.7  218.11
  4468.9  214.43  4851.2  214.87  4986.9   213.6  4987.9   211.6  5012.1   211.6
  5013.1   213.6  5540.3  214.97  5592.2  215.94  5663.3  214.63  5702.4  215.67
  5736.1  218.68  5888.7  222.13    5908  221.41  5981.6  222.44  6044.5  221.48
  6095.5  223.72  6141.3  220.38  6170.8  221.91  6418.2  223.72  6518.7  226.72
  6617.1   227.7  6632.6  229.39  6649.9  233.97  6662.7  234.02  6669.8  235.54
#Mann= 3 , 1 , 0
  3867.8     .15       0  4986.9    .045       0  5013.1     .15       0
Bank Sta=4986.9,5013.1
XS Rating Curve= 0 ,0
Exp/Cntr=0.3,0.1

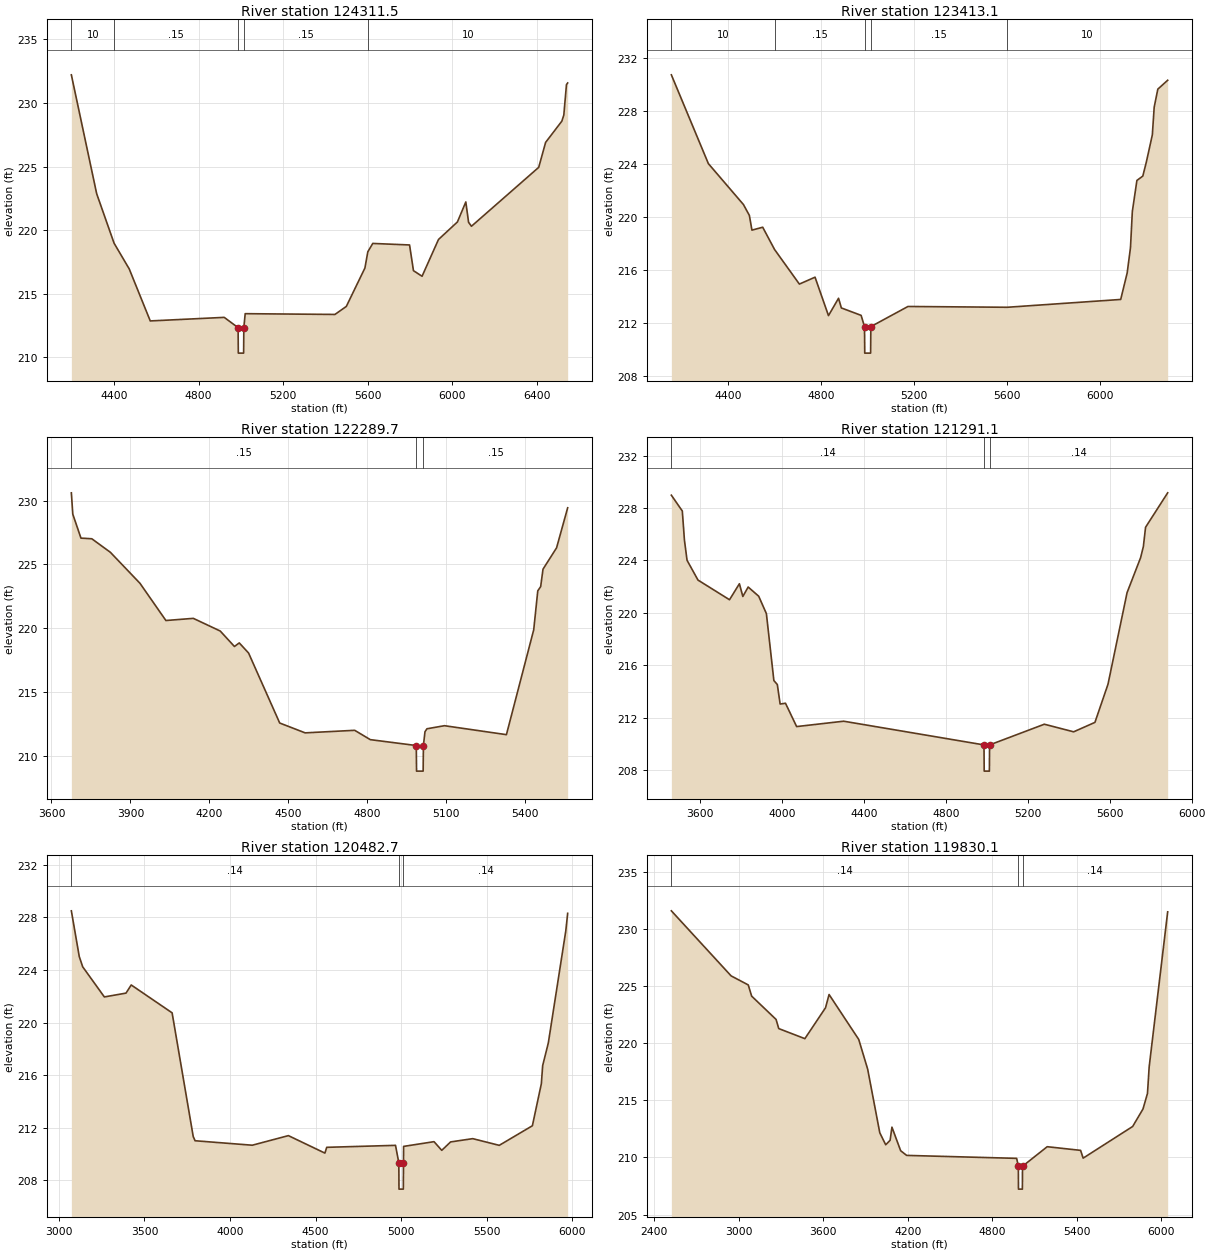
Type RM Length L Ch R = 1 ,124311.5,898.4091,898.4091,898.4091
BEGIN DESCRIPTION:
Black River 140.0
END DESCRIPTION:
XS GIS Cut Line= 3
2099975.53839471620910.0714873722099203.61057301620699.869357459
2097656.46489627620710.149461625
#Sta/Elev= 30
  4197.9  232.21  4317.6  222.87  4399.9  218.98  4471.5  216.96  4571.1  212.87
  4920.9  213.15  4986.5  212.34  4987.5  210.34  5012.6  210.34  5013.6  212.34
    5020  213.44  5444.5  213.38  5498.3  214.01  5586.3  217.03  5599.9   218.3
  5623.3  218.96  5797.4  218.84  5815.8  216.82  5856.5  216.38  5934.2  219.27
  6023.8  220.65  6063.4  222.22  6076.5  220.62  6090.1  220.31  6408.2  224.94
  6440.8   226.9  6517.6  228.57  6526.9  229.05  6539.4  231.44  6545.1  231.57
#Mann= 5 , 1 , 0
  4197.9      10       0  4399.9     .15       0  4986.5    .045       0
  5013.6     .15       0  5599.9      10       0
Bank Sta=4986.5,5013.6
XS Rating Curve= 0 ,0
Exp/Cntr=0.3,0.1

Type RM Length L Ch R = 1 ,123413.1,1123.411,1123.411,1123.411
BEGIN DESCRIPTION:
Black River 139.0
END DESCRIPTION:
XS GIS Cut Line= 3
2100182.06048733619969.581957686 2099338.3619384620000.452270485
 2098082.9692179620289.125195518
#Sta/Elev= 30
  4156.5  230.72  4315.5  224.02  4466.3  220.93  4491.7  220.11  4502.7     219
    4549  219.22  4599.9  217.54  4706.5  214.93  4773.8  215.45  4831.6  212.55
  4874.8  213.86  4886.9  213.13  4971.8  212.57  4986.4  211.72  4987.4  209.72
  5012.6  209.72  5013.6  211.72  5173.1  213.24  5599.9  213.18  6087.1  213.77
    6115  215.78  6129.1  217.68  6137.1  220.41  6156.7  222.75  6182.1  223.08
  6197.3  224.14    6223  226.19    6231  228.28  6246.6  229.64  6288.9  230.31
#Mann= 5 , 1 , 0
  4156.5      10       0  4599.9     .15       0  4986.4    .045       0
  5013.6     .15       0  5599.9      10       0
Bank Sta=4986.4,5013.6
XS Rating Curve= 0 ,0
Exp/Cntr=0.3,0.1

Type RM Length L Ch R = 1 ,122289.7,998.6101,998.6101,998.6101
BEGIN DESCRIPTION:
Black River 138.0
END DESCRIPTION:
XS GIS Cut Line= 3
2100098.82964398619689.0491151352098865.78714995619169.873854494
2098317.36159292619158.683741108
#Sta/Elev= 30
  3675.5   230.6    3681  228.93    3712  227.06  3753.2  227.01  3823.9  225.95
  3936.3  223.53  4034.9  220.62    4139  220.79  4241.3   219.8  4295.4  218.59
  4313.7  218.87  4349.1  218.08  4467.4  212.61  4564.1  211.84  4752.4  212.04
  4811.9  211.31  4986.5  210.85  4987.5  208.85  5012.6  208.85  5013.6  210.85
  5019.6  211.93  5027.1  212.16  5093.7   212.4  5329.1   211.7  5432.9   219.9
  5448.3  222.94  5459.3  223.27  5468.1  224.63  5519.7   226.3  5561.9  229.43
#Mann= 3 , 1 , 0
  3675.5     .15       0  4986.5    .045       0  5013.6     .15       0
Bank Sta=4986.5,5013.6
XS Rating Curve= 0 ,0
Exp/Cntr=0.3,0.1

Type RM Length L Ch R = 1 ,121291.1,808.4082,808.4082,808.4082
BEGIN DESCRIPTION:
Black River 137.0
END DESCRIPTION:
XS GIS Cut Line= 3
2100150.65016906 619376.785951072099152.19005198618224.724277589
2098265.74106987618081.752828904
#Sta/Elev= 30
  3460.5  228.98    3514  227.77  3524.4  225.54  3537.1  224.01  3590.6   222.5
  3744.4     221  3792.6  222.22  3809.4  221.25  3835.4  221.97  3886.8  221.27
  3924.3  219.94  3960.9  214.83  3977.7  214.53  3991.4  213.04  4017.6   213.1
  4071.9  211.32  4301.5  211.73  4986.4  209.92  4987.4  207.92  5012.7  207.92
  5013.7  209.92    5281   211.5    5424  210.92  5527.9  211.64  5591.6  214.55
  5684.7  221.54  5750.8  224.21  5764.3  225.06    5775  226.53  5882.9  229.16
#Mann= 3 , 1 , 0
  3460.5     .14       0  4986.4    .044       0  5013.7     .14       0
Bank Sta=4986.4,5013.7
XS Rating Curve= 0 ,0
Exp/Cntr=0.3,0.1

Type RM Length L Ch R = 1 ,120482.7,652.6066,652.6066,652.6066
BEGIN DESCRIPTION:
Black River 136.0
END DESCRIPTION:
XS GIS Cut Line= 3
2100285.29153334619248.6346525532099467.24324432617451.426442005
 2098551.3739641617585.957805169
#Sta/Elev= 30
  3072.8   228.5    3119  225.02  3139.2  224.24  3265.6  221.95  3392.2  222.24
  3422.6  222.86  3661.6  220.74    3785  211.33  3795.9  211.01  4130.1  210.67
  4341.1   211.4  4554.4  210.07  4565.2  210.51  4967.1  210.66  4986.4  209.33
  4987.4  207.33  5012.7  207.33  5013.7  209.33  5014.3  210.58  5192.2  210.94
  5237.3  210.28  5288.9  210.92  5418.3  211.17  5573.3  210.66  5766.9  212.15
  5819.3  215.35  5827.1  216.73  5860.2  218.46  5962.1  226.97  5973.1  228.31
#Mann= 3 , 1 , 0
  3072.8     .14       0  4986.4    .044       0  5013.7     .14       0
Bank Sta=4986.4,5013.7
XS Rating Curve= 0 ,0
Exp/Cntr=0.3,0.1

Type RM Length L Ch R = 1 ,119830.1,1003.91,1003.91,1003.91
BEGIN DESCRIPTION:
Black River 135.0
END DESCRIPTION:
XS GIS Cut Line= 4
2100426.83296754618811.6902251322100117.49983316616991.501781732
2099525.92383891616868.2605329672098512.83357358617217.754074275
#Sta/Elev= 30
  2522.7  231.57  2946.8  225.88  3068.4  225.09  3092.5  224.11  3265.9  222.07
  3284.9  221.27  3470.2  220.39  3616.7  223.09    3642  224.25  3852.5  220.32
  3915.9  217.72  4001.8  212.16  4043.8  211.11  4075.2   211.5  4088.1  212.65
  4149.9  210.59  4192.5  210.18  4973.2  209.92  4985.1  209.23  4986.1  207.23
  5013.8  207.23  5014.8  209.23    5190  210.94  5426.9  210.62  5445.1  209.94
  5796.5  212.71  5869.8  214.24  5901.6   215.6  5913.5  217.91  6044.9  231.48
#Mann= 3 , 1 , 0
  2522.7     .14       0  4985.1    .044       0  5014.8     .14       0
Bank Sta=4985.1,5014.8
XS Rating Curve= 0 ,0
Exp/Cntr=0.3,0.1