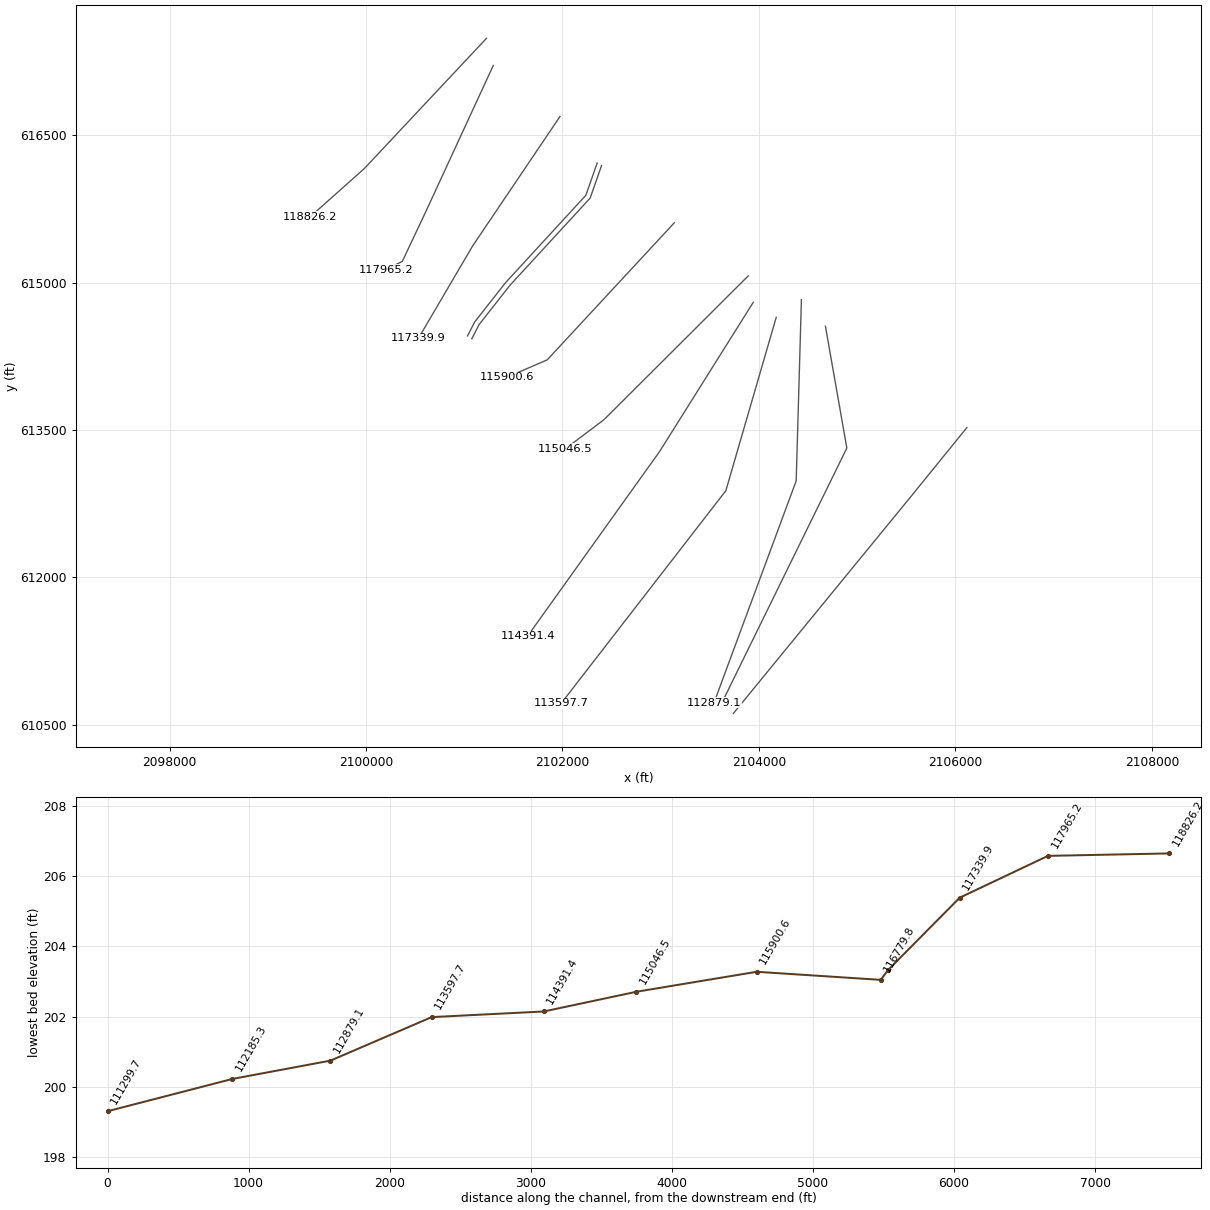
HEC-RAS study B4544BLACKRIVER.prj: B4544 BLACK RIVER SR1722

--- B4544BLACKRIVER.g02 (geometry) --- (continued)

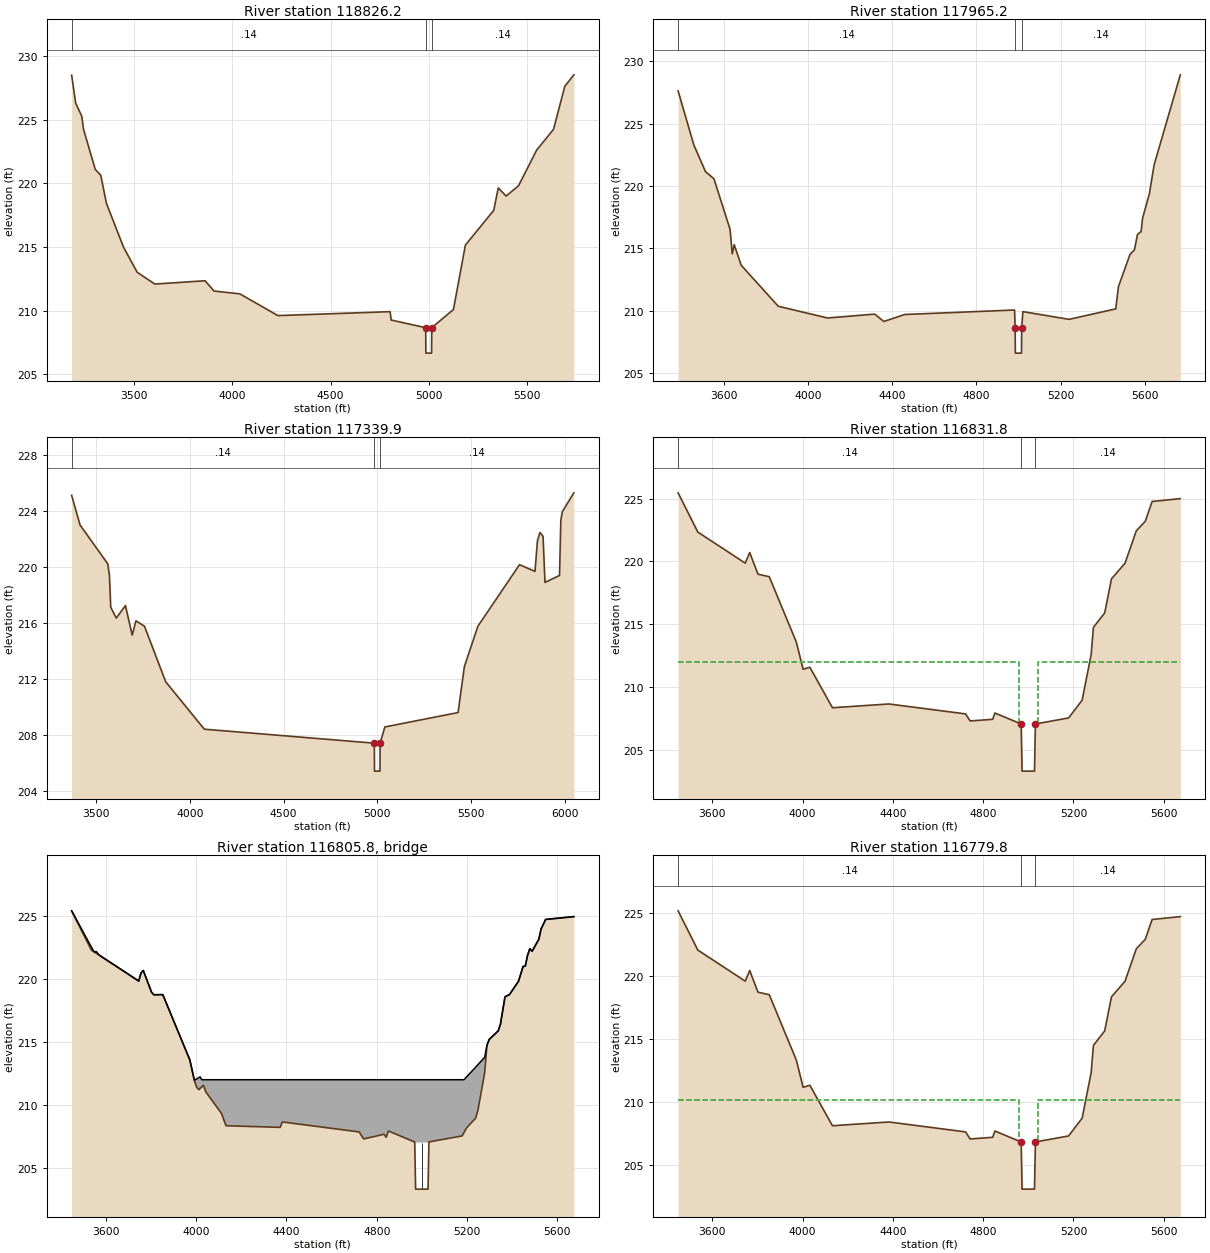
Type RM Length L Ch R = 1 ,118826.2,861.0087,861.0087,861.0087
BEGIN DESCRIPTION:
Black River 134.0
END DESCRIPTION:
XS GIS Cut Line= 3
 2101226.2910682 617488.216814792099982.77846807616162.593382663
2099430.89287599615670.908400573
#Sta/Elev= 30
  3182.1   228.5  3202.6  226.31  3233.7  225.27  3243.2  224.21  3302.5  221.09
  3330.3  220.64  3358.9  218.44  3446.8  214.96  3515.7  213.01  3605.5  212.08
  3861.4  212.34  3907.2  211.53  4038.4  211.31  4232.4   209.6  4803.4  209.91
    4809  209.25  4984.5  208.65  4985.5  206.65  5014.6  206.65  5015.6  208.65
  5125.9  210.08  5186.6  215.14  5331.2  217.88    5354  219.64  5394.2     219
  5457.3  219.81  5549.8  222.62  5635.2  224.24  5692.9  227.63  5738.8  228.53
#Mann= 3 , 1 , 0
  3182.1     .14       0  4984.5    .044       0  5015.6     .14       0
Bank Sta=4984.5,5015.6
XS Rating Curve= 0 ,0
Exp/Cntr=0.3,0.1

Type RM Length L Ch R = 1 ,117965.2,625.3063,625.3063,625.3063
BEGIN DESCRIPTION:
Black River 133.0
END DESCRIPTION:
XS GIS Cut Line= 4
 2101295.6217707617212.2540185452100612.87485264615732.979029515
2100369.42238581615217.4438057582100200.95067874 615134.09296119
#Sta/Elev= 30
  3382.2  227.62  3456.6   223.3  3512.4  221.14  3552.5  220.57  3629.1  216.52
  3639.6  214.54  3648.9  215.28  3682.2  213.63  3858.4  210.34  4092.5   209.4
  4316.9  209.71  4360.2  209.12  4459.7  209.68  4981.6  210.04  4984.4  208.58
  4985.4  206.58  5014.5  206.58  5015.5  208.58  5021.1  209.91  5240.8  209.29
  5462.6  210.13  5475.5  211.92  5530.4   214.5  5551.6  214.87  5565.9   216.1
  5583.3  216.34    5590   217.4  5622.5  219.37  5645.1  221.69  5769.5  228.91
#Mann= 3 , 1 , 0
  3382.2     .14       0  4984.4    .044       0  5015.5     .14       0
Bank Sta=4984.4,5015.5
XS Rating Curve= 0 ,0
Exp/Cntr=0.3,0.1

Type RM Length L Ch R = 1 ,117339.9,508.1051,508.1051,508.1051
BEGIN DESCRIPTION:
Black River 132.0
END DESCRIPTION:
XS GIS Cut Line= 3
2101974.94865411616693.0487576012101085.44964109615374.965401875
2100533.03404364614433.605863373
#Sta/Elev= 30
  3368.2  225.12  3413.1     223  3561.1  220.22  3570.1  219.38    3577  217.11
  3606.6  216.34  3655.4  217.24  3691.6  215.12  3711.5  216.14  3757.1  215.76
  3870.5  211.78  4076.6  208.39  4984.4  207.39  4985.4  205.39  5014.5  205.39
  5015.5  207.39  5040.7  208.55  5431.6  209.58  5465.3  212.87  5537.2  215.75
  5759.7  220.16  5842.4  219.68  5855.3  221.86  5868.8  222.46  5885.4   222.2
  5895.7  218.89  5973.4  219.39  5980.3  223.33  5988.3  223.95  6049.8   225.3
#Mann= 3 , 1 , 0
  3368.2     .14       0  4984.4    .044       0  5015.5     .14       0
Bank Sta=4984.4,5015.5
XS Rating Curve= 0 ,0
Exp/Cntr=0.5,0.3

Type RM Length L Ch R = 1 ,116831.8,52.0005,52.0005,52.0005
BEGIN DESCRIPTION:
Upstream Section of Bridge/Culvert/Weir
END DESCRIPTION:
XS GIS Cut Line= 5
2102353.53249018616219.603960333 2102237.7313168615890.060621173
2101421.46304581615002.2016247762101106.41985358614601.227561831
 2101033.5091148614458.776118416
#Sta/Elev= 30
  3448.3  225.46  3535.6  222.34  3745.6  219.87  3765.6  220.71  3802.2  218.99
  3852.2  218.79  3972.2  213.59  4002.2  211.43  4032.2  211.59  4132.2  208.37
  4382.2  208.67  4722.2  207.88  4742.2  207.32  4842.2  207.45  4852.2  207.95
  4968.5  207.08  4972.5  203.33  5027.5  203.33  5031.5  207.08  5178.6  207.56
  5238.6  208.97  5278.6   212.6  5288.6  214.76  5338.6  215.91  5368.6  218.62
  5428.6  219.86  5478.6  222.44  5518.6   223.2  5548.6  224.77  5673.6     225
#Mann= 3 , 1 , 0
  3448.3     .14       0  4968.5    .044       0  5031.5     .14       0
#XS Ineff= 2 , 0
       0    4957     212    5043       0     212
Permanent Ineff=
       F       F
Bank Sta=4968.5,5031.5
XS Rating Curve= 0 ,0
Exp/Cntr=0.5,0.3

Type RM Length L Ch R = 3 ,116805.8,,,
BEGIN DESCRIPTION:
Abattoir Road TOR
Structure ID: Abattoir Road
Approximate Survey Structure
END DESCRIPTION:
Bridge Culvert--1,0,-1,-1, 0
Deck Dist Width WeirC Skew NumUp NumDn MinLoCord MaxHiCord MaxSubmerge Is_Ogee
10,32,2.6,0, 52, 52, , , 0.95, 0, 1,1,,
  3448.3  3535.6  3548.3  3558.3  3568.3  3745.6  3755.6  3765.6  3802.2  3812.2
  3852.2  3972.2  3992.2  4002.2  4012.2  4017.6  4024.8  4032.2  4042.2  4112.2
  4132.2  4372.2  4382.2  4722.2  4742.2  4832.2  4842.2  4852.2  4972.5  5027.5
  5178.6  5186.7  5198.6  5238.6  5248.6  5278.6  5288.6  5298.6  5338.6  5348.6
  5368.6  5388.6  5428.6  5448.6  5458.6  5468.6  5478.6  5488.6  5518.6  5528.6
  5548.6  5673.6
  225.43  222.55  222.17  222.18  221.94  219.85  220.49  220.69  218.97  218.76
  218.77  213.57  211.96  212.06  212.17  212.23     212     212     212     212
     212     212     212     212     212     212     212     212     212     212
     212     212  212.23     213   213.2  213.78  214.74  215.21  215.89  216.44
   218.6  218.78  219.84  221.01  221.04   221.9  222.42  222.22  223.18     224
  224.75  224.97
  225.43  222.31  222.16  222.04  221.93  219.84  220.48  220.68  218.96  218.75
  218.76  213.56  211.91   211.4  211.21   211.3  211.43  211.56  211.05  209.32
  208.34  208.21  208.64  207.85  207.29  207.66  207.42  207.92     207     207
  207.53  207.79  208.18  208.94  209.56  212.57  214.73   215.2  215.88  216.43
  218.59  218.77  219.83     221  221.03  221.89  222.41  222.21  223.17  223.99
  224.74  224.97
  3448.3  3535.6  3548.3  3558.3  3568.3  3745.6  3755.6  3765.6  3802.2  3812.2
  3852.2  3972.2  3992.2  4002.2  4012.2  4017.6  4024.8  4032.2  4042.2  4112.2
  4132.2  4372.2  4382.2  4722.2  4742.2  4832.2  4842.2  4852.2  4972.5  5027.5
  5178.6  5186.7  5198.6  5238.6  5248.6  5278.6  5288.6  5298.6  5338.6  5348.6
  5368.6  5388.6  5428.6  5448.6  5458.6  5468.6  5478.6  5488.6  5518.6  5528.6
  5548.6  5673.6
  225.43  222.55  222.17  222.18  221.94  219.85  220.49  220.69  218.97  218.76
  218.77  213.57  211.96  212.06  212.17  212.23     212     212     212     212
     212     212     212     212     212     212     212     212     212     212
     212     212  212.23     213   213.2  213.78  214.74  215.21  215.89  216.44
   218.6  218.78  219.84  221.01  221.04   221.9  222.42  222.22  223.18     224
  224.75  224.97
  225.18  222.06  221.91  221.79  221.68  219.59  220.23  220.43  218.71   218.5
  218.51  213.31  211.66  211.15  210.96  211.05  211.18  211.31   210.8  209.07
  208.09  207.96  208.39   207.6  207.04  207.41  207.17  207.67  206.75  206.75
  207.28  207.54  207.93  208.69  209.31  212.32  214.48  214.95  215.63  216.18
  218.34  218.52  219.58  220.75  220.78  221.64  222.16  221.96  222.92  223.74
  224.49  224.72
Pier Skew, UpSta & Num, DnSta & Num=  ,5000, 2 ,5000, 2 , 0 , 0 , 0 ,,
       1       1
   202.3     208
       1       1
  202.05  207.75
BR Coef= 1 , 1 , 0 ,1.25, 0 ,,,0.8,0,2,0,
WSPro=,,,, 1 ,,,, 0 ,,,, 0 ,,,,-1 ,-1 ,-1 , 0 , 0 , 0 , 0 , 0
BR U #Sta/Elev= 93
  3448.3  225.43  3535.6  222.31  3548.3  222.16  3558.3  222.04  3568.3  221.93
  3578.3  221.81  3588.3  221.69  3598.3  221.57  3608.3  221.45  3698.3   220.4
  3708.3  220.28  3728.3  220.04  3745.6  219.84  3755.6  220.48  3765.6  220.68
  3768.3  220.55  3797.6  219.18  3802.2  218.96  3812.2  218.75  3852.2  218.76
  3897.6  216.79  3937.6  215.06  3972.2  213.56  3977.6  213.11  3992.2  211.91
  4002.2   211.4  4012.2  211.21  4017.6   211.3  4024.8  211.43  4032.2  211.56
  4042.2  211.05  4112.2  209.32  4132.2  208.34  4372.2  208.21  4382.2  208.64
  4722.2  207.85  4742.2  207.29  4832.2  207.66  4842.2  207.42  4852.2  207.92
 4959.91  207.11    4960  207.11  4960.1  207.11  4968.5  207.05  4972.5   203.3
    5000   203.3  5027.5   203.3  5031.5  207.05  5039.8  207.08 5039.89  207.08
    5040  207.08  5178.6  207.53  5186.7  207.79  5198.6  208.18  5238.6  208.94
  5248.6  209.56  5278.6  212.57  5288.6  214.73  5298.6   215.2  5338.6  215.88
  5348.6  216.43  5368.6  218.59  5388.6  218.77  5393.7  218.91  5403.7  219.17
  5413.7  219.44  5423.7   219.7  5428.6  219.83  5433.7  220.13  5443.7  220.71
  5448.6     221  5453.7  221.02  5458.6  221.03  5468.6  221.89  5473.7  222.16
  5478.6  222.41  5483.7  222.31  5488.6  222.21  5493.7  222.37  5503.7  222.69
  5513.6  223.01  5518.6  223.17  5523.6  223.58  5528.6  223.99  5533.6  224.18
  5543.6  224.55  5548.6  224.74  5563.6  224.77  5593.6  224.82  5643.6  224.91
  5653.6  224.93  5663.6  224.95  5673.6  224.97
BR U #Mann= 3
  3448.3     .14  4968.5    .044  5031.5     .14
BR U Banks=4968.5,5031.5
BR D #Sta/Elev= 93
  3448.3  225.18  3535.6  222.06  3548.3  221.91  3558.3  221.79  3568.3  221.68
  3578.3  221.56  3588.3  221.44  3598.3  221.32  3608.3   221.2  3698.3  220.15
  3708.3  220.03  3728.3  219.79  3745.6  219.59  3755.6  220.23  3765.6  220.43
  3768.3   220.3  3797.6  218.93  3802.2  218.71  3812.2   218.5  3852.2  218.51
  3897.6  216.54  3937.6  214.81  3972.2  213.31  3977.6  212.86  3992.2  211.66
  4002.2  211.15  4012.2  210.96  4017.6  211.05  4024.8  211.18  4032.2  211.31
  4042.2   210.8  4112.2  209.07  4132.2  208.09  4372.2  207.96  4382.2  208.39
  4722.2   207.6  4742.2  207.04  4832.2  207.41  4842.2  207.17  4852.2  207.67
 4959.91  206.86    4960  206.86  4960.1  206.86  4968.5   206.8  4972.5  203.05
    5000  203.05  5027.5  203.05  5031.5   206.8  5039.8  206.83 5039.89  206.83
    5040  206.83  5178.6  207.28  5186.7  207.54  5198.6  207.93  5238.6  208.69
  5248.6  209.31  5278.6  212.32  5288.6  214.48  5298.6  214.95  5338.6  215.63
  5348.6  216.18  5368.6  218.34  5388.6  218.52  5393.7  218.66  5403.7  218.92
  5413.7  219.19  5423.7  219.45  5428.6  219.58  5433.7  219.88  5443.7  220.46
  5448.6  220.75  5453.7  220.77  5458.6  220.78  5468.6  221.64  5473.7  221.91
  5478.6  222.16  5483.7  222.06  5488.6  221.96  5493.7  222.12  5503.7  222.44
  5513.6  222.76  5518.6  222.92  5523.6  223.33  5528.6  223.74  5533.6  223.93
  5543.6   224.3  5548.6  224.49  5563.6  224.52  5593.6  224.57  5643.6  224.66
  5653.6  224.68  5663.6   224.7  5673.6  224.72
BR D #Mann= 3
  3448.3     .14  4968.5    .044  5031.5     .14
BR D Banks=4968.5,5031.5
BC Design=,, 0 ,, 0 ,,,,,,
BC HTab HWMax=225.46
BC Use User HTab Curves=0
BC User HTab FreeFlow(D)= 0

Type RM Length L Ch R = 1 ,116779.8,879.2089,879.2089,879.2089
BEGIN DESCRIPTION:
Downstream Section of Bridge/Culvert/Weir
END DESCRIPTION:
XS GIS Cut Line= 5
2102397.50293572616191.8436790472102281.71176244615862.300339887
2101465.44349145 614974.441343492101150.40029922614573.467280545
2101077.47956034614431.015837129
#Sta/Elev= 30
  3448.3  225.18  3535.6  222.06  3745.6  219.59  3765.6  220.43  3802.2  218.71
  3852.2  218.51  3972.2  213.31  4002.2  211.15  4032.2  211.31  4132.2  208.09
  4382.2  208.39  4722.2   207.6  4742.2  207.04  4842.2  207.17  4852.2  207.67
  4968.5   206.8  4972.5  203.05  5027.5  203.05  5031.5   206.8  5178.6  207.28
  5238.6  208.69  5278.6  212.32  5288.6  214.48  5338.6  215.63  5368.6  218.34
  5428.6  219.58  5478.6  222.16  5518.6  222.92  5548.6  224.49  5673.6  224.72
#Mann= 3 , 1 , 0
  3448.3     .14       0  4968.5    .044       0  5031.5     .14       0
#XS Ineff= 2 , 0
       0    4957   210.1    5043       0   210.1
Permanent Ineff=
       F       F
Bank Sta=4968.5,5031.5
XS Rating Curve= 0 ,0
Exp/Cntr=0.5,0.3

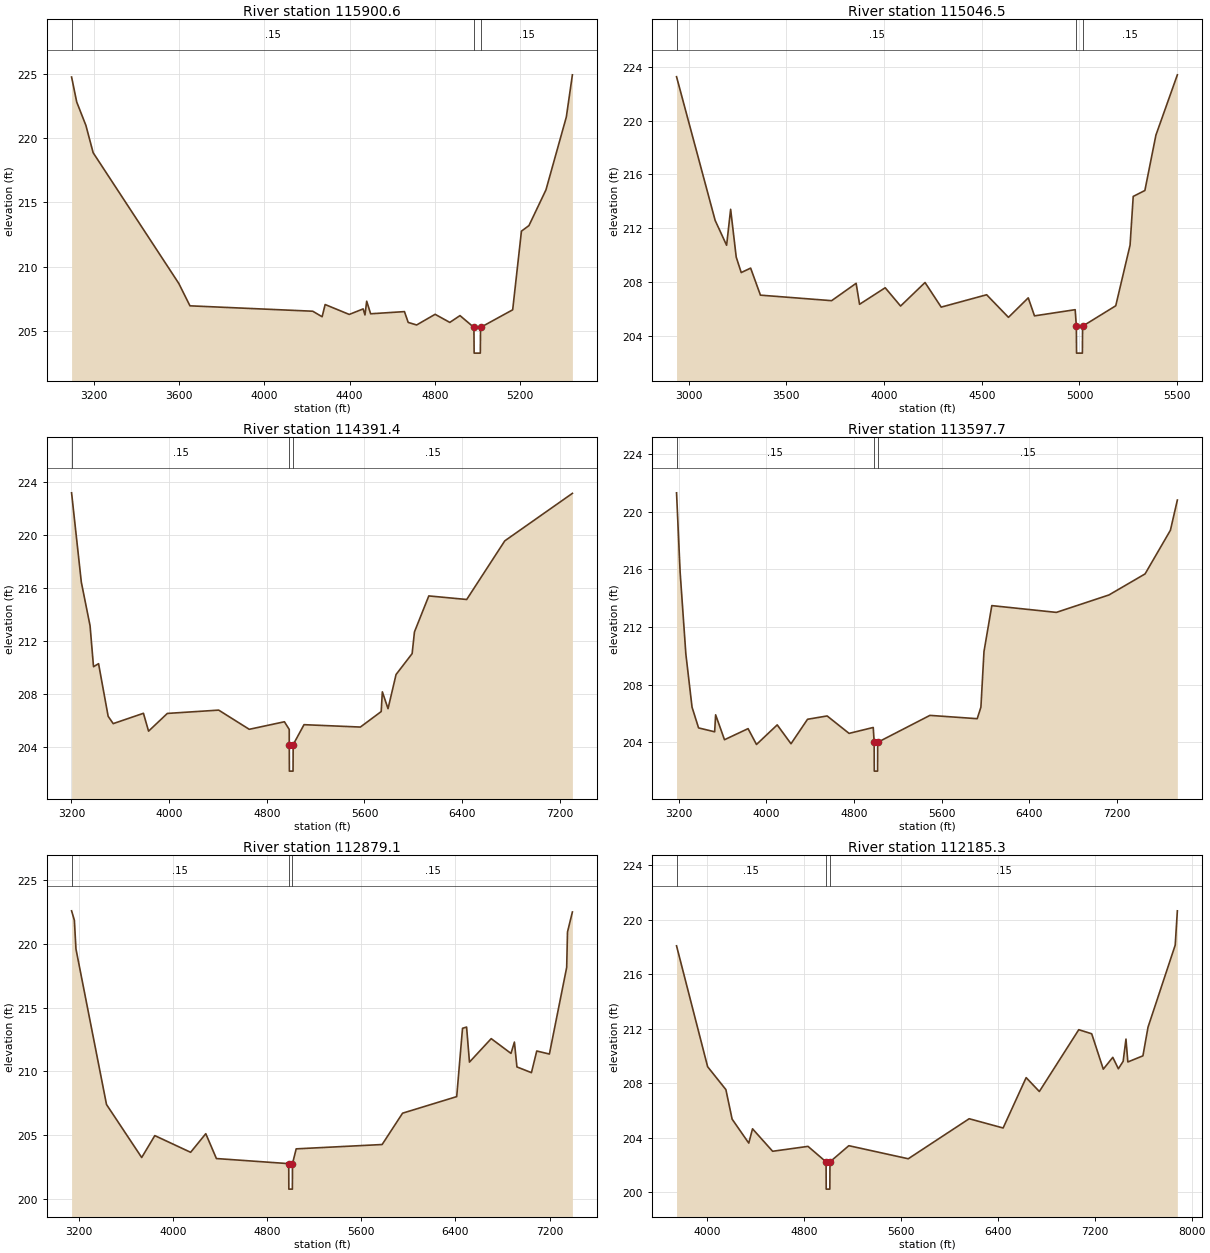
Type RM Length L Ch R = 1 ,115900.6,854.1087,854.1087,854.1087
BEGIN DESCRIPTION:
Black River 129.0
END DESCRIPTION:
XS GIS Cut Line= 3
2103138.65044553615610.6077895652101844.42733158614215.013648447
2101430.53313772614036.401838629
#Sta/Elev= 30
  3093.2  224.76  3117.3  222.82  3160.6  220.99  3194.6  218.87  3597.2   208.7
  3649.6  206.96  4226.7  206.54  4270.9  206.11    4285  207.06  4398.4  206.29
  4463.8  206.72  4472.3  206.25  4480.4  207.32  4498.9  206.34  4657.9  206.51
  4675.4  205.67  4715.1  205.47    4802   206.3    4871  205.67    4919   206.2
  4984.4  205.28  4985.4  203.28  5014.5  203.28  5015.5  205.28  5166.6  206.65
  5207.8  212.77    5243   213.2    5323  215.98  5418.8  221.65  5447.3  224.93
#Mann= 3 , 1 , 0
  3093.2     .15       0  4984.4    .045       0  5015.5     .15       0
Bank Sta=4984.4,5015.5
XS Rating Curve= 0 ,0
Exp/Cntr=0.3,0.1

Type RM Length L Ch R = 1 ,115046.5,655.1066,655.1066,655.1066
BEGIN DESCRIPTION:
Black River 128.0
END DESCRIPTION:
XS GIS Cut Line= 3
2103890.24806124615069.472306409 2102422.9431935613606.377481327
2102030.91922124613311.214490533
#Sta/Elev= 30
  2938.1  223.26  3135.6  212.58  3194.3  210.73  3214.9   213.4  3243.5  209.85
  3269.1   208.7  3317.3  209.03  3367.4  207.02  3731.7  206.61  3857.1   207.9
  3874.6  206.34  4005.8  207.57  4084.6  206.21  4209.7  207.96  4292.4  206.13
  4524.9  207.05  4636.6  205.37  4737.9  206.82  4769.8  205.48    4978  205.94
    4984  204.71    4985  202.71  5014.9  202.71  5015.9  204.71  5185.6  206.23
  5258.9  210.74    5275  214.36  5334.7   214.8    5391  218.91  5500.9   223.4
#Mann= 3 , 1 , 0
  2938.1     .15       0    4984    .045       0  5015.9     .15       0
Bank Sta=4984,5015.9
XS Rating Curve= 0 ,0
Exp/Cntr=0.3,0.1

Type RM Length L Ch R = 1 ,114391.4,793.708,793.708,793.708
BEGIN DESCRIPTION:
Black River 127.0
END DESCRIPTION:
XS GIS Cut Line= 3
  2103941.938585614800.569581702 2102990.0589399613284.194216745
2101645.16531252611403.285158082
#Sta/Elev= 30
  3200.8  223.18  3280.6  216.43  3352.3  213.13  3380.5  210.04  3421.8  210.27
  3500.5  206.29  3541.9  205.74  3789.5  206.52  3831.4  205.17  3985.1  206.51
  4405.8  206.76  4656.3  205.31  4944.3  205.88  4983.8   205.3    4984  204.15
    4985  202.15    5015  202.15    5016  204.15  5104.9  205.66  5566.5  205.48
    5737  206.65  5746.6  208.14  5793.1  206.87  5858.8  209.45  5990.5  211.03
  6009.6  212.67  6127.1  215.39  6437.5  215.12  6749.4  219.55  7303.4  223.14
#Mann= 3 , 1 , 0
  3200.8     .15       0    4984    .045       0    5016     .15       0
Bank Sta=4984,5016
XS Rating Curve= 0 ,0
Exp/Cntr=0.3,0.1

Type RM Length L Ch R = 1 ,113597.7,718.6073,718.6073,718.6073
BEGIN DESCRIPTION:
Black River 126.0
END DESCRIPTION:
XS GIS Cut Line= 3
2104175.70095364614647.1480271292103663.11575978  612883.2201538
2101985.74876354610717.088205063
#Sta/Elev= 30
    3178  221.31  3210.7  215.81  3263.1  210.12  3319.7  206.43  3379.3  204.99
  3526.3  204.72  3535.1   205.9  3616.2  204.17  3831.7  204.94  3908.6  203.84
    4098   205.2  4223.9  203.89    4375  205.59  4554.2  205.82  4754.5  204.61
  4975.4  205.02    4984  203.99    4985  201.99    5015  201.99    5016  203.99
  5493.4  205.86  5925.5  205.63  5959.3  206.43  5987.4  210.29    6059  213.48
  6648.7  213.01  7129.5  214.22  7459.3  215.68  7690.9  218.71  7754.5  220.81
#Mann= 3 , 1 , 0
    3178     .15       0    4984    .045       0    5016     .15       0
Bank Sta=4984,5016
XS Rating Curve= 0 ,0
Exp/Cntr=0.3,0.1

Type RM Length L Ch R = 1 ,112879.1,693.807,693.807,693.807
BEGIN DESCRIPTION:
Black River 125.0
END DESCRIPTION:
XS GIS Cut Line= 3
2104432.32355392614827.6598561992104379.13301496612983.461169511
2103542.95454222610725.748292813
#Sta/Elev= 30
  3140.2  222.59  3163.9  221.85  3177.3   219.6  3436.8  207.39  3735.5  203.23
  3846.9  204.95    4151  203.64  4279.7   205.1    4370  203.15    4984  202.75
    4985  200.75    5015  200.75    5016  202.75  5047.3  203.91  5777.1  204.25
  5950.7  206.71  6410.3  208.01  6459.7  213.37  6494.2  213.47  6518.7  210.72
  6703.3  212.56  6871.3   211.4  6900.3  212.29  6921.7  210.34  7044.9  209.89
  7089.9  211.59  7197.3  211.35  7344.2  218.15  7351.1  220.93  7392.7   222.5
#Mann= 3 , 1 , 0
  3140.2     .15       0    4984    .045       0    5016     .15       0
Bank Sta=4984,5016
XS Rating Curve= 0 ,0
Exp/Cntr=0.3,0.1

Type RM Length L Ch R = 1 ,112185.3,885.609,885.609,885.609
BEGIN DESCRIPTION:
Black River 124.0
END DESCRIPTION:
XS GIS Cut Line= 3
 2104676.8960321 614556.787111532104894.66823871613317.124550418
2103629.29541709610737.348410354
#Sta/Elev= 30
  3750.2   218.1  4006.7  209.22  4157.3  207.54  4208.8  205.37  4346.1  203.61
  4377.1  204.66    4543  203.01  4834.8  203.37    4984  202.23    4985  200.23
    5015  200.23    5016  202.23  5171.6  203.42    5662  202.46  6164.6   205.4
  6444.6  204.72  6634.7  208.42  6743.5   207.4  7068.8  211.94  7175.5  211.64
  7271.2  209.04  7349.4  209.91  7395.5  209.07    7435  209.62  7458.1  211.25
  7473.7  209.57  7598.1  210.02    7640  212.12  7864.4  218.15  7882.2  220.67
#Mann= 3 , 1 , 0
  3750.2     .15       0    4984    .045       0    5016     .15       0
Bank Sta=4984,5016
XS Rating Curve= 0 ,0
Exp/Cntr=0.3,0.1

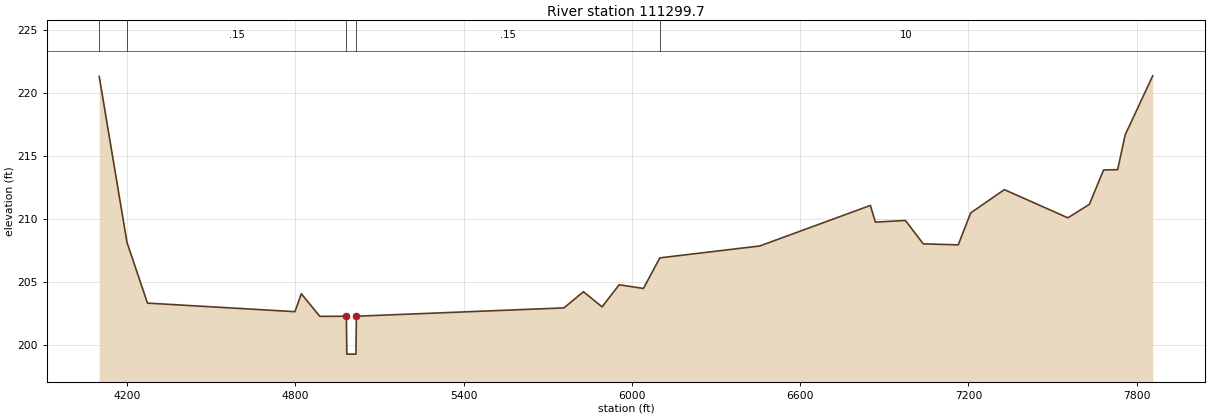
Type RM Length L Ch R = 1 ,111299.7,508.7052,508.7052,508.7052
BEGIN DESCRIPTION:
Black River 123.0
END DESCRIPTION:
XS GIS Cut Line= 3
2106116.62062037 613525.516661992105547.68485553612824.509558904
2103740.13654021610616.367184489
#Sta/Elev= 30
  4100.9  221.29  4199.9  208.16    4273  203.35  4798.8  202.67  4821.5  204.09
  4887.5   202.3  4982.2  202.31  4983.7  199.31  5016.3  199.31  5017.8  202.31
  5757.8  202.97  5827.5  204.25  5893.9  203.05  5954.8   204.8  6041.3  204.51
  6099.9  206.93    6456  207.87  6850.5  211.08  6868.5  209.76  6975.4  209.89
  7039.1  208.04  7163.8  207.96  7208.2  210.49  7328.3  212.33  7554.7   210.1
  7631.5  211.17    7682  213.89  7732.1  213.91  7759.1  216.67  7857.3  221.34
#Mann= 5 , 1 , 0
  4100.9      10       0  4199.9     .15       0  4982.2    .045       0
  5017.8     .15       0  6099.9      10       0
Bank Sta=4982.2,5017.8
XS Rating Curve= 0 ,0
Exp/Cntr=0.3,0.1