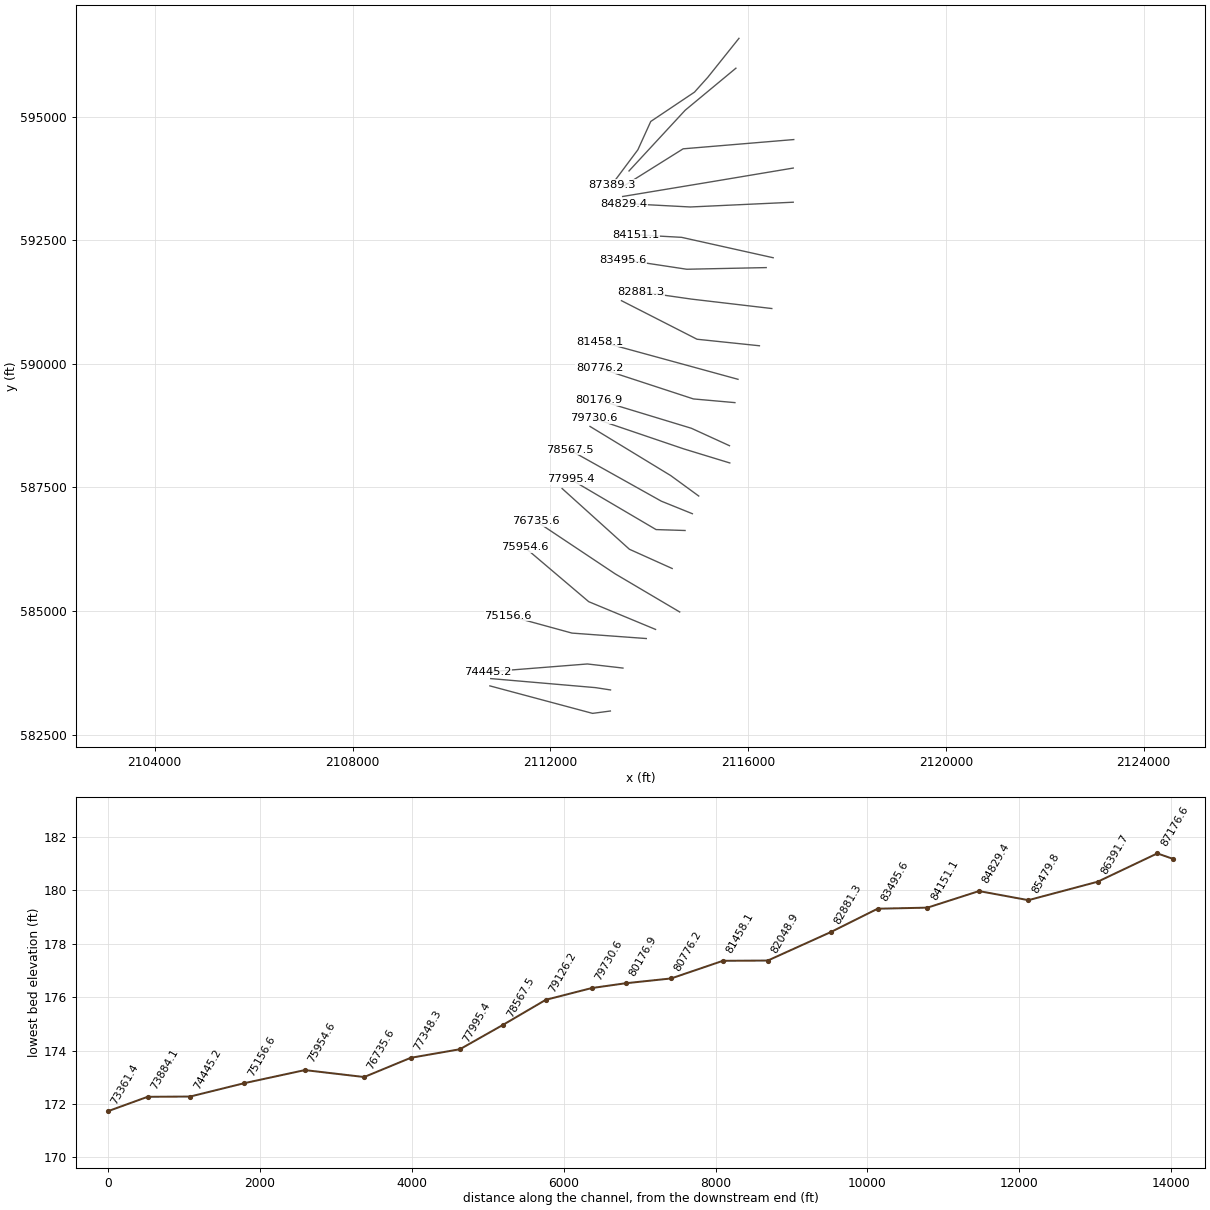
HEC-RAS study B4544BLACKRIVER.prj: B4544 BLACK RIVER SR1722

--- B4544BLACKRIVER.g02 (geometry) --- (continued)

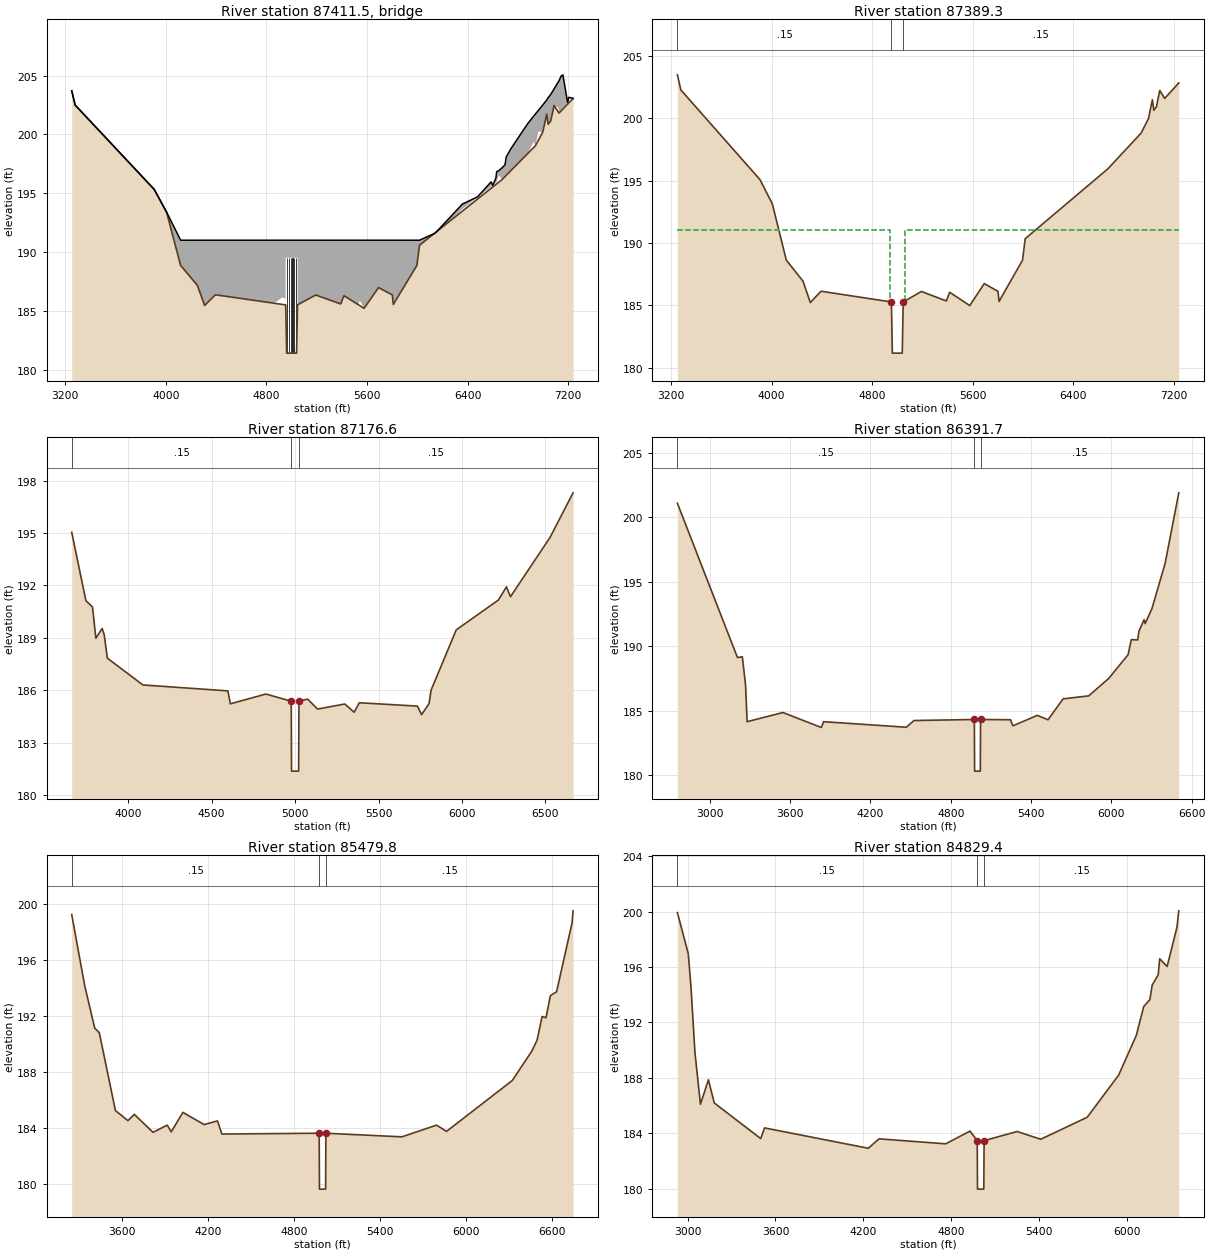
Type RM Length L Ch R = 3 ,87411.5 ,,,
BEGIN DESCRIPTION:
Red Hill Church Road TOR
Structure ID: Red Hill Church Road
Approximate Survey Structure
END DESCRIPTION:
Bridge Culvert--1,0,-1,-1, 0
Deck Dist Width WeirC Skew NumUp NumDn MinLoCord MaxHiCord MaxSubmerge Is_Ogee
10,24.5,2.6,0, 60, 60, , , 0.95, 0, 1,1,,
  3250.8    3278  3907.1  4005.7  4117.1  4249.9  4308.2    4393  4866.3  4924.8
  4949.6 4952.41  4952.5 5047.39  5047.5  5168.6  5191.6  5390.6  5416.5  5434.5
  5498.5  5531.5  5542.8  5576.3  5691.6  5751.7  5801.1  5809.2  5908.2  5996.4
  6017.5  6141.6  6259.4  6357.6  6479.9  6586.8  6600.1    6625  6631.2  6648.1
  6675.5  6697.7  6706.8  6743.8  6879.9  6924.4  6939.4  6962.2    6998  7029.2
  7040.5  7061.4  7087.7  7123.1  7127.2  7142.9  7158.1  7195.5  7205.7  7239.1
   203.7  202.49  195.32  193.38     191     191     191     191     191     191
     191     191     191     191     191     191     191     191     191     191
     191     191     191     191     191     191     191     191     191     191
     191   191.6  192.93  194.07  194.69  195.96  195.66  196.28  196.84  196.91
  197.17  197.41  198.07  198.77  200.94  201.53  201.73  202.03   202.5  202.92
  203.11   203.4  203.86  204.49  204.56  204.94  205.06  202.71  203.15  203.05
   203.7  202.49  195.31  193.37  188.85  187.17  185.45  186.36  185.67  186.13
  186.05   185.6   189.5   189.5  185.51  185.88  186.34  185.58  186.28  185.66
  185.18  185.35  185.88  185.21  186.97  186.07  186.35  185.54  186.76  188.85
  190.57  191.59  192.35  193.64  194.68  195.57  195.65   195.9  195.97  196.52
  196.17  196.53  196.58  196.92  198.39  199.37  199.03  200.23  200.19  201.71
  200.86  201.14  202.45  202.27  201.81  202.02  202.22  202.71  203.15  203.05
  3250.8    3278  3907.1  4005.7  4117.1  4249.9  4308.2    4393  4866.3  4924.8
  4949.6 4952.41  4952.5 5047.39  5047.5  5168.6  5191.6  5390.6  5416.5  5434.5
  5498.5  5531.5  5542.8  5576.3  5691.6  5751.7  5801.1  5809.2  5908.2  5996.4
  6017.5  6141.6  6259.4  6357.6  6479.9  6586.8  6600.1    6625  6631.2  6648.1
  6675.5  6697.7  6706.8  6743.8  6879.9  6924.4  6939.4  6962.2    6998  7029.2
  7040.5  7061.4  7087.7  7123.1  7127.2  7142.9  7158.1  7195.5  7205.7  7239.1
   203.7  202.49  195.32  193.38     191     191     191     191     191     191
     191     191     191     191     191     191     191     191     191     191
     191     191     191     191     191     191     191     191     191     191
     191   191.6  192.93  194.07  194.69  195.96  195.66  196.28  196.84  196.91
  197.17  197.41  198.07  198.77  200.94  201.53  201.73  202.03   202.5  202.92
  203.11   203.4  203.86  204.49  204.56  204.94  205.06  202.71  203.15  203.05
  203.45  202.24  195.06  193.12   188.6  186.92   185.2  186.11  185.42  185.88
   185.8  185.35  189.25  189.25  185.26  185.63  186.09  185.33  186.03  185.41
  184.93   185.1  185.63  184.96  186.72  185.82   186.1  185.29  186.51   188.6
  190.32  191.34   192.1  193.39  194.43  195.32   195.4  195.65  195.72  196.27
  195.92  196.28  196.33  196.67  198.14  199.12  198.78  199.98  199.94  201.46
  200.61  200.89   202.2  202.02  201.56  201.77  201.97  202.46   202.9   202.8
Pier Skew, UpSta & Num, DnSta & Num=  ,4964.6, 2 ,4964.6, 2 , 0 , 0 , 0 ,,
       1       1
   180.4   190.5
       1       1
  180.15  190.25
Pier Skew, UpSta & Num, DnSta & Num=  ,4978.7, 2 ,4978.7, 2 , 0 , 0 , 0 ,,
       1       1
   180.4   190.5
       1       1
  180.15  190.25
Pier Skew, UpSta & Num, DnSta & Num=  ,4992.9, 2 ,4992.9, 2 , 0 , 0 , 0 ,,
       1       1
   180.4   190.5
       1       1
  180.15  190.25
Pier Skew, UpSta & Num, DnSta & Num=  ,5007.1, 2 ,5007.1, 2 , 0 , 0 , 0 ,,
       1       1
   180.4   190.5
       1       1
  180.15  190.25
Pier Skew, UpSta & Num, DnSta & Num=  ,5021.2, 2 ,5021.2, 2 , 0 , 0 , 0 ,,
       1       1
   180.4   190.5
       1       1
  180.15  190.25
Pier Skew, UpSta & Num, DnSta & Num=  ,5035.4, 2 ,5035.4, 2 , 0 , 0 , 0 ,,
       1       1
   180.4   190.5
       1       1
  180.15  190.25
Abutment Skew #Up #Dn= , 2 , 2
  4952.3  4957.5
   189.5  183.04
  4952.3  4957.5
  189.25  182.79
Abutment Skew #Up #Dn= , 2 , 2
  5042.5 5047.59
  183.04   189.5
  5042.5 5047.59
  182.79  189.25
BR Coef= 1 , 1 , 0 ,1.25, 0 ,,,0.8,0,2,0,
WSPro=,,,, 1 ,,,, 0 ,,,, 0 ,,,,-1 ,-1 ,-1 , 0 , 0 , 0 , 0 , 0
BR U #Sta/Elev= 30
  3250.8   203.7    3278  202.49  3907.1  195.31  4005.7  193.37  4117.1  188.85
  4249.9  187.17  4308.2  185.45    4393  186.36    4953   185.5  4960.5   181.4
  5039.5   181.4    5047   185.5  5191.6  186.34  5390.6  185.58  5416.5  186.28
  5576.3  185.21  5691.6  186.97  5801.1  186.35  5809.2  185.54  5996.4  188.85
  6017.5  190.57  6675.5  196.17  6939.4  199.03    6998  200.19  7029.2  201.71
  7040.5  200.86  7061.4  201.14  7087.7  202.45  7127.2  201.81  7239.1  203.05
BR U #Mann= 3
  3250.8     .15    4953     .05    5047     .15
BR U Banks=4953,5047
BR D #Sta/Elev= 30
  3250.8  203.45    3278  202.24  3907.1  195.06  4005.7  193.12  4117.1   188.6
  4249.9  186.92  4308.2   185.2    4393  186.11    4953  185.25  4960.5  181.15
  5039.5  181.15    5047  185.25  5191.6  186.09  5390.6  185.33  5416.5  186.03
  5576.3  184.96  5691.6  186.72  5801.1   186.1  5809.2  185.29  5996.4   188.6
  6017.5  190.32  6675.5  195.92  6939.4  198.78    6998  199.94  7029.2  201.46
  7040.5  200.61  7061.4  200.89  7087.7   202.2  7127.2  201.56  7239.1   202.8
BR D #Mann= 3
  3250.8     .15    4953     .05    5047     .15
BR D Banks=4953,5047
BC Design=,, 0 ,, 0 ,,,,,,
BC HTab HWMax=203.72
BC Use User HTab Curves=0
BC User HTab FreeFlow(D)= 0

Type RM Length L Ch R = 1 ,87389.3 ,212.6522,212.6522,212.6522
BEGIN DESCRIPTION:
Downstream Section of Bridge/Culvert/Weir
END DESCRIPTION:
XS GIS Cut Line= 6
2115815.66889779596583.0149889242115186.62252386595796.707021512
2114916.00978183595494.8739631322114031.31081745594901.607951753
 2113771.1081809594329.1621513392113243.82283808593622.794993942
#Sta/Elev= 30
  3250.8  203.47    3278  202.26  3907.1  195.08  4005.7  193.14  4117.1  188.62
  4249.9  186.94  4308.2  185.22    4393  186.13    4953  185.27  4960.5  181.17
  5039.5  181.17    5047  185.27  5191.6  186.11  5390.6  185.35  5416.5  186.05
  5576.3  184.98  5691.6  186.74  5801.1  186.12  5809.2  185.31  5996.4  188.62
  6017.5  190.34  6675.5  195.94  6939.4   198.8    6998  199.96  7029.2  201.48
  7040.5  200.63  7061.4  200.91  7087.7  202.22  7127.2  201.58  7239.1  202.82
#Mann= 3 , 1 , 0
  3250.8     .15       0    4953     .05       0    5047     .15       0
#XS Ineff= 2 , 0
       0    4942     191    5058       0     191
Permanent Ineff=
       F       F
Bank Sta=4953,5047
XS Rating Curve= 0 ,0
Exp/Cntr=0.5,0.3

Type RM Length L Ch R = 1 ,87176.6 ,784.908,784.908,784.908
BEGIN DESCRIPTION:
Black River 91.0
END DESCRIPTION:
XS GIS Cut Line= 3
2115753.73827027595979.2488711512114727.98787666595129.070256558
2113591.91636521593900.877811668
#Sta/Elev= 30
  3661.1  195.04    3746  191.13  3785.6  190.77  3805.8  188.98  3843.3  189.54
  3855.3   189.2  3874.8  187.84  4087.9  186.31    4597  185.97  4612.1  185.23
  4824.7  185.79  4976.8  185.38  4978.8  181.38  5021.2  181.38  5023.2  185.38
  5075.3   185.5  5134.6  184.93  5297.8  185.22  5354.2  184.75  5384.7  185.29
  5732.9   185.1  5758.3  184.61  5802.8  185.24  5815.1  186.01  5965.9  189.46
  6219.1  191.17  6266.6  191.92  6291.3  191.36  6527.7  194.74  6666.4   197.3
#Mann= 3 , 1 , 0
  3661.1     .15       0  4976.8    .046       0  5023.2     .15       0
Bank Sta=4976.8,5023.2
XS Rating Curve= 0 ,0
Exp/Cntr=0.3,0.1

Type RM Length L Ch R = 1 ,86391.7 ,911.9092,911.9092,911.9092
BEGIN DESCRIPTION:
Black River 90.0
END DESCRIPTION:
XS GIS Cut Line= 3
2116924.11012928594535.8042451792114686.35745484594348.462346902
2113415.22457484593552.274279377
#Sta/Elev= 30
  2758.5  201.07  3207.1  189.12  3243.5  189.18  3267.6  187.01  3279.3  184.15
  3546.5  184.86  3833.7   183.7  3850.6  184.15  4468.7  183.72  4525.4  184.24
  4976.8  184.32  4978.8  180.32  5021.3  180.32  5023.3  184.32  5246.7   184.3
  5264.9  183.83  5447.3  184.64  5527.1   184.3  5639.9  185.92  5831.1  186.15
  5982.3  187.52  6125.3  189.34  6149.4  190.51  6196.7  190.48  6206.1  191.15
  6244.4  192.05  6252.7  191.75  6303.5  192.91  6401.9  196.41  6503.9  201.88
#Mann= 3 , 1 , 0
  2758.5     .15       0  4976.8    .046       0  5023.3     .15       0
Bank Sta=4976.8,5023.3
XS Rating Curve= 0 ,0
Exp/Cntr=0.3,0.1

Type RM Length L Ch R = 1 ,85479.8 ,650.4066,650.4066,650.4066
BEGIN DESCRIPTION:
Black River 89.0
END DESCRIPTION:
XS GIS Cut Line= 3
2116913.53002208593959.6184068682115196.35262246593671.925491766
2113463.30506203593384.492579298
#Sta/Elev= 30
  3250.2  199.27  3341.2  194.16  3410.6  191.15  3442.6  190.82    3555  185.25
  3642.4  184.53  3686.8  184.98  3817.4  183.69  3916.3  184.21  3944.3  183.73
  4025.8  185.12  4173.7  184.25  4267.2  184.51  4297.7  183.57  4976.5  183.63
  4978.5  179.63  5021.4  179.63  5023.4  183.63  5553.5  183.37  5795.8  184.21
  5864.8  183.76  6323.7   187.4  6459.2  189.49  6496.4  190.28  6532.1  191.98
    6559  191.89  6589.6  193.47  6632.9  193.75  6740.8  198.68    6748  199.54
#Mann= 3 , 1 , 0
  3250.2     .15       0  4976.5    .046       0  5023.4     .15       0
Bank Sta=4976.5,5023.4
XS Rating Curve= 0 ,0
Exp/Cntr=0.3,0.1

Type RM Length L Ch R = 1 ,84829.4 ,678.3069,678.3069,678.3069
BEGIN DESCRIPTION:
Black River 88.0
END DESCRIPTION:
XS GIS Cut Line= 3
2116913.39002066593268.6914059212114832.06893128593172.330429525
2113496.73540077593242.611141658
#Sta/Elev= 30
    2931  199.93  3005.1  196.97  3024.4  194.44  3050.6  189.84  3088.2   186.1
  3142.6  187.86  3182.5  186.19  3499.3  183.62  3525.7  184.39  4233.5  182.92
  4306.6   183.6  4761.6  183.24  4927.4  184.16  4976.6  183.47  4978.6  179.97
  5021.5  179.97  5023.5  183.47  5249.1  184.13  5409.9  183.57  5727.3  185.16
  5941.5   188.2  6062.1  191.07  6112.6  193.15  6154.5  193.65  6170.4   194.7
  6211.3  195.44  6221.8   196.6  6272.2  196.04  6339.5  198.88  6351.7  200.06
#Mann= 3 , 1 , 0
    2931     .15       0  4976.6    .046       0  5023.5     .15       0
Bank Sta=4976.6,5023.5
XS Rating Curve= 0 ,0
Exp/Cntr=0.3,0.1

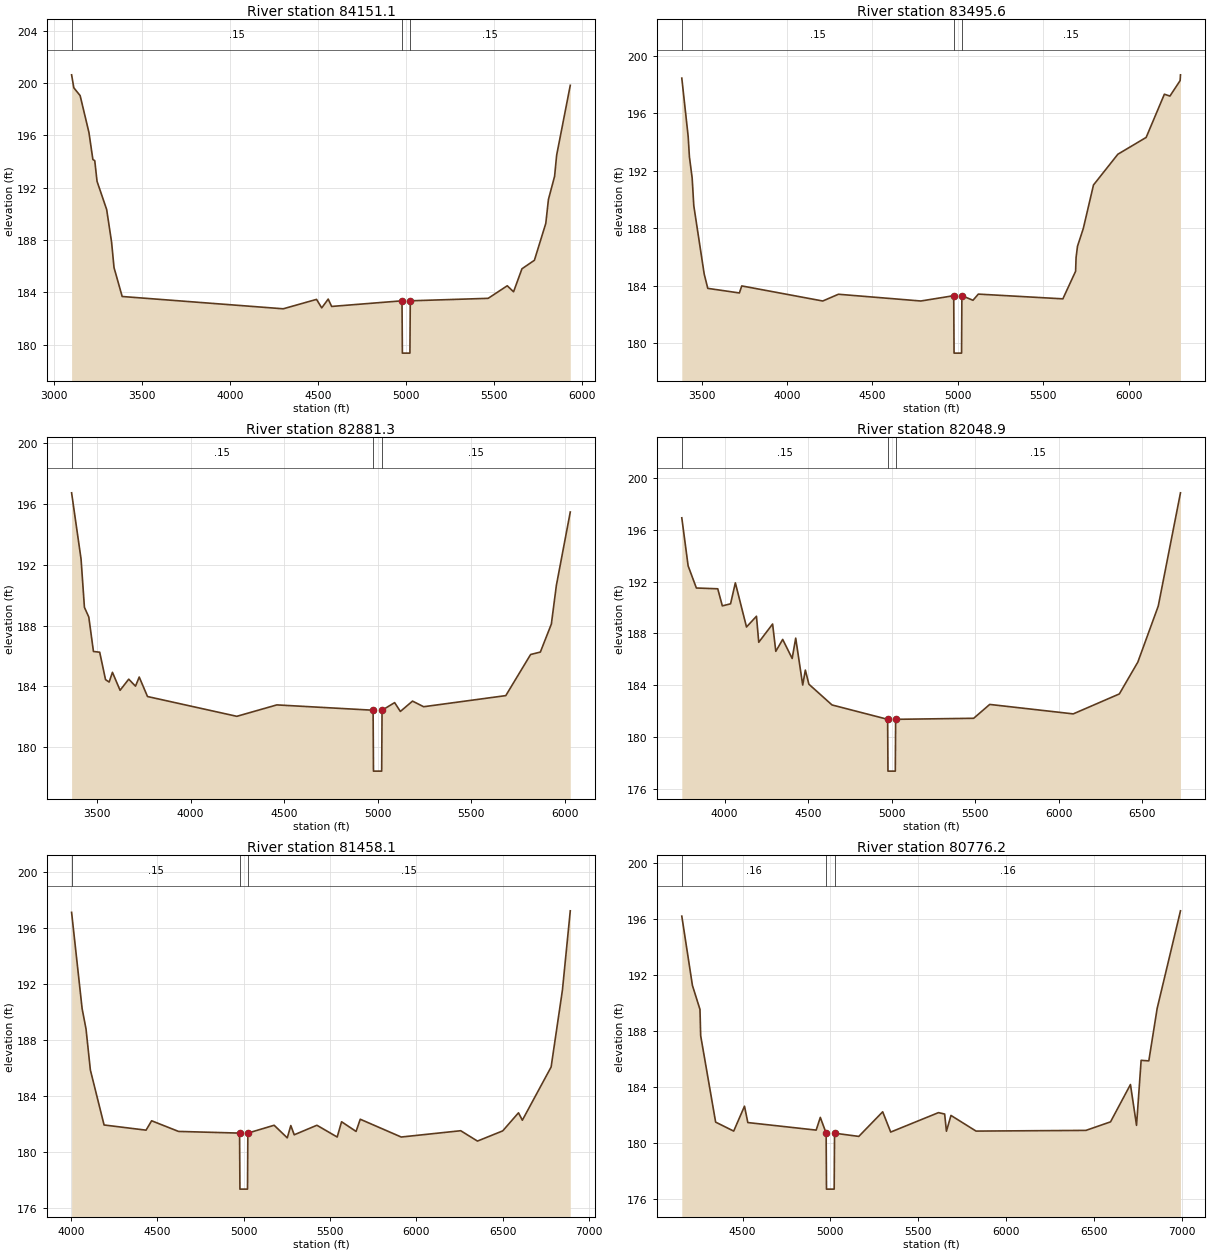
Type RM Length L Ch R = 1 ,84151.1 ,655.5066,655.5066,655.5066
BEGIN DESCRIPTION:
Black River 87.0
END DESCRIPTION:
XS GIS Cut Line= 3
2116507.58590877592145.5700256842114655.12713839592558.254207283
2113721.70768034 592610.11473277
#Sta/Elev= 30
  3099.7  200.63  3112.3  199.64  3148.2  199.04  3198.1  196.23  3220.7  194.15
  3231.2  194.07  3244.2  192.49  3298.9  190.33  3326.8  187.84  3340.7  185.89
    3387  183.68  4301.8  182.74  4491.1  183.46  4520.5  182.81  4557.3  183.48
  4576.8  182.92  4976.6  183.35  4978.6  179.35  5021.5  179.35  5023.5  183.35
    5466  183.54  5574.4   184.5  5610.2  184.04  5657.9   185.8  5728.6  186.45
  5793.3  189.27  5808.3   191.1  5843.3  192.87    5855  194.49  5932.4  199.83
#Mann= 3 , 1 , 0
  3099.7     .15       0  4976.6    .045       0  5023.5     .15       0
Bank Sta=4976.6,5023.5
XS Rating Curve= 0 ,0
Exp/Cntr=0.3,0.1

Type RM Length L Ch R = 1 ,83495.6 ,614.3062,614.3062,614.3062
BEGIN DESCRIPTION:
Black River 86.0
END DESCRIPTION:
XS GIS Cut Line= 3
2116366.52447944 591946.428007842114759.21819311591912.947668594
 2113462.3450523592109.439659586
#Sta/Elev= 30
  3384.3  198.46  3421.5  194.41  3428.9  192.98  3444.9  191.51  3454.6  189.57
  3515.4  184.82  3536.4  183.82  3721.3   183.5  3735.4  183.99  4209.5  182.94
  4301.2  183.41  4783.7  182.94  4976.1  183.31  4978.1  179.31    5022  179.31
    5024  183.31  5088.9  182.99  5120.3  183.42  5615.1  183.09  5689.6  185.01
  5692.5  185.97  5700.7  186.75  5734.7  187.99  5794.4  191.02    5937  193.16
  6102.6  194.33  6209.4  197.34  6241.8  197.21  6301.6  198.29  6303.6  198.69
#Mann= 3 , 1 , 0
  3384.3     .15       0  4976.1    .045       0    5024     .15       0
Bank Sta=4976.1,5024
XS Rating Curve= 0 ,0
Exp/Cntr=0.3,0.1

Type RM Length L Ch R = 1 ,82881.3 ,832.4084,832.4084,832.4084
BEGIN DESCRIPTION:
Black River 85.0
END DESCRIPTION:
XS GIS Cut Line= 3
 2116479.9156284591118.3896175862114852.88914225591309.271551733
2113834.09881917591455.613034565
#Sta/Elev= 30
  3363.3  196.72  3413.9  192.37  3431.9   189.2  3455.3  188.56  3480.2   186.3
  3513.6  186.25  3544.8  184.45  3564.1  184.29  3581.8  184.93  3622.6  183.75
  3668.9  184.48    3705  184.02    3725  184.62  3769.3  183.34  4247.1  182.04
  4461.2  182.79    4976  182.44    4978  178.44  5021.9  178.44  5023.9  182.44
  5091.2  182.94  5121.8  182.36  5186.9  183.04  5246.3  182.67  5685.7   183.4
  5818.5   186.1  5870.6  186.26  5929.5   188.1  5956.3  190.64  6030.7  195.46
#Mann= 3 , 1 , 0
  3363.3     .15       0    4976    .045       0  5023.9     .15       0
Bank Sta=4976,5023.9
XS Rating Curve= 0 ,0
Exp/Cntr=0.3,0.1

Type RM Length L Ch R = 1 ,82048.9 ,590.806,590.806,590.806
BEGIN DESCRIPTION:
Black River 84.0
END DESCRIPTION:
XS GIS Cut Line= 3
2116229.38308983590365.4619884062114967.38030235 590497.43332563
2113438.94481519591277.411228902
#Sta/Elev= 30
  3744.1  196.93    3782  193.22  3831.4  191.51  3959.3  191.45  3986.7  190.13
    4036  190.29  4064.6  191.91  4131.4   188.5    4191  189.33  4204.7  187.32
  4287.6  188.73  4306.8  186.62    4348  187.54  4404.7  186.07  4425.9  187.64
  4467.8  184.02  4483.6  185.17  4504.9  184.08  4643.2  182.48  4976.1  181.37
  4978.1  177.37    5022  177.37    5024  181.37  5491.1  181.45  5587.1  182.52
    6087  181.79  6362.9  183.33  6473.7  185.79    6596  190.12  6728.9  198.86
#Mann= 3 , 1 , 0
  3744.1     .15       0  4976.1    .045       0    5024     .15       0
Bank Sta=4976.1,5024
XS Rating Curve= 0 ,0
Exp/Cntr=0.3,0.1

Type RM Length L Ch R = 1 ,81458.1 ,681.9069,681.9069,681.9069
BEGIN DESCRIPTION:
Black River 83.0
END DESCRIPTION:
XS GIS Cut Line= 3
2115796.38870243589687.0951147272114852.88914225 589945.79773608
2113009.79046671590449.962844627
#Sta/Elev= 30
  4002.9  197.12  4063.8  190.25  4086.4   188.8  4111.6  185.87  4191.1  181.94
  4434.2  181.57  4466.5  182.24  4622.4  181.48  4976.1  181.36  4978.1  177.36
    5022  177.36    5024  181.36  5176.3  181.92  5252.4  181.02  5272.9   181.9
  5292.7  181.24  5424.1  181.92  5541.6  181.08    5567  182.17    5651  181.48
  5675.2  182.35  5912.6  181.08  6257.2  181.53  6354.3  180.79  6500.7  181.52
    6592  182.81  6614.3  182.28    6781  186.08  6846.5  191.57    6892  197.23
#Mann= 3 , 1 , 0
  4002.9     .15       0  4976.1    .046       0    5024     .15       0
Bank Sta=4976.1,5024
XS Rating Curve= 0 ,0
Exp/Cntr=0.3,0.1

Type RM Length L Ch R = 1 ,80776.2 ,599.3061,599.3061,599.3061
BEGIN DESCRIPTION:
Black River 82.0
END DESCRIPTION:
XS GIS Cut Line= 3
2115733.92806954589215.4703359012114894.51956408589290.081091908
2112997.04033751 589911.38738741
#Sta/Elev= 30
  4154.3  196.22  4214.9  191.26  4257.8  189.55  4261.8  187.67    4347  181.49
  4449.8  180.85  4511.3  182.63  4530.2  181.46  4919.3  180.92    4943  181.83
  4976.1   180.7  4978.1   176.7  5021.9   176.7  5023.9   180.7  5162.1  180.47
  5298.1  182.23  5343.7  180.78  5615.7  182.17  5650.9  182.07    5661  180.84
  5686.9  181.97  5829.6  180.85  6455.4   180.9  6595.3  181.51  6708.8  184.18
  6743.4  181.26  6769.6  185.91  6813.3  185.87  6860.8  189.62  6993.6   196.6
#Mann= 3 , 1 , 0
  4154.3     .16       0  4976.1    .047       0  5023.9     .16       0
Bank Sta=4976.1,5023.9
XS Rating Curve= 0 ,0
Exp/Cntr=0.3,0.1

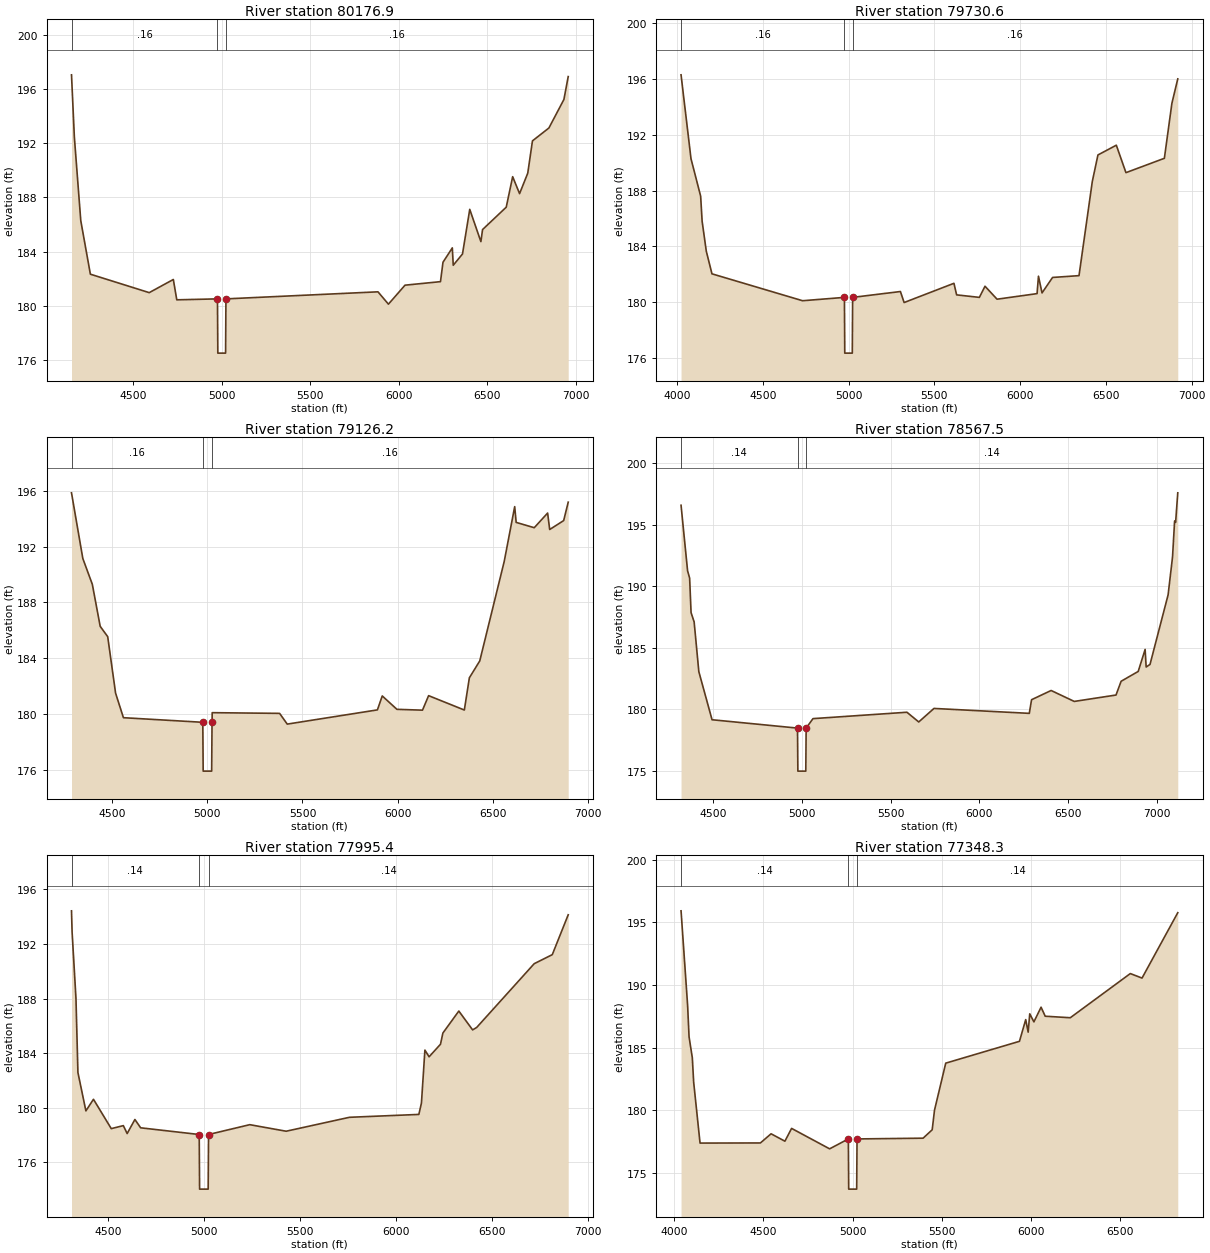
Type RM Length L Ch R = 1 ,80176.9 ,446.3045,446.3045,446.3045
BEGIN DESCRIPTION:
Black River 81.0
END DESCRIPTION:
XS GIS Cut Line= 3
2115623.93695503588344.1015065932114852.88914225588696.815080529
2112977.77014225589266.790855916
#Sta/Elev= 30
  4150.9  197.04  4167.1  192.44  4203.3  186.29  4257.6  182.34  4590.3  180.98
  4726.5  181.95    4746  180.45    4976  180.52    4978  176.52  5021.9  176.52
  5023.9  180.52  5883.3  181.04  5942.3  180.13  6036.1  181.53  6236.6  181.79
  6250.7  183.22  6303.5  184.28  6308.7     183    6361  183.83    6402  187.12
    6465  184.74  6474.4  185.63  6608.2  187.28  6644.6  189.53  6683.6  188.28
  6729.9  189.79  6756.5  192.17  6849.4  193.12  6934.2  195.22  6958.6  196.91
#Mann= 3 , 1 , 0
  4150.9     .16       0    4976    .047       0  5023.9     .16       0
Bank Sta=4976,5023.9
XS Rating Curve= 0 ,0
Exp/Cntr=0.3,0.1

Type RM Length L Ch R = 1 ,79730.6 ,604.4061,604.4061,604.4061
BEGIN DESCRIPTION:
Black River 80.0
END DESCRIPTION:
XS GIS Cut Line= 3
2115630.20701857587995.2679719722114696.76756032588280.490862046
 2112879.4391459588898.027119348
#Sta/Elev= 30
  4023.8  196.31  4081.8  190.29  4138.1   187.6  4146.6  185.81    4171  183.65
    4204  182.03  4732.3   180.1  4976.1  180.34  4978.1  176.34    5022  176.34
    5024  180.34  5302.5  180.76  5324.1  179.97  5614.5  181.35  5630.1  180.52
  5762.8  180.34  5795.6  181.14  5865.8  180.21  6099.1  180.61  6107.2  181.86
    6128  180.66  6189.4  181.77  6343.5   181.9  6421.1  188.66  6453.9  190.56
    6561  191.26  6617.2  189.29  6841.1  190.32  6884.9  194.26  6919.2  196.02
#Mann= 3 , 1 , 0
  4023.8     .16       0  4976.1    .047       0    5024     .16       0
Bank Sta=4976.1,5024
XS Rating Curve= 0 ,0
Exp/Cntr=0.3,0.1

Type RM Length L Ch R = 1 ,79126.2 ,558.7057,558.7057,558.7057
BEGIN DESCRIPTION:
Black River 79.0
END DESCRIPTION:
XS GIS Cut Line= 3
2115001.75065062587326.4811953652114436.56492377587739.265377978
2112802.87837013588734.075458077
#Sta/Elev= 30
  4285.1  195.85  4344.7  191.14  4394.7  189.29    4436  186.28  4475.5  185.54
    4517  181.49  4558.2  179.73  4975.7   179.4  4977.7   175.9  5022.3   175.9
  5024.3   179.4  5025.2  180.09  5379.7  180.04  5419.8  179.27  5894.1  180.29
  5919.6  181.29  5996.7  180.33  6131.2  180.27  6163.4  181.31  6351.3  180.28
  6377.8  182.59  6432.4   183.8  6560.9  190.92  6616.2  194.86  6623.9  193.73
    6719  193.35  6789.4   194.4  6800.2  193.22  6873.8  193.86  6897.7  195.18
#Mann= 3 , 1 , 0
  4285.1     .16       0  4975.7    .047       0  5024.3     .16       0
Bank Sta=4975.7,5024.3
XS Rating Curve= 0 ,0
Exp/Cntr=0.3,0.1

Type RM Length L Ch R = 1 ,78567.5 ,572.1058,572.1058,572.1058
BEGIN DESCRIPTION:
Black River 78.0
END DESCRIPTION:
XS GIS Cut Line= 3
2114873.42935038586968.617569245 2114244.8229809587222.600142771
2112392.39421082588258.820642469
#Sta/Elev= 30
  4319.1   196.6    4356  191.26  4367.5  190.67  4375.6  187.86  4392.9  187.11
  4419.4  183.06  4493.9  179.15  4975.7  178.47  4977.7  174.97  5022.4  174.97
  5024.4  178.47  5062.9  179.24  5592.6  179.76  5659.2  178.97  5745.1  180.07
  6282.5  179.67  6295.3  180.78  6405.6  181.53    6536  180.64  6771.4  181.16
  6800.2  182.28  6896.6  183.08  6935.5  184.87  6941.4  183.44  6963.1  183.65
  7065.1  189.31  7090.1  192.39  7101.8  195.32  7107.5  195.21  7119.6  197.61
#Mann= 3 , 1 , 0
  4319.1     .14       0  4975.7    .046       0  5024.4     .14       0
Bank Sta=4975.7,5024.4
XS Rating Curve= 0 ,0
Exp/Cntr=0.3,0.1

Type RM Length L Ch R = 1 ,77995.4 ,647.1066,647.1066,647.1066
BEGIN DESCRIPTION:
Black River 77.0
END DESCRIPTION:
XS GIS Cut Line= 3
2114725.84785498586629.2541305822114138.73190592 586647.99432047
2112417.67446698587661.124586202
#Sta/Elev= 30
  4311.2  194.43  4314.3  192.87  4334.4  188.03  4344.6  182.59  4386.1  179.78
  4425.5  180.63  4518.1  178.48  4580.9   178.7  4600.9  178.12  4641.1  179.15
    4671  178.54  4975.7  178.05  4977.7  174.05  5022.3  174.05  5024.3  178.05
  5238.8  178.77    5428  178.29  5757.5  179.31  6118.5  179.52    6132  180.35
    6150  184.23  6171.8  183.74  6231.1  184.66  6243.6  185.48  6326.5  187.09
  6398.3  185.71  6419.5  185.89  6718.8  190.56  6812.8  191.22  6895.7  194.14
#Mann= 3 , 1 , 0
  4311.2     .14       0  4975.7    .046       0  5024.3     .14       0
Bank Sta=4975.7,5024.3
XS Rating Curve= 0 ,0
Exp/Cntr=0.3,0.1

Type RM Length L Ch R = 1 ,77348.3 ,612.7062,612.7062,612.7062
BEGIN DESCRIPTION:
Black River 75.0
END DESCRIPTION:
XS GIS Cut Line= 3
2114465.04521235585860.7363434322113599.48644191586250.180289545
2112238.49265139587478.312733827
#Sta/Elev= 30
  4038.5  195.91  4075.3  188.37  4083.3  185.88  4101.6   184.2  4109.2  182.25
  4144.9   177.4  4483.1  177.41  4542.8  178.14  4620.3  177.55  4657.7  178.57
  4870.8  176.94  4975.6  177.73  4977.6  173.73  5022.3  173.73  5024.3  177.73
  5394.3  177.79  5445.3  178.46  5458.2  180.02  5521.1  183.77  5934.1  185.51
  5969.1  187.24  5982.8  186.24  5991.7   187.7    6015  187.06  6055.1  188.23
  6078.3  187.51  6218.8  187.39    6555  190.91  6620.6  190.55  6820.8  195.76
#Mann= 3 , 1 , 0
  4038.5     .14       0  4975.6    .046       0  5024.3     .14       0
Bank Sta=4975.6,5024.3
XS Rating Curve= 0 ,0
Exp/Cntr=0.3,0.1

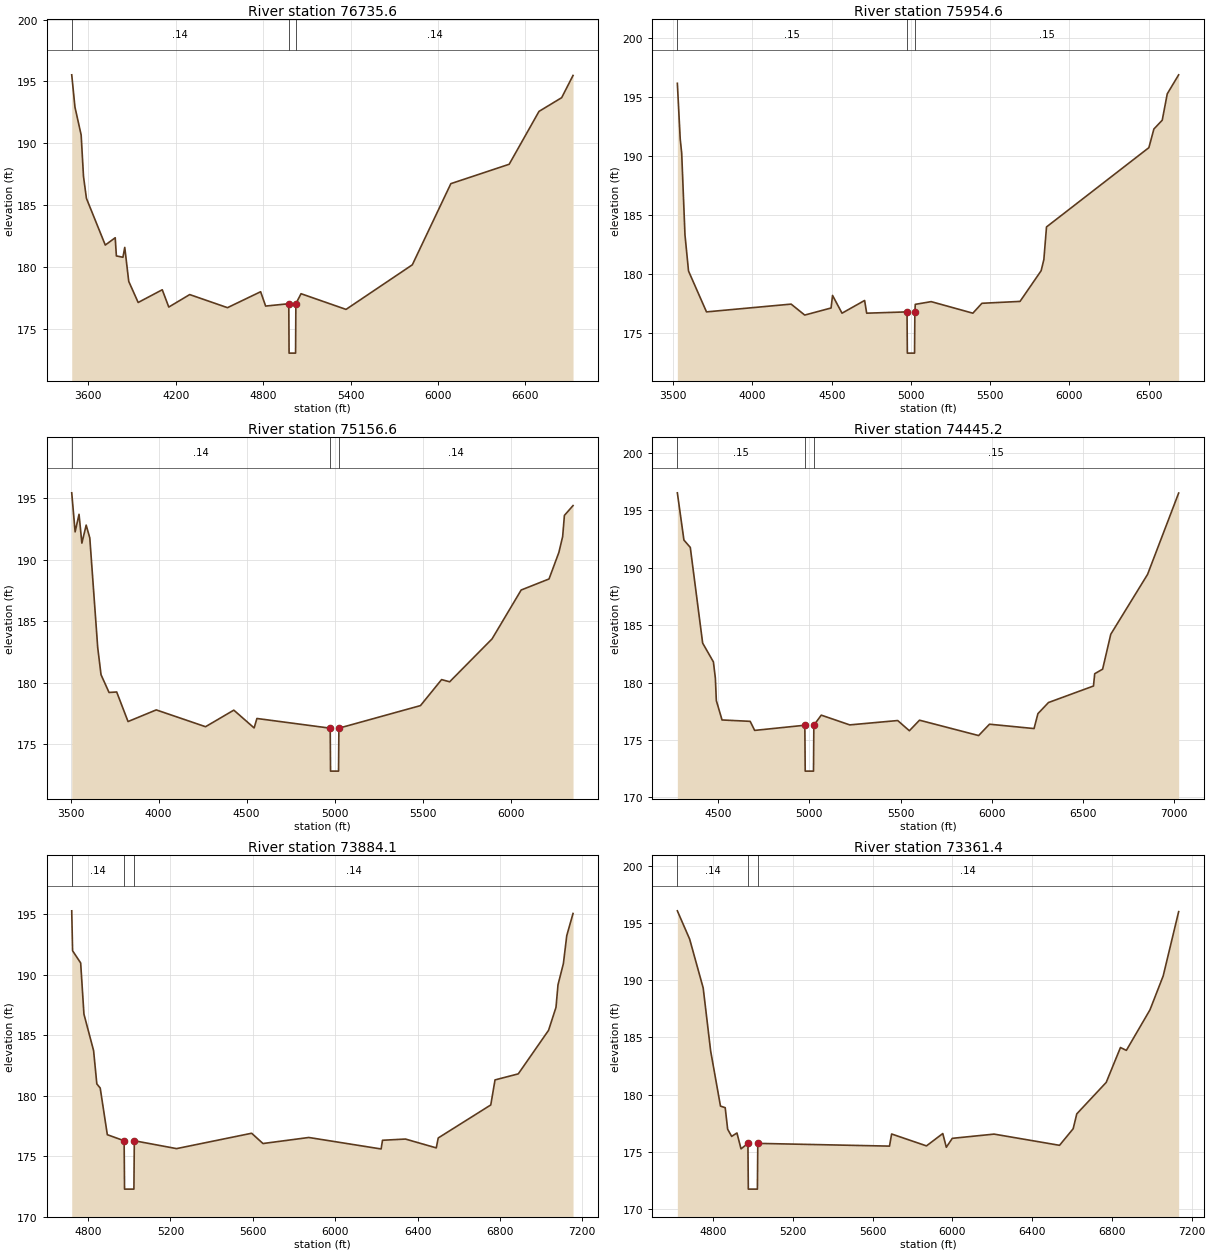
Type RM Length L Ch R = 1 ,76735.6 ,781.0079,781.0079,781.0079
BEGIN DESCRIPTION:
Black River 74.0
END DESCRIPTION:
XS GIS Cut Line= 3
2114616.87675081584981.4974343792113307.76348597585755.135273409
2111709.56729195586820.096064323
#Sta/Elev= 30
  3485.7  195.54  3507.8  192.93  3550.4  190.67  3566.5  187.31  3586.6  185.54
    3716  181.76  3784.2  182.35  3792.2  180.88  3837.2  180.77  3849.7  181.57
    3877  178.82  3941.8  177.11  4107.1  178.14  4151.9  176.74  4295.5  177.75
  4554.9  176.69  4782.3  177.98  4816.7  176.82  4975.6  177.01  4977.6  173.01
  5022.3  173.01  5024.3  177.01  5059.8  177.82  5368.6  176.55  5823.6  180.16
  6088.1  186.73  6488.5   188.3  6693.2  192.58  6848.8  193.69  6926.8  195.49
#Mann= 3 , 1 , 0
  3485.7     .14       0  4975.6    .046       0  5024.3     .14       0
Bank Sta=4975.6,5024.3
XS Rating Curve= 0 ,0
Exp/Cntr=0.3,0.1

Type RM Length L Ch R = 1 ,75954.6 ,798.0081,798.0081,798.0081
BEGIN DESCRIPTION:
Black River 72.0
END DESCRIPTION:
XS GIS Cut Line= 3
2114128.65180378584628.7038596322112777.34811144585189.369540682
2111480.90497499586289.690689892
#Sta/Elev= 30
  3525.9  196.17  3543.9  191.46  3553.3  190.24    3574  183.31  3596.4  180.24
  3709.8  176.77  4243.9  177.43  4329.7   176.5    4496   177.1  4505.2  178.17
    4565  176.66  4707.6  177.74  4720.6  176.66  4975.2  176.77  4977.2  173.27
  5022.7  173.27  5024.7  176.77  5027.3  177.41  5127.5  177.64  5390.7  176.66
  5447.7   177.5  5688.3  177.66  5821.4  180.26  5838.7  181.21  5855.4  183.98
  6501.4  190.71    6533  192.29  6585.7  193.04  6617.4  195.28  6689.3  196.89
#Mann= 3 , 1 , 0
  3525.9     .15       0  4975.2    .046       0  5024.7     .15       0
Bank Sta=4975.2,5024.7
XS Rating Curve= 0 ,0
Exp/Cntr=0.3,0.1

Type RM Length L Ch R = 1 ,75156.6 ,711.4072,711.4072,711.4072
BEGIN DESCRIPTION:
Black River 71.0
END DESCRIPTION:
XS GIS Cut Line= 3
2113941.64990895584444.1619897272112438.19467491 584554.36310636
2111145.49157635584908.526694989
#Sta/Elev= 30
    3507  195.46  3526.3  192.28  3548.5  193.71  3564.6  191.36  3589.1  192.83
  3609.7  191.78  3654.5  182.87  3673.4  180.64    3719  179.19  3762.4  179.23
  3826.9  176.82  3987.1  177.77  4267.2   176.4  4427.8  177.75  4543.1   176.3
    4559  177.07  4975.3  176.28  4977.3  172.78  5022.7  172.78  5024.7  176.28
  5488.1  178.12  5608.1  180.24  5653.9  180.06    5895  183.56  6060.2  187.54
  6218.4  188.44  6274.3   190.6  6295.8  191.89  6305.8  193.62  6354.8  194.42
#Mann= 3 , 1 , 0
    3507     .14       0  4975.3    .046       0  5024.7     .14       0
Bank Sta=4975.3,5024.7
XS Rating Curve= 0 ,0
Exp/Cntr=0.3,0.1

Type RM Length L Ch R = 1 ,74445.2 ,561.1057,561.1057,561.1057
BEGIN DESCRIPTION:
Black River 70.0
END DESCRIPTION:
XS GIS Cut Line= 3
2113469.40512384583847.0759396412112750.43783877583929.866778535
2110731.04737692583770.005158707
#Sta/Elev= 30
    4276  196.54  4312.1  192.42    4347  191.78  4414.8  183.44  4473.8   181.8
  4484.5  180.38  4489.8  178.43  4521.1  176.74  4675.4  176.62    4700  175.83
  4975.2  176.28  4977.2  172.28  5022.7  172.28  5024.6  176.28  5065.3  177.16
  5221.5  176.31  5484.5  176.69  5548.5   175.8  5604.1  176.72  5928.3  175.38
  5987.9  176.37  6232.3  175.99  6253.5  177.29  6311.5  178.26  6558.2   179.7
    6565  180.77  6608.4  181.17  6653.1  184.21  6854.9  189.43  7025.4  196.52
#Mann= 3 , 1 , 0
    4276     .15       0  4975.2    .047       0  5024.6     .15       0
Bank Sta=4975.2,5024.6
XS Rating Curve= 0 ,0
Exp/Cntr=0.3,0.1

Type RM Length L Ch R = 1 ,73884.1 ,522.7053,522.7053,522.7053
BEGIN DESCRIPTION:
Black River 69.0
END DESCRIPTION:
XS GIS Cut Line= 3
2113217.98257625583404.4614547672112916.96952618583451.091927259
2110794.72802217583634.183782471
#Sta/Elev= 30
  4720.7  195.28  4724.8  191.98  4764.1  190.97    4780  186.74  4826.9  183.72
  4842.6  180.97    4859  180.63  4893.6  176.77  4975.2  176.27  4977.2  172.27
  5022.7  172.27  5024.7  176.27  5229.9  175.62  5594.5  176.89  5649.5  176.04
  5872.1  176.54  6223.3  175.59  6230.1  176.31  6341.4  176.41  6491.2  175.68
  6500.7   176.5  6755.9  179.23  6776.5   181.3  6889.5   181.8  7036.5   185.4
  7072.6   187.3  7082.4  189.17  7108.6  190.92  7124.9  193.23  7155.4  195.06
#Mann= 3 , 1 , 0
  4720.7     .14       0  4975.2    .046       0  5024.7     .14       0
Bank Sta=4975.2,5024.7
XS Rating Curve= 0 ,0
Exp/Cntr=0.3,0.1

Type RM Length L Ch R = 1 ,73361.4 ,640.2065,640.2065,640.2065
BEGIN DESCRIPTION:
Black River 68.0
END DESCRIPTION:
XS GIS Cut Line= 3
2113215.04254646582978.5671393132112854.51889339582930.686654155
2110778.10785377583486.582286872
#Sta/Elev= 30
  4621.5  196.06  4683.1  193.59    4751  189.32  4788.5   183.8  4837.7  178.99
  4861.4  178.85  4873.7  176.97  4893.7  176.34  4920.3  176.64  4940.7  175.25
  4975.3  175.73  4977.3  171.73  5022.8  171.73  5024.8  175.73  5685.1  175.49
  5695.7  176.55  5870.4  175.51  5952.2  176.59  5969.9  175.39  5999.8  176.17
  6209.4  176.54  6537.5  175.56  6605.9  177.01    6624  178.31  6771.5  181.06
    6843  184.11  6872.5  183.86  6990.8   187.4  7057.2  190.37  7134.7  195.99
#Mann= 3 , 1 , 0
  4621.5     .14       0  4975.3    .046       0  5024.8     .14       0
Bank Sta=4975.3,5024.8
XS Rating Curve= 0 ,0
Exp/Cntr=0.3,0.1