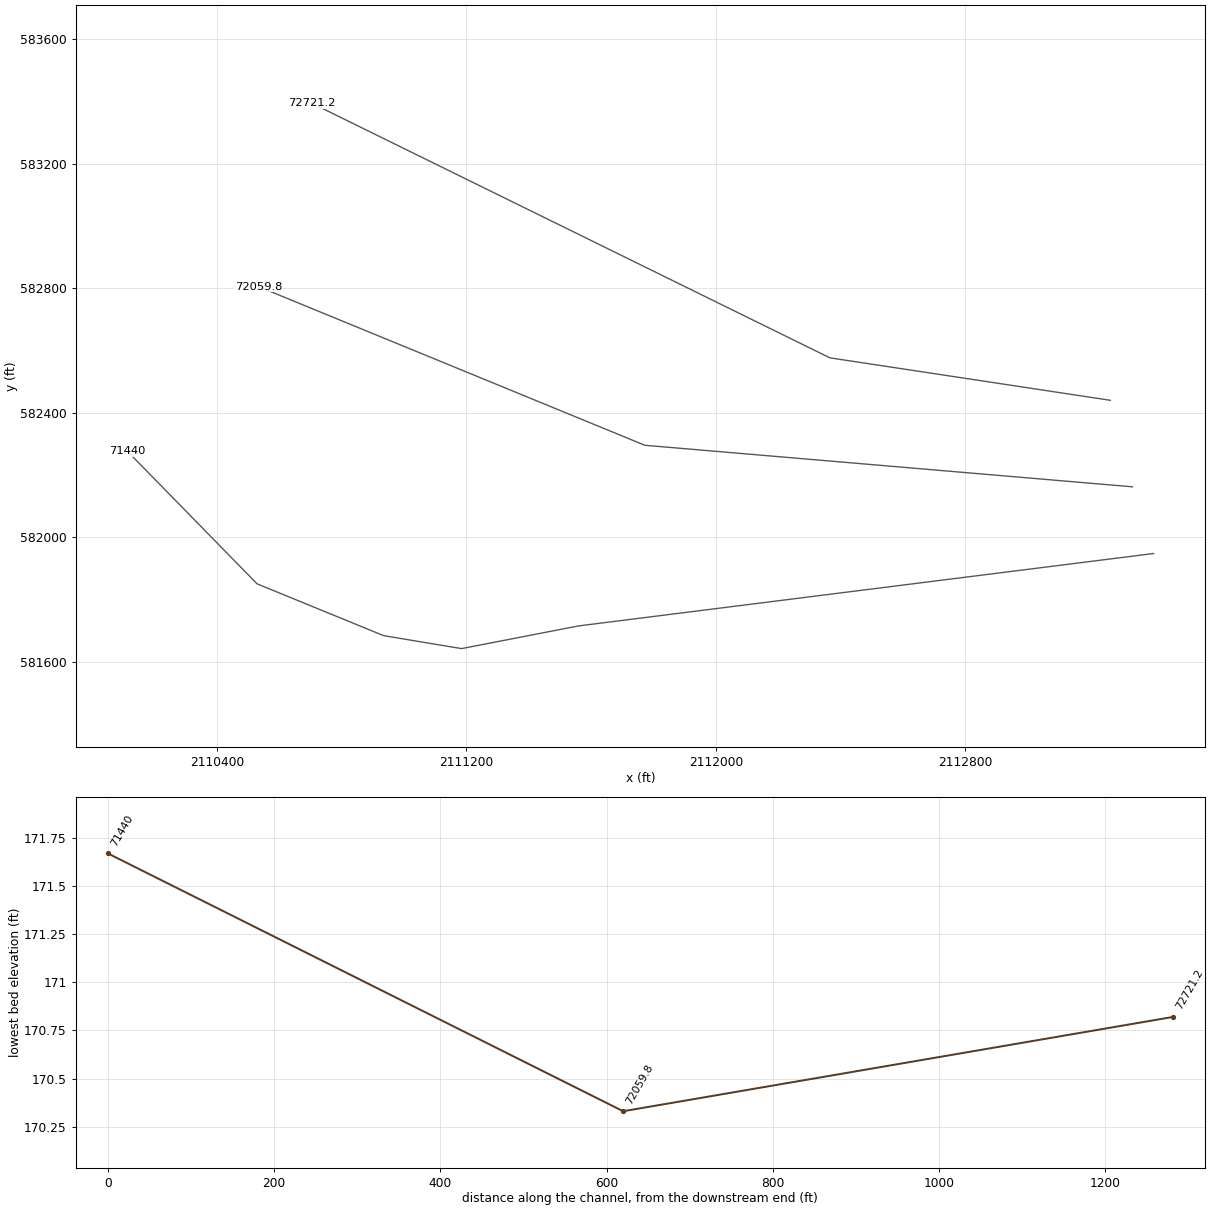
HEC-RAS study B4544BLACKRIVER.prj: B4544 BLACK RIVER SR1722

--- B4544BLACKRIVER.g02 (geometry) --- (continued)

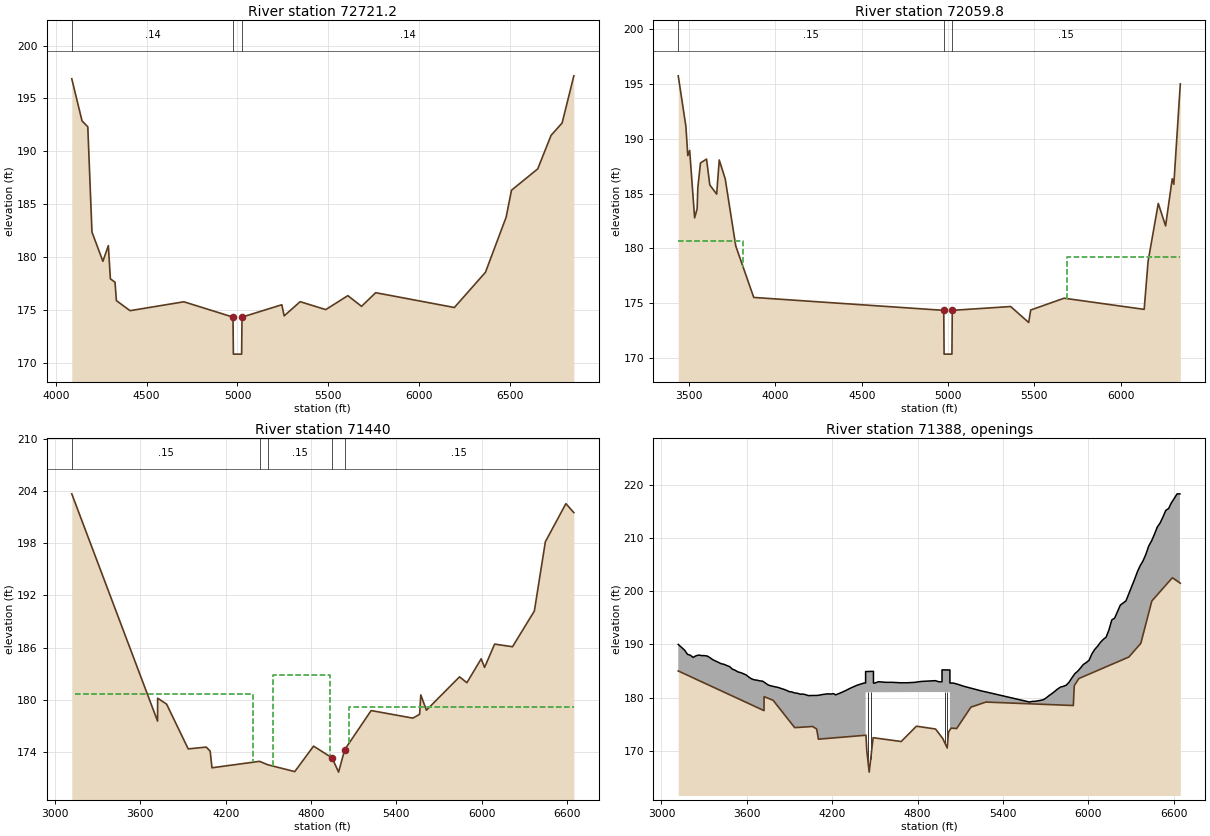
Type RM Length L Ch R = 1 ,72721.2 ,661.4067,661.4067,661.4067
BEGIN DESCRIPTION:
Black River 67.0
END DESCRIPTION:
XS GIS Cut Line= 3
2113264.67304935582440.3616858462112365.33393663582576.813068465
2110703.34709624 583395.52136418
#Sta/Elev= 30
  4088.2  196.86  4144.7  192.88  4176.4  192.32  4199.3  182.37  4259.5   179.6
  4289.4  181.08  4300.7  177.94  4326.2  177.62  4333.7  175.88  4408.9  174.93
    4705  175.77  4975.3  174.32  4977.3  170.82  5022.8  170.82  5024.8  174.32
  5243.8  175.49  5256.8  174.44  5344.7  175.78  5485.4  175.03  5607.1  176.35
  5682.5  175.34  5760.2  176.63  6193.2  175.23  6364.2  178.56    6478  183.77
  6507.4  186.32  6651.8  188.34  6725.3  191.51    6786  192.68  6850.5  197.14
#Mann= 3 , 1 , 0
  4088.2     .14       0  4975.3    .046       0  5024.8     .14       0
Bank Sta=4975.3,5024.8
XS Rating Curve= 0 ,0
Exp/Cntr=0.3,0.1

Type RM Length L Ch R = 1 ,72059.8 ,619.8,619.8,619.8
BEGIN DESCRIPTION:
Black River 66.0
END DESCRIPTION:
XS GIS Cut Line= 3
2113335.52376726582162.3188685252111772.06792525582295.790220949
2110532.48536495  582806.0153909
#Sta/Elev= 30
  3436.6  195.76    3481  191.14    3492  188.47  3502.9  188.94  3531.6  182.78
  3546.2  183.62  3550.2  185.55  3565.5   187.8  3600.6  188.15  3619.6  185.79
  3659.3  184.95  3674.3  188.07  3708.9  186.34    3770  180.21  3874.2  175.51
  4975.3  174.33  4977.3  170.33  5022.7  170.33  5024.7  174.33  5363.1  174.68
  5467.5  173.22  5479.2  174.36  5672.7  175.44  6136.8  174.42  6159.5  178.82
  6218.5   184.1  6260.9  182.05  6299.3  186.35  6308.6  185.85  6346.2  195.02
#Mann= 3 ,-1 , 0
  3436.6     .15       0  4975.3    .046       0  5024.7     .15       0
#XS Ineff= 2 , 0
        3812.875   180.75687.375           179.2
Permanent Ineff=
       F       F
Bank Sta=4975.3,5024.7
XS Rating Curve= 0 ,0
Exp/Cntr=0.5,0.3

Type RM Length L Ch R = 1 ,71440   ,119,119,119
XS GIS Cut Line= 6
2113403.44287169581947.9357585012111558.91670513581715.133402586
2111184.21863562581642.284466922 2110934.4166418581683.914633006
2110528.50505203581850.4461240922110112.17189521 582277.18050684
#Sta/Elev= 30
    3118  203.67    3721  177.54 3721.56  180.17 3784.62  179.49 3936.55  174.34
 4063.11  174.55 4090.97  174.08 4103.43  172.17 4437.78  172.91 4495.47  172.52
 4685.26  171.73 4817.61  174.66 4947.55  173.31 4993.49  171.67 5036.26  174.25
 5222.23  178.75 5515.67  177.88 5563.15  178.32 5571.28  180.55 5610.61  178.79
 5843.67  182.63 5895.16  181.95 5995.81   184.7 6019.59  183.71 6090.27  186.39
 6216.05  186.09 6369.59   190.2 6446.87  198.16 6591.26  202.54 6647.05  201.51
#Mann= 5 ,-1 , 0
    3118     .15       0 4437.78    .046       0 4495.47     .15       0
 4947.55    .046       0 5036.26     .15       0
#XS Ineff= 3 ,-1
    3140  4395.3   180.7 4529.95  4932.3  182.79 5067.45    6669   179.2
Permanent Ineff=
       F       F       F
Bank Sta=4947.55,5036.26
XS Rating Curve= 0 ,0
Exp/Cntr=0.5,0.3

Type RM Length L Ch R = 4 ,71388   ,,,
BEGIN DESCRIPTION:
Three Bridge Road TOR
END DESCRIPTION:
Bridge Culvert--1,0,-1,-1, 0
Deck Dist Width WeirC Skew NumUp NumDn MinLoCord MaxHiCord MaxSubmerge Is_Ogee
39.7,25,2.6,0, 156, 158, , , 0.98, 0, 0,0,,
    31183163.4153183.1863202.9573222.7283242.4983262.269 3282.043301.8113321.582
3341.3533361.1243380.8953400.6663420.4373439.8913459.3443478.7983498.2513517.704
3537.1583556.6113576.0643595.5183614.9713634.4253653.878 3672.653691.4233710.195
3728.968 3747.743766.5123785.2853804.0573822.8293841.6023860.3743879.1463897.919
3916.6913936.0393955.3873974.7353994.0834013.4314032.7794052.1274071.4754090.823
4110.1714129.5194149.479 4169.444189.4014209.362    4225    4250    4275    4300
    4325    4350    4375    4400    4425    4435    4435 4490.25 4490.25    4500
    4525    4550    4575    4600    4625    4650    4675    4700    4725    4750
    4775    4800    4825    4850    4875    4900    4925    4950    4972    4972
 5027.75 5027.75    5050    5075    5100    5125    5150    5175    5200    5225
    5250    52755586.649 5606.615626.5715646.5315666.4925686.4535706.4145726.374
5746.3355766.2955786.2565806.2175826.1785846.1385866.099 5886.065906.0215925.981
5945.9425965.9025985.8636005.8246025.7856045.7456065.7066085.6676105.6276125.588
6145.5496165.509 6185.476205.4316225.3926245.3526265.3136285.2736305.2346325.195
6345.1566365.1166385.0776405.0386424.9996444.959 6464.92 6484.886504.8416524.802
6544.7636564.7236584.6846604.6456624.6056644.566
     190 188.895 188.128 187.962 187.553 187.851 187.997 187.895  187.89 187.813
 187.498 187.118 186.861 186.611 186.363 186.252 186.024 185.827 185.357 185.138
 184.828 184.697 184.484 184.246 183.838 183.504 183.331 183.266 183.134 183.095
 182.768 182.405  182.22 182.099 181.991 181.886 181.702 181.549 181.355 181.117
 181.055 180.868 180.816 180.633  180.66  180.54 180.358  180.39 180.396 180.392
 180.454 180.559 180.626 180.702 180.655 180.732 180.503 180.786 181.065 181.385
 181.729 182.035 182.322 182.534  182.74  182.74  184.89  184.93 182.732 182.732
 182.972 182.931 182.866 182.861  182.86 182.826 182.788 182.786 182.785 182.815
 182.846 182.937 183.027 183.059 183.093 183.139 183.181 182.968 182.968 185.207
 185.187 182.728 182.728 182.562 182.337 182.123 181.947 181.764 181.579 181.398
 181.236 181.095 179.162 179.279 179.291 179.389  179.48 179.621 179.978  180.41
 180.774 181.216  181.64 181.985 182.114  182.35 182.924  183.75   184.5 184.957
 185.579 186.238 186.581 187.024  188.23 189.063  189.66 190.394 190.939 191.372
 192.743 194.605 194.951 196.173 197.392 197.801 198.198 199.562 200.891 202.213
 203.652 204.826 205.718 206.955 208.519 209.469 210.702 212.063 212.836 213.954
  215.21 215.558 216.668 217.475 218.326  218.31
                                                                                
                                                                                
                                                                                
                                                                                
                                                                                
                                                                                
                                                  180.97  181.01
                                                                                
                                                                          181.04
  181.02
                                                                                
                                                                                
                                                                                
                                                                                
                                                                                
                                                
    31183163.4153183.1863202.9573222.7283242.4983262.269 3282.043301.8113321.582
3341.3533361.1243380.8953400.6663420.4373439.8913459.3443478.7983498.2513517.704
3537.1583556.6113576.0643595.5183614.9713634.4253653.878 3672.653691.4233710.195
3728.968 3747.743766.5123785.2853804.0573822.8293841.6023860.3743879.1463897.919
3916.6913936.0393955.3873974.7353994.0834013.4314032.7794052.1274071.4754090.823
4110.1714129.5194149.479 4169.444189.4014209.362    4225    4250    4275    4300
    4325    4350    4375    4400    4425    4435    4435 4490.25 4490.25    4500
    4525    4550    4575    4600    4625    4650    4675    4700    4725    4750
    4775    4800    4825    4850    4875    4900    4925    4950    4972    4972
 5027.75 5027.75    5050    5075    5100    5125    5150    5175    5200    5225
    5250    52755586.649 5606.615626.5715646.5315666.4925686.4535706.4145726.374
5746.3355766.2955786.2565806.2175826.1785846.1385866.099 5886.065906.0215925.981
5945.9425965.9025985.8636005.8246025.7856045.7456065.7066085.6676105.6276125.588
6145.5496165.509 6185.476205.4316225.3926245.3526265.3136285.2736305.2346325.195
6345.1566365.1166385.0776405.0386424.9996444.959 6464.92 6484.886504.8416524.802
6544.7636564.7236584.6846604.6456624.6056644.5666664.527 6669.94
     190 188.895 188.128 187.962 187.553 187.851 187.997 187.895  187.89 187.813
 187.498 187.118 186.861 186.611 186.363 186.252 186.024 185.827 185.357 185.138
 184.828 184.697 184.484 184.246 183.838 183.504 183.331 183.266 183.134 183.095
 182.768 182.405  182.22 182.099 181.991 181.886 181.702 181.549 181.355 181.117
 181.055 180.868 180.816 180.633  180.66  180.54 180.358  180.39 180.396 180.392
 180.454 180.559 180.626 180.702 180.655 180.732 180.503 180.786 181.065 181.385
 181.729 182.035 182.322 182.534  182.74  182.74  184.86  184.94 182.732 182.732
 182.972 182.931 182.866 182.861  182.86 182.826 182.788 182.786 182.785 182.815
 182.846 182.937 183.027 183.059 183.093 183.139 183.181 182.968 182.968 185.197
 185.197 182.728 182.728 182.562 182.337 182.123 181.947 181.764 181.579 181.398
 181.236 181.095 179.162 179.279 179.291 179.389  179.48 179.621 179.978  180.41
 180.774 181.216  181.64 181.985 182.114  182.35 182.924  183.75   184.5 184.957
 185.579 186.238 186.581 187.024  188.23 189.063  189.66 190.394 190.939 191.372
 192.743 194.605 194.951 196.173 197.392 197.801 198.198 199.562 200.891 202.213
 203.652 204.826 205.718 206.955 208.519 209.469 210.702 212.063 212.836 213.954
  215.21 215.558 216.668 217.475 218.326  218.31 219.311     220
                                                                                
                                                                                
                                                                                
                                                                                
                                                                                
                                                                                
                                                  180.94  181.02
                                                                                
                                                                          181.03
  181.03
                                                                                
                                                                                
                                                                                
                                                                                
                                                                                
                                                                
Pier Skew, UpSta & Num, DnSta & Num=  ,4454.125, 2 ,4454.125, 2 , 0 , 0 , 0 ,,
       2       2
     170     184
       2       2
     170     184
Pier Skew, UpSta & Num, DnSta & Num=  ,4471.125, 2 ,4471.125, 2 , 0 , 0 , 0 ,,
       2       2
     170     184
       2       2
     170     184
Pier Skew, UpSta & Num, DnSta & Num=  ,4991.375, 2 ,4991.375, 2 , 0 , 0 , 0 ,,
       2       2
     170     184
       2       2
     170     184
Pier Skew, UpSta & Num, DnSta & Num=  ,5008.375, 2 ,5008.375, 2 , 0 , 0 , 0 ,,
       2       2
     170     184
       2       2
     170     184
Abutment Skew #Up #Dn= , 3 , 3
    4435    4436    4436
  180.97  180.97     170
    4435    4436    4436
  180.94  180.94     170
Abutment Skew #Up #Dn= , 3 , 3
 4489.25 4489.25 4490.25
     170  181.01  181.01
 4489.25 4489.25 4490.25
     170  181.02  181.02
Abutment Skew #Up #Dn= , 3 , 3
    4972    4973    4973
  181.04  181.04     171
    4972    4973    4973
  181.03  181.03     171
Abutment Skew #Up #Dn= , 3 , 3
 5026.75 5026.75 5027.75
     171  181.02  181.02
 5026.75 5026.75 5027.75
     171  181.03  181.03
BR Coef=-1 , 1 , 0 ,0.9, 0 ,,,0.8,0,1.2,0,
WSPro=,,,, 1 ,,,, 0 ,,,, 0 ,,,,-1 ,-1 ,-1 , 0 , 0 , 0 , 0 , 0
BR Coef=-1 , 1 , 0 ,1.05, 0 ,,,0.8,0,1.2,0,
WSPro=,,,, 1 ,,,, 0 ,,,, 0 ,,,,-1 ,-1 ,-1 , 0 , 0 , 0 , 0 , 0
BC Mult= 3 ,3118,4800,3140,4800
BC Mult= 3 ,4800,6690,4800,6690
BR U #Sta/Elev= 30
    3118     185    3721  177.54 3721.56  180.17 3784.62  179.49 3936.55  174.34
 4063.11  174.55 4090.97  174.08 4103.43  172.17 4437.78  172.91  4443.3  170.03
  4460.3  165.97 4487.76  172.45 4685.26  171.73 4792.23  174.61 4926.77  174.08
 4977.54  172.28  5008.3  170.53  5017.8  173.51 5036.26  174.25  5075.2  174.17
 5175.12  178.19 5280.95  179.15 5895.16   178.5 5901.67  182.24 5934.19  183.58
 6285.37  187.62 6369.59   190.2 6446.87  198.16 6591.26  202.54 6647.05  201.51
BR U #Mann= 5
    3118     .15 4437.78    .046 4487.76     .15 4926.77    .046 5036.26     .15
BR U Banks=4977.54,5017.8
BR D #Sta/Elev= 30
    3140     185    3788  176.24 3978.08  179.81    4028  173.67 4085.41  176.66
 4139.81  176.62 4177.83  173.11  4436.7  174.68  4451.2  168.36    4460  167.55
  4483.9  172.52 4801.27  176.28 4830.65  175.09 4970.91  173.33  4982.5  169.37
  4999.5  171.03  5016.4  175.83 5042.58  175.85 5104.35  178.72 5155.27  178.86
 5398.86  178.64  5570.8  176.43 5631.61  178.06 5946.01  178.05 5951.19  182.14
 6140.19  184.51  6235.1   187.7 6296.52  185.41 6468.15  193.31 6669.94  198.53
BR D #Mann= 5
    3140     .15  4436.7    .046  4483.9     .15 4830.65    .046 5042.58     .15
BR D Banks=4970.91,5016.4
BC Design=,, 0 ,, 0 ,,,,,,
BC Use User HTab Curves=0
BC User HTab FreeFlow(D)= 0