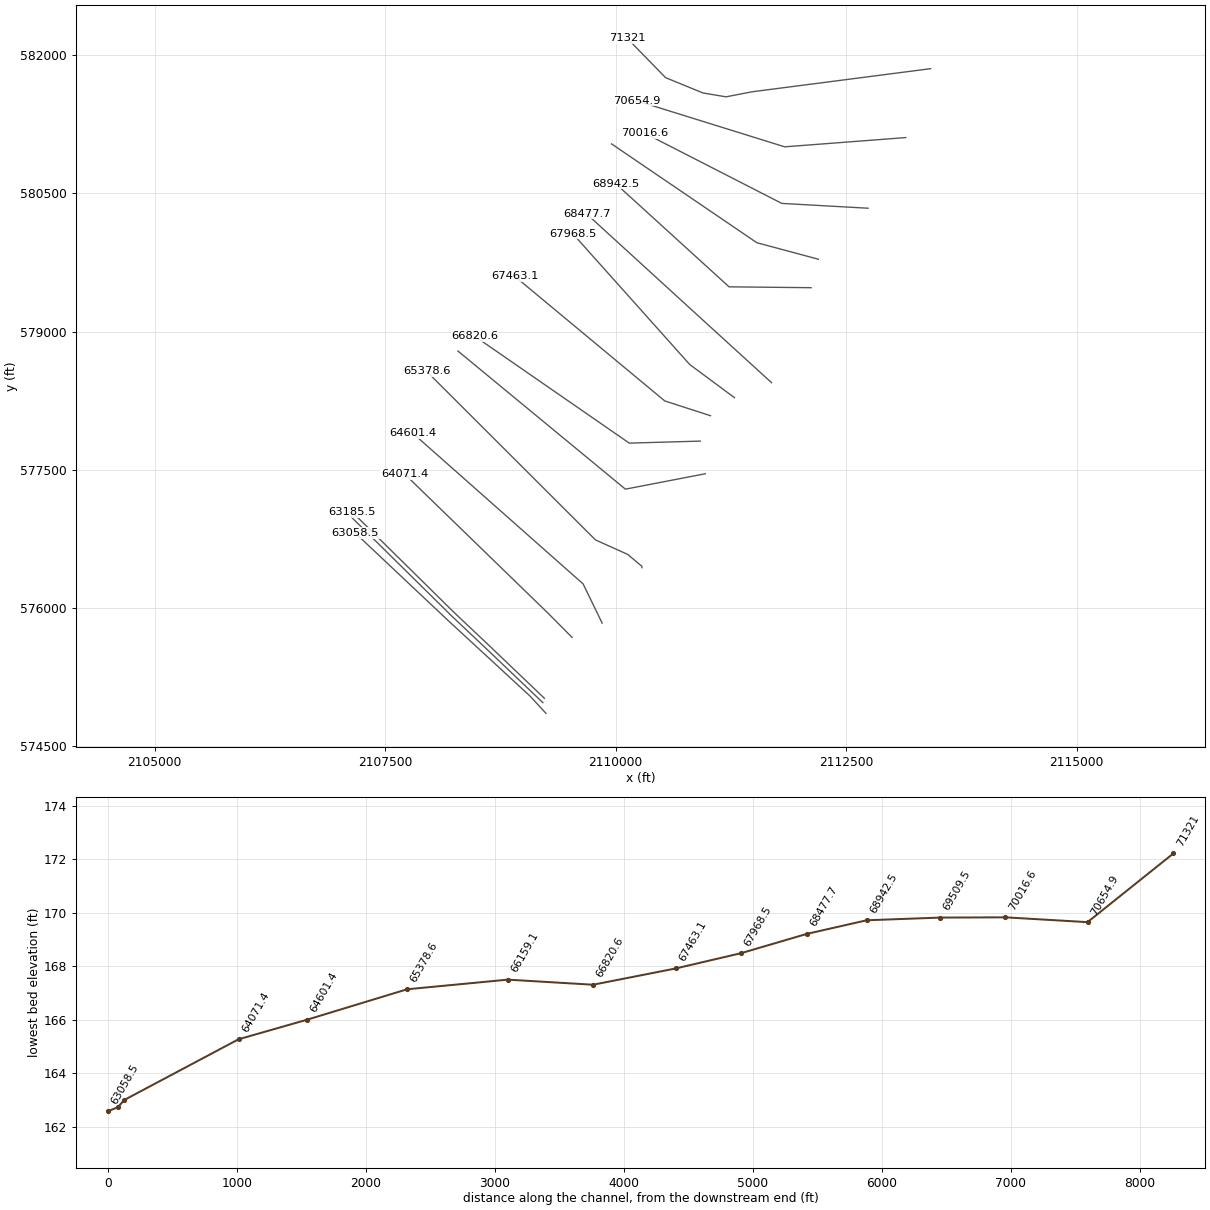
HEC-RAS study B4544BLACKRIVER.prj: B4544 BLACK RIVER SR1722

--- B4544BLACKRIVER.g02 (geometry) --- (continued)

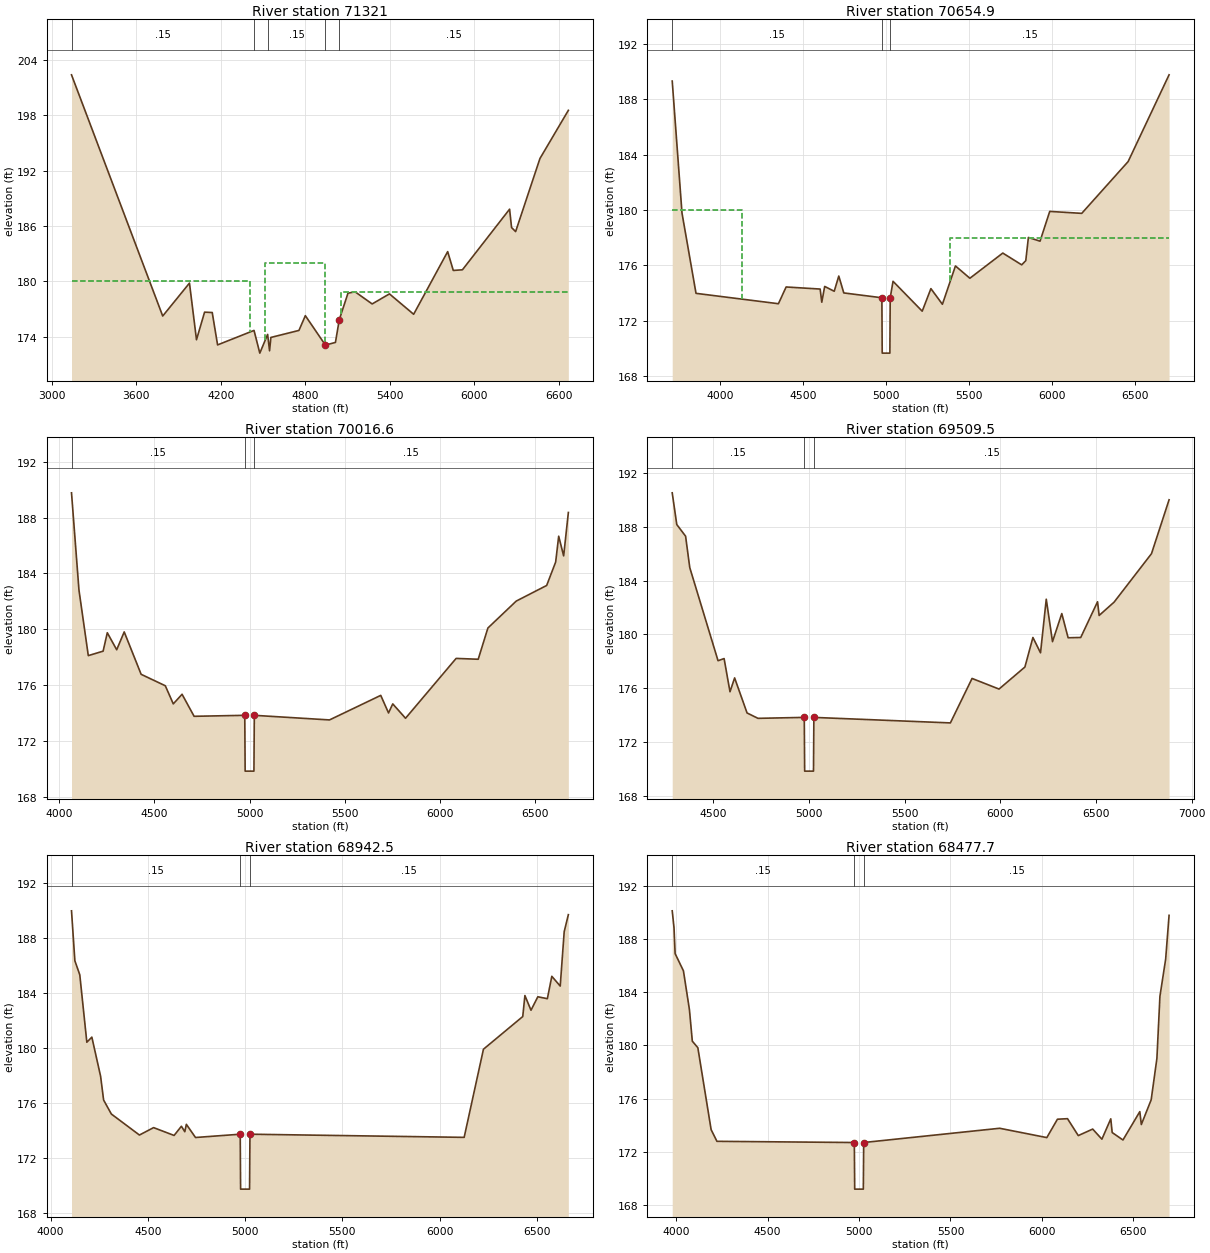
Type RM Length L Ch R = 1 ,71321   ,666.1,666.1,666.1
XS GIS Cut Line= 6
2113417.59376204581853.6701990072111477.28104162581602.232053578
2111198.36985403581548.0034874982110948.56786022581589.633653581
2110542.65627044581756.1648165882110126.31753621582182.899199337
#Sta/Elev= 30
    3140  202.38    3788  176.24 3978.08  179.81    4028  173.67 4085.41  176.66
 4139.81  176.62 4177.83  173.11  4436.7  174.68 4477.87  172.22 4533.33  174.25
 4547.15  172.47 4556.37  173.92 4755.91  174.68 4801.27  176.28 4943.86  173.09
 5015.14  173.38 5042.58  175.85 5104.35  178.72 5155.27  178.86 5275.98  177.55
 5398.86  178.64  5570.8  176.43 5812.54  183.22 5852.43  181.18 5917.35  181.25
 6252.39  187.82 6266.47  185.83 6295.33  185.39 6468.15  193.31 6669.94  198.53
#Mann= 5 ,-1 , 0
    3140     .15       0  4436.7    .046       0 4533.33     .15       0
 4943.86    .046       0 5042.58     .15       0
#XS Ineff= 3 ,-1
    3140 4407.85     180  4517.4  4943.5     182  5054.9    6669   178.8
Permanent Ineff=
       F       F       F
Bank Sta=4943.86,5042.58
XS Rating Curve= 0 ,0
Exp/Cntr=0.5,0.3

Type RM Length L Ch R = 1 ,70654.9 ,638.3065,638.3065,638.3065
BEGIN DESCRIPTION:
Black River 65.0
END DESCRIPTION:
XS GIS Cut Line= 3
2113148.02186736581105.6981621182111834.51855804 581005.17714357
2110233.34233383581503.702194968
#Sta/Elev= 30
  3711.4  189.31  3770.3  179.77  3854.8  173.97  4351.5  173.22  4397.8  174.43
  4602.9  174.28  4612.7  173.33  4630.3  174.47  4687.7  174.12  4715.2  175.22
  4745.4     174  4974.9  173.65  4976.9  169.65  5023.1  169.65  5025.1  173.65
  5042.2  174.84    5218  172.68  5270.4  174.31  5339.7  173.18  5418.3  175.95
  5505.3  175.06  5703.6  176.88  5817.4  176.03  5842.1  176.33  5857.9  178.01
  5928.1  177.74  5986.5  179.89  6179.5  179.75  6458.9  183.49  6705.7  189.76
#Mann= 3 ,-1 , 0
  3711.4     .15       0  4974.9    .046       0  5025.1     .15       0
#XS Ineff= 2 , 0
        4132.175     1805388.075             178
Permanent Ineff=
       F       F
Bank Sta=4974.9,5025.1
XS Rating Curve= 0 ,0
Exp/Cntr=0.3,0.1

Type RM Length L Ch R = 1 ,70016.6 ,507.1051,507.1051,507.1051
BEGIN DESCRIPTION:
Black River 64.0
END DESCRIPTION:
XS GIS Cut Line= 3
2112738.75772042580338.800391383 2111803.2882416580391.090921227
2110312.12313209581155.118662881
#Sta/Elev= 30
  4063.9  189.78  4103.2   182.8  4152.2  178.11  4230.1  178.43  4252.1  179.75
  4301.5  178.53    4341  179.81    4430  176.77  4557.1  175.95  4599.1  174.65
  4645.2  175.34  4708.5  173.76  4974.9  173.83  4976.9  169.83  5023.1  169.83
  5025.1  173.83  5420.5   173.5  5689.9  175.26  5730.8     174    5753  174.65
  5820.2  173.62  6086.2  177.91  6202.3  177.85  6253.3  180.09  6402.3  182.02
  6562.3  183.14  6609.6  184.82  6625.5  186.67  6651.6  185.26  6676.3  188.37
#Mann= 3 , 1 , 0
  4063.9     .15       0  4974.9    .046       0  5025.1     .15       0
Bank Sta=4974.9,5025.1
XS Rating Curve= 0 ,0
Exp/Cntr=0.3,0.1

Type RM Length L Ch R = 1 ,69509.5 ,567.0057,567.0057,567.0057
BEGIN DESCRIPTION:
Black River 63.0
END DESCRIPTION:
XS GIS Cut Line= 3
2112199.99226127579785.3147830872111532.67549956579964.356597261
2109956.65953029581037.007466097
#Sta/Elev= 30
  4284.6  190.54  4308.4  188.18  4354.5  187.31  4376.2  184.98  4524.1  178.04
  4555.8   178.2  4586.6  175.73  4610.8  176.76  4675.8  174.15    4733  173.75
  4974.9  173.82  4976.9  169.82  5023.1  169.82  5025.1  173.82  5738.7  173.41
    5852  176.72  5992.9  175.93  6128.3  177.57  6170.1  179.77  6209.9  178.63
  6239.9  182.62  6272.5  179.46  6321.1  181.55  6354.1  179.75  6420.1  179.77
    6508  182.43  6516.4  181.41  6594.4   182.4    6790  186.01  6881.9  190.02
#Mann= 3 , 1 , 0
  4284.6     .15       0  4974.9    .046       0  5025.1     .15       0
Bank Sta=4974.9,5025.1
XS Rating Curve= 0 ,0
Exp/Cntr=0.3,0.1

Type RM Length L Ch R = 1 ,68942.5 ,464.8047,464.8047,464.8047
BEGIN DESCRIPTION:
Black River 62.0
END DESCRIPTION:
XS GIS Cut Line= 3
2112120.49145572579476.2116510422111230.84244118579485.581745986
 2109999.6899663580606.703105957
#Sta/Elev= 30
  4107.4  189.99  4124.7  186.35    4150  185.33  4186.2  180.42    4212  180.79
  4256.9  177.95  4272.5  176.21  4312.3  175.19  4456.7  173.66  4529.5   174.2
  4634.9  173.63  4672.5   174.3    4690   173.9    4698  174.44    4745  173.48
  4974.9  173.72  4976.9  169.72    5023  169.72    5025  173.72  6126.4  173.49
  6225.6  179.91  6427.7  182.29  6438.8  183.82  6470.1  182.75  6505.3  183.73
  6554.2  183.59  6577.2  185.22  6620.4  184.51  6640.8  188.47  6662.2  189.71
#Mann= 3 , 1 , 0
  4107.4     .15       0  4974.9    .046       0    5025     .15       0
Bank Sta=4974.9,5025
XS Rating Curve= 0 ,0
Exp/Cntr=0.3,0.1

Type RM Length L Ch R = 1 ,68477.7 ,509.2052,509.2052,509.2052
BEGIN DESCRIPTION:
Black River 61.0
END DESCRIPTION:
XS GIS Cut Line= 3
2111691.73711128578445.5112072772110939.40948818579131.698160194
2109685.57678349580277.729772574
#Sta/Elev= 30
  3978.6  190.11  3988.5  188.82  3994.4   186.9    4040   185.6  4072.7  182.69
  4088.5  180.32  4118.7  179.83  4191.3  173.68  4223.1   172.8  4974.4  172.71
  4976.4  169.21  5023.6  169.21  5025.6  172.71  5769.1  173.78    6027  173.08
  6085.1  174.46  6140.2   174.5    6199  173.23  6277.8  173.72  6328.2  172.96
  6376.8  174.49  6384.4  173.46  6443.3   172.9  6535.5  175.03  6543.8  174.06
  6597.7  175.92    6629  179.03  6645.5  183.69  6676.8  186.48  6695.5  189.77
#Mann= 3 , 1 , 0
  3978.6     .15       0  4974.4    .046       0  5025.6     .15       0
Bank Sta=4974.4,5025.6
XS Rating Curve= 0 ,0
Exp/Cntr=0.3,0.1

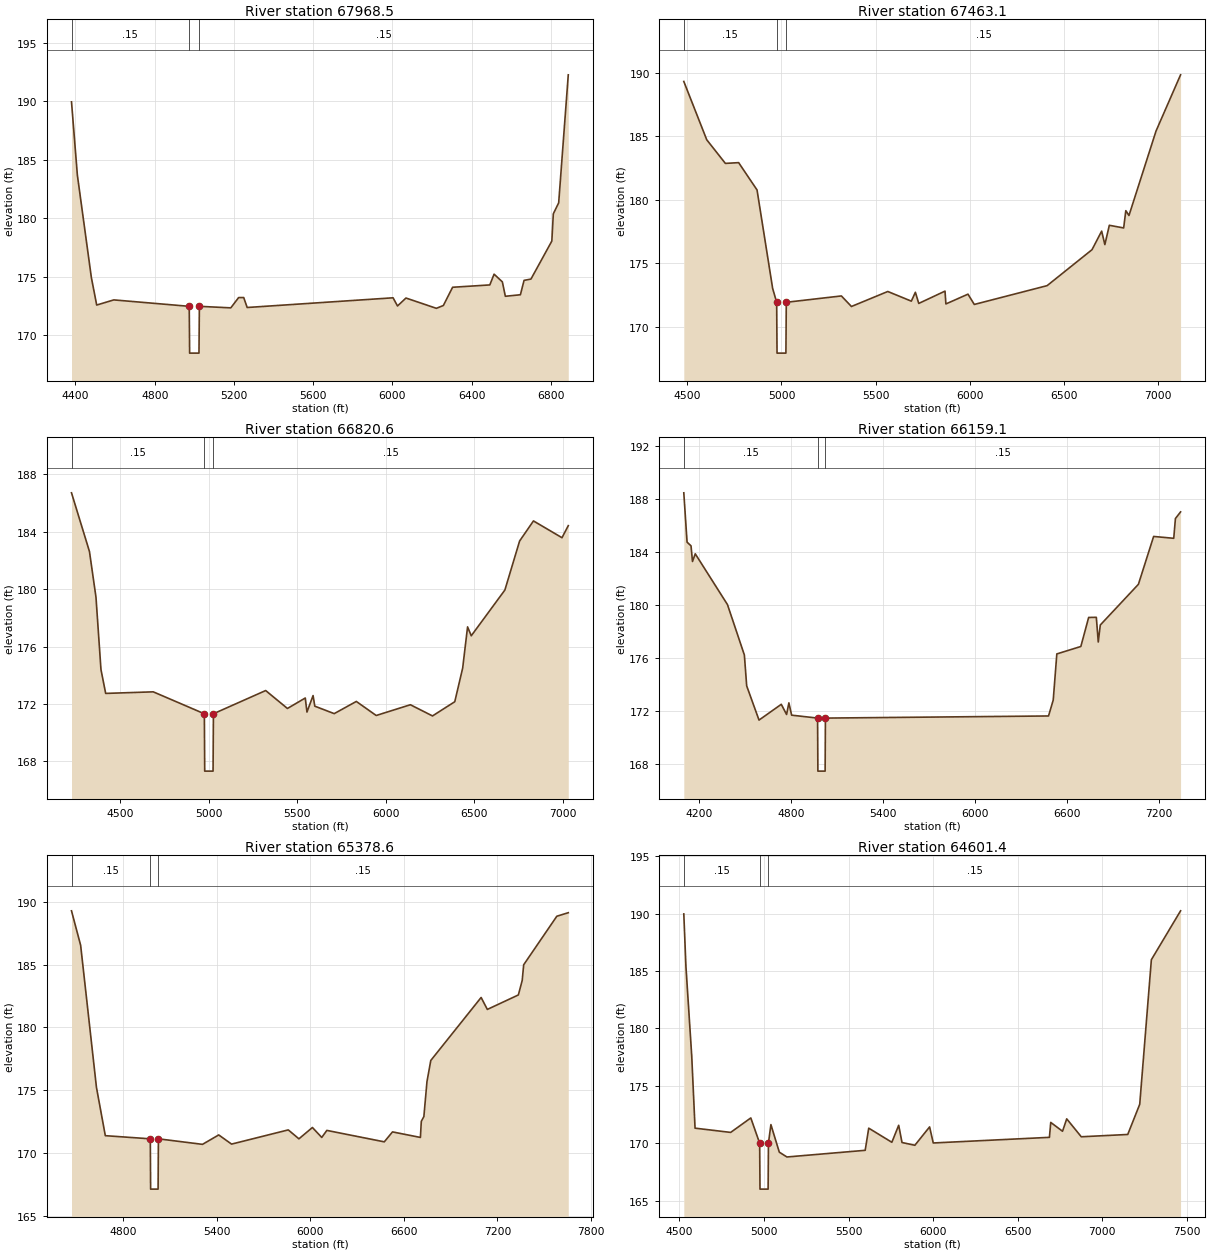
Type RM Length L Ch R = 1 ,67968.5 ,505.4051,505.4051,505.4051
BEGIN DESCRIPTION:
Black River 60.0
END DESCRIPTION:
XS GIS Cut Line= 3
2111289.99304054578282.1995524912110804.10811722578642.513203436
2109536.29527087580061.977586424
#Sta/Elev= 30
    4380  189.97  4409.6  183.71  4480.3  174.95  4507.2   172.6  4593.5  173.04
  4974.4  172.49  4976.4  168.49  5023.6  168.49  5025.6  172.49  5184.2  172.36
  5223.9  173.24  5249.5  173.24  5266.9  172.39  6003.5  173.22  6025.9  172.52
  6068.7   173.2  6222.1  172.32  6257.4  172.56  6304.1  174.12  6491.9  174.32
  6513.5  175.24  6555.3  174.58  6570.4  173.35  6646.4  173.48  6664.9  174.71
  6699.7  174.82  6805.1  178.07  6812.6   180.4  6839.7  181.34  6888.1  192.28
#Mann= 3 , 1 , 0
    4380     .15       0  4974.4    .046       0  5025.6     .15       0
Bank Sta=4974.4,5025.6
XS Rating Curve= 0 ,0
Exp/Cntr=0.3,0.1

Type RM Length L Ch R = 1 ,67463.1 ,642.5065,642.5065,642.5065
BEGIN DESCRIPTION:
Black River 59.0
END DESCRIPTION:
XS GIS Cut Line= 3
2111029.36039963578086.7275718342110533.49537518578247.009195918
2108903.47885874579601.912924733
#Sta/Elev= 30
  4480.8   189.3  4602.7  184.71  4701.8  182.85  4772.3  182.91  4870.1  180.76
  4953.1  173.01  4974.4  171.92  4976.4  167.92  5023.6  167.92  5025.6  171.92
  5318.4  172.42  5371.9  171.59  5565.1  172.77  5690.4  172.01  5711.8  172.71
  5729.8  171.83  5869.3   172.8    5874  171.79  5991.4  172.56    6025  171.75
    6412  173.23  6650.8  176.06    6702  177.52    6719  176.46  6742.8  177.98
    6819  177.77  6830.4  179.13  6847.2  178.75  6991.1   185.4  7121.5  189.82
#Mann= 3 , 1 , 0
  4480.8     .15       0  4974.4    .045       0  5025.6     .15       0
Bank Sta=4974.4,5025.6
XS Rating Curve= 0 ,0
Exp/Cntr=0.3,0.1

Type RM Length L Ch R = 1 ,66820.6 ,661.5067,661.5067,661.5067
BEGIN DESCRIPTION:
Black River 58.0
END DESCRIPTION:
XS GIS Cut Line= 3
2110918.54927681577811.0447784272110148.39147305577789.044555506
2108474.19450893578948.106299915
#Sta/Elev= 30
  4223.8  186.72  4325.2  182.63  4362.1  179.44  4390.3  174.39  4416.9  172.73
  4685.7  172.84  4974.4  171.31  4976.4  167.31  5023.6  167.31  5025.6  171.31
  5320.8  172.93  5443.8  171.68  5544.6  172.41  5554.1  171.43  5588.7  172.58
  5598.4  171.84  5708.1  171.32    5833  172.17  5945.4  171.19  6138.4  171.94
  6263.4  171.16  6389.2  172.15  6433.9   174.5  6461.5  177.37  6482.4  176.75
  6672.3  179.94  6755.6  183.36  6833.8  184.76    6995  183.59  7030.5  184.43
#Mann= 3 , 1 , 0
  4223.8     .15       0  4974.4    .045       0  5025.6     .15       0
Bank Sta=4974.4,5025.6
XS Rating Curve= 0 ,0
Exp/Cntr=0.3,0.1

Type RM Length L Ch R = 1 ,66159.1 ,780.5079,780.5079,780.5079
BEGIN DESCRIPTION:
Black River 57.0
END DESCRIPTION:
XS GIS Cut Line= 3
  2110972.649825 577456.441185342110106.76105122577289.449493265
2108289.90264156578788.724684951
#Sta/Elev= 30
  4102.6  188.49  4123.9  184.77  4149.7  184.49  4159.1  183.31  4177.3  183.89
  4387.2  180.06  4497.3  176.26  4512.4  173.93  4592.8  171.35  4737.9  172.54
  4772.4  171.77  4787.4  172.65  4805.4  171.72  4974.4   171.5  4976.4   167.5
  5023.6   167.5  5025.5   171.5  6479.5  171.66  6510.1  172.86  6533.6  176.34
    6690   176.9    6741  179.09    6791   179.1  6803.6  177.24  6816.8  178.52
  7065.2  181.59  7164.4   185.2  7295.5  185.06  7306.4  186.55    7340  187.05
#Mann= 3 , 1 , 0
  4102.6     .15       0  4974.4    .044       0  5025.5     .15       0
Bank Sta=4974.4,5025.5
XS Rating Curve= 0 ,0
Exp/Cntr=0.3,0.1

Type RM Length L Ch R = 1 ,65378.6 ,777.2079,777.2079,777.2079
BEGIN DESCRIPTION:
Black River 55.0
END DESCRIPTION:
XS GIS Cut Line= 5
2110286.43287178576437.4108598242110284.97285698576452.001007662
2110131.81130505576581.0823156022109781.72775776576738.623911922
 2107952.0392181578566.752435776
#Sta/Elev= 30
  4468.8  189.27  4527.4  186.53  4628.8  175.23  4685.6  171.39  4974.1  171.14
  4976.1  167.14    5024  167.14    5026  171.14  5308.8   170.7  5412.8  171.45
  5495.1  170.72  5858.7  171.85    5927  171.14  6013.5  172.04  6073.4  171.25
  6106.1  171.81  6474.3   170.9  6527.1  171.69    6706  171.25  6711.7  172.53
  6728.2  172.91    6748  175.68  6772.5  177.37  7095.3  182.38  7135.2  181.43
    7334  182.58  7358.8  183.74  7368.1  184.98  7580.7  188.84  7654.1  189.12
#Mann= 3 , 1 , 0
  4468.8     .15       0  4974.1    .044       0    5026     .15       0
Bank Sta=4974.1,5026
XS Rating Curve= 0 ,0
Exp/Cntr=0.3,0.1

Type RM Length L Ch R = 1 ,64601.4 ,530.0054,530.0054,530.0054
BEGIN DESCRIPTION:
Black River 52.0
END DESCRIPTION:
XS GIS Cut Line= 3
2109854.16849178575835.7247631282109647.93640209576260.809070374
2107802.39770183577894.815627251
#Sta/Elev= 30
  4525.5  189.97    4538  185.42  4572.4  177.59    4592  171.31  4802.6  170.94
  4921.7   172.2    4974     170    4976     166    5024     166    5026     170
  5040.5  171.62  5090.2  169.22  5135.2   168.8    5598  169.38    5619  171.31
  5755.7  170.08  5796.1  171.56  5815.8  170.06  5891.7  169.82  5978.9  171.42
  6000.5  170.02  6687.4  170.51  6695.3  171.81  6764.9  171.04  6789.7  172.12
  6875.7  170.56  7150.5  170.76  7221.4  173.39  7290.2  185.98  7462.9  190.24
#Mann= 3 , 1 , 0
  4525.5     .15       0    4974    .044       0    5026     .15       0
Bank Sta=4974,5026
XS Rating Curve= 0 ,0
Exp/Cntr=0.3,0.1

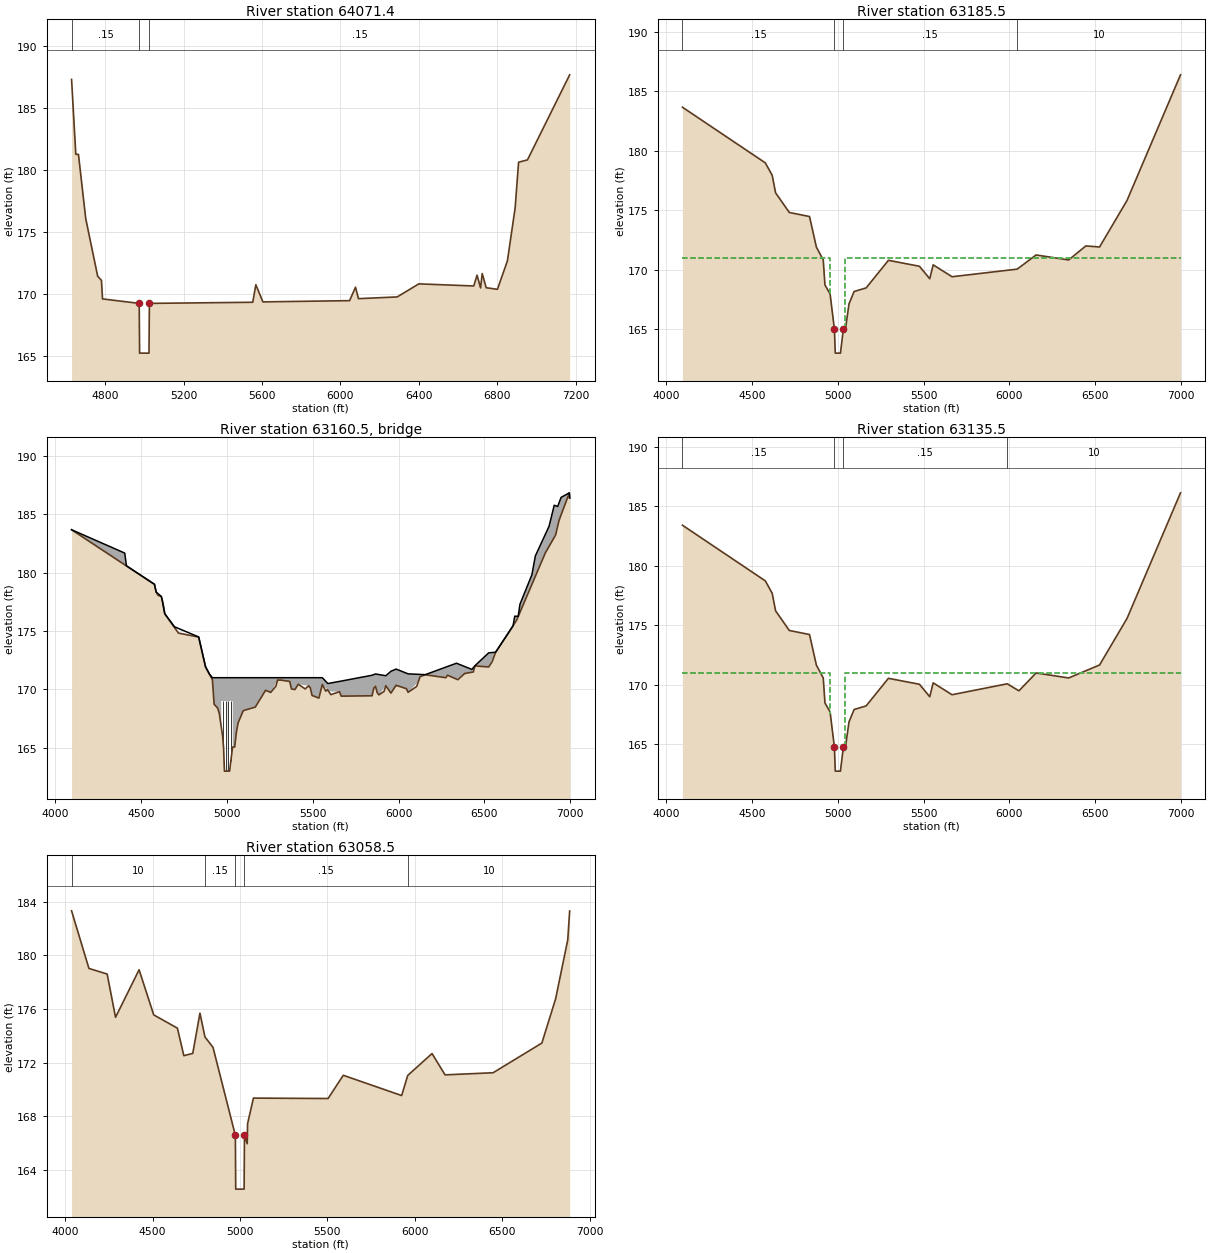
Type RM Length L Ch R = 1 ,64071.4 ,885.909,885.909,885.909
BEGIN DESCRIPTION:
Black River 51.0
END DESCRIPTION:
XS GIS Cut Line= 3
2109527.77518454575680.3631888972109274.10261415575936.385783094
2107710.61677184 577454.71116781
#Sta/Elev= 30
  4629.2  187.28  4650.8  181.26  4664.4  181.25  4701.4  176.09  4762.4  171.45
  4781.6  171.12    4787  169.63  4974.1  169.27  4976.1  165.27    5024  165.27
    5026  169.27  5553.1  169.36  5568.8  170.77  5604.9  169.39  6046.9  169.49
    6077  170.57  6092.3  169.65  6289.7  169.79  6399.9  170.84  6680.1  170.67
  6696.7  171.54  6714.8  170.51  6723.1  171.67  6743.4  170.53  6800.6   170.4
  6851.6  172.69    6891  176.95  6908.5  180.62  6953.9  180.81    7169  187.65
#Mann= 3 , 1 , 0
  4629.2     .15       0  4974.1    .044       0    5026     .15       0
Bank Sta=4974.1,5026
XS Rating Curve= 0 ,0
Exp/Cntr=0.5,0.3

Type RM Length L Ch R = 1 ,63185.5 ,50.0005,50.0005,50.0005
BEGIN DESCRIPTION:
Upstream Section of Bridge/Culvert/Weir
END DESCRIPTION:
XS GIS Cut Line= 4
2109227.85214551575019.3064906172108629.32608083575590.912282519
2108246.86220545575952.2659440032107143.36102401577040.786973646
#Sta/Elev= 30
  4093.8  183.67  4577.1  178.99  4617.1  177.95  4637.1  176.47  4717.1  174.82
  4834.8  174.48  4874.8  171.91  4914.8  170.83  4924.8  168.73  4954.8  167.97
    4980     165    4985     163    5015     163    5032     165  5044.8  165.06
  5064.8  167.13  5094.8  168.18  5164.8  168.48  5294.8   170.8  5475.7   170.3
  5535.7  169.25  5555.7  170.42  5665.7  169.42  6045.7  170.06  6155.7  171.25
  6345.7  170.83  6445.7  172.01  6525.7  171.92  6685.7  175.83  6997.6  186.39
#Mann= 4 ,-1 , 0
  4093.8     .15       0    4980     .05       0    5032     .15       0
  6045.7      10       0
#XS Ineff= 2 , 0
       0    4956     171    5044       0     171
Permanent Ineff=
       F       F
Bank Sta=4980,5032
XS Rating Curve= 0 ,0
Exp/Cntr=0.5,0.3

Type RM Length L Ch R = 3 ,63160.5 ,,,
BEGIN DESCRIPTION:
Railroad Bridge #2 (Black R.) TOR
Structure ID: Railroad Bridge #2 (Black R.)-est
Approximate Survey Structure
END DESCRIPTION:
Bridge Culvert--1,0,-1,-1, 0
Deck Dist Width WeirC Skew NumUp NumDn MinLoCord MaxHiCord MaxSubmerge Is_Ogee
10,30,2.6,0, 60, 60, , , 0.95, 0, 1,1,,
  4093.8  4403.8  4413.8  4577.1  4587.1  4617.1  4637.1  4693.8  4834.8  4874.8
  4897.2  4914.8  4924.8  4954.8 4966.41  4966.5 5033.39  5033.5  5044.8  5064.8
  5094.8  5164.8  5224.8  5254.8  5294.8  5365.7  5375.7  5395.7  5415.7  5475.7
  5495.7  5535.7  5555.7  5587.6  5665.7  5845.7  5865.7  5885.7  5925.7  5955.7
  5985.7  6055.7  6155.7  6337.6  6427.6  6445.7  6525.7  6565.7  6667.6  6677.6
  6697.6  6707.6  6777.6  6797.6  6877.6  6907.6  6927.6  6947.6  6995.7  6997.6
  183.67  181.67  180.58     179  178.33  177.96  176.48  175.36  174.49  171.95
  171.32     171     171     171     171     171     171     171     171     171
     171     171     171     171     171     171     171     171     171     171
     171     171     171   170.5  170.71  171.21  171.32  171.27  171.17  171.55
  171.74  171.33  171.26  172.24  171.71  172.03  173.13  173.18  175.44  176.27
  176.25  177.28  179.82  181.43  183.97  185.77  185.66  186.44  186.83  186.39
  183.67  180.67  180.57  178.99  178.32  177.95  176.47   175.3  174.48  171.91
  171.31  170.83  168.73  167.97   166.8     169     169  165.04  165.06  167.13
  168.18  168.48  169.92  169.74   170.8  170.68  170.04  169.98  170.44   170.3
  169.48  169.25  170.42  169.94  169.42  169.45  170.26  169.53  170.31  169.68
  170.35  169.75  171.25  170.88  171.47  172.01  171.92  173.17  175.43  175.65
  176.24  176.58  178.99  179.68  182.24  183.01  183.96  184.94  186.82  186.39
  4093.8  4403.8  4413.8  4577.1  4587.1  4617.1  4637.1  4693.8  4834.8  4874.8
  4897.2  4914.8  4924.8  4954.8 4966.41  4966.5 5033.39  5033.5  5044.8  5064.8
  5094.8  5164.8  5224.8  5254.8  5294.8  5365.7  5375.7  5395.7  5415.7  5475.7
  5495.7  5535.7  5555.7  5587.6  5665.7  5845.7  5865.7  5885.7  5925.7  5955.7
  5985.7  6055.7  6155.7  6337.6  6427.6  6445.7  6525.7  6565.7  6667.6  6677.6
  6697.6  6707.6  6777.6  6797.6  6877.6  6907.6  6927.6  6947.6  6995.7  6997.6
  183.67  181.67  180.58     179  178.33  177.96  176.48  175.36  174.49  171.95
  171.32     171     171     171     171     171     171     171     171     171
     171     171     171     171     171     171     171     171     171     171
     171     171     171   170.5  170.71  171.21  171.32  171.27  171.17  171.55
  171.74  171.33  171.26  172.24  171.71  172.03  173.13  173.18  175.44  176.27
  176.25  177.28  179.82  181.43  183.97  185.77  185.66  186.44  186.83  186.39
  183.42  180.42  180.32  178.74  178.07   177.7  176.22  175.05  174.23  171.66
  171.06  170.58  168.48  167.72  166.55  168.75  168.75  164.79  164.81  166.88
  167.93  168.23  169.67  169.49  170.55  170.43  169.79  169.73  170.19  170.05
  169.23     169  170.17  169.69  169.17   169.2  170.01  169.28  170.06  169.43
   170.1   169.5     171  170.63  171.22  171.76  171.67  172.92  175.18   175.4
  175.99  176.33  178.74  179.43  181.99  182.76  183.71  184.69  186.57  186.14
Pier Skew, UpSta & Num, DnSta & Num=  ,4977.5, 2 ,4977.5, 2 , 0 , 0 , 0 ,,
       1       1
  164.37     170
       1       1
  164.12  169.75
Pier Skew, UpSta & Num, DnSta & Num=  ,4992.5, 2 ,4992.5, 2 , 0 , 0 , 0 ,,
       1       1
     162     170
       1       1
  161.75  169.75
Pier Skew, UpSta & Num, DnSta & Num=  ,5007.5, 2 ,5007.5, 2 , 0 , 0 , 0 ,,
       1       1
     162     170
       1       1
  161.75  169.75
Pier Skew, UpSta & Num, DnSta & Num=  ,5022.5, 2 ,5022.5, 2 , 0 , 0 , 0 ,,
       1       1
  162.82     170
       1       1
  162.57  169.75
Abutment Skew #Up #Dn= , 2 , 2
  4966.3    4970
     169  166.43
  4966.3    4970
  168.75  166.18
Abutment Skew #Up #Dn= , 2 , 2
    5030 5033.59
  164.76     169
    5030 5033.59
  164.51  168.75
BR Coef= 1 , 1 , 0 ,1.25, 0 ,,,0.8,0,2,0,
WSPro=,,,, 1 ,,,, 0 ,,,, 0 ,,,,-1 ,-1 ,-1 , 0 , 0 , 0 , 0 , 0
BR U #Sta/Elev= 152
  4093.8  183.67  4103.8  183.57  4113.8  183.48  4123.8  183.38  4133.8  183.28
  4143.8  183.19  4153.8  183.09  4173.8   182.9  4183.8   182.8  4193.8   182.7
  4403.8  180.67  4413.8  180.57  4423.8  180.47  4433.8  180.38  4443.8  180.28
  4463.8  180.09  4473.8  179.99  4483.8  179.89  4493.8   179.8  4503.8   179.7
  4523.8  179.51  4533.8  179.41  4543.8  179.31  4553.8  179.22  4563.8  179.12
  4577.1  178.99  4583.8  178.54  4587.1  178.32  4597.1  178.06  4603.8  178.02
  4613.8  177.97  4617.1  177.95  4627.1   177.4  4637.1  176.47  4673.8  175.71
  4693.8   175.3  4717.1  174.82  4793.8   174.6  4834.8  174.48  4853.8  173.26
  4874.8  171.91  4893.8   171.4  4897.2  171.31  4914.8  170.83  4924.8  168.73
  4944.8  168.41  4954.8  167.97 4966.41   166.8  4966.5  166.79    4970  166.43
  4974.8  165.95    4980     165    4985     163    5000     163    5015     163
    5030  164.76    5032     165 5033.39  165.04  5033.5  165.04  5034.8  165.08
  5044.8  165.06  5054.8  166.35  5064.8  167.13  5094.8  168.18  5164.8  168.48
  5224.8  169.92  5254.8  169.74  5284.8  170.27  5294.8   170.8  5314.8  170.79
  5365.7  170.68  5375.7  170.04  5395.7  169.98  5415.7  170.44  5455.7  170.04
  5475.7   170.3  5485.7  170.13  5495.7  169.48  5535.7  169.25  5555.7  170.42
  5560.4  170.29  5567.6  170.08  5575.7  169.85  5585.7  169.98  5587.6  169.94
  5605.7  169.55  5655.7   169.8  5665.7  169.42  5827.6  169.45  5837.6  169.45
  5845.7  169.45  5855.7   170.1  5857.6  170.13  5865.7  170.26  5875.7  169.72
  5885.7  169.53  5915.7  169.83  5925.7  170.31  5927.6  170.27  5947.6  169.85
  5955.7  169.68  5985.7  170.35  5987.6  170.34  6045.7  170.06  6055.7  169.75
  6105.7  170.25  6125.7  171.09  6147.6  171.21  6155.7  171.25  6275.7     171
  6285.7  171.21  6307.6  171.07  6337.6  170.88  6345.7  170.83  6385.7  171.36
  6427.6  171.47  6435.7  171.49  6437.6  171.59  6445.7  172.01  6477.6  171.97
  6487.6  171.96  6525.7  171.92  6527.6  171.96  6545.7  172.37  6565.7  173.17
  6577.6  173.43  6587.6  173.66  6597.6  173.88  6607.6   174.1  6617.6  174.32
  6647.6  174.99  6657.6  175.21  6667.6  175.43  6677.6  175.65  6685.7  175.83
  6687.6   175.9  6697.6  176.24  6707.6  176.58  6777.6  178.99  6787.6  179.34
  6797.6  179.68  6855.7  181.68  6877.6  182.24  6907.6  183.01  6915.7  183.22
  6917.6  183.34  6927.6  183.96  6935.7  184.47  6937.6  184.54  6947.6  184.94
  6995.7  186.82  6997.6  186.39
BR U #Mann= 4
  4093.8     .15    4980     .05    5032     .15  6045.7      10
BR U Banks=4980,5032
BR D #Sta/Elev= 152
  4093.8  183.42  4103.8  183.32  4113.8  183.23  4123.8  183.13  4133.8  183.03
  4143.8  182.94  4153.8  182.84  4173.8  182.65  4183.8  182.55  4193.8  182.45
  4403.8  180.42  4413.8  180.32  4423.8  180.22  4433.8  180.13  4443.8  180.03
  4463.8  179.84  4473.8  179.74  4483.8  179.64  4493.8  179.55  4503.8  179.45
  4523.8  179.26  4533.8  179.16  4543.8  179.06  4553.8  178.97  4563.8  178.87
  4577.1  178.74  4583.8  178.29  4587.1  178.07  4597.1  177.81  4603.8  177.77
  4613.8  177.72  4617.1   177.7  4627.1  177.15  4637.1  176.22  4673.8  175.46
  4693.8  175.05  4717.1  174.57  4793.8  174.35  4834.8  174.23  4853.8  173.01
  4874.8  171.66  4893.8  171.15  4897.2  171.06  4914.8  170.58  4924.8  168.48
  4944.8  168.16  4954.8  167.72 4966.41  166.55  4966.5  166.54    4970  166.18
  4974.8   165.7    4980  164.75    4985  162.75    5000  162.75    5015  162.75
    5030  164.51    5032  164.75 5033.39  164.79  5033.5  164.79  5034.8  164.83
  5044.8  164.81  5054.8   166.1  5064.8  166.88  5094.8  167.93  5164.8  168.23
  5224.8  169.67  5254.8  169.49  5284.8  170.02  5294.8  170.55  5314.8  170.54
  5365.7  170.43  5375.7  169.79  5395.7  169.73  5415.7  170.19  5455.7  169.79
  5475.7  170.05  5485.7  169.88  5495.7  169.23  5535.7     169  5555.7  170.17
  5560.4  170.04  5567.6  169.83  5575.7   169.6  5585.7  169.73  5587.6  169.69
  5605.7   169.3  5655.7  169.55  5665.7  169.17  5827.6   169.2  5837.6   169.2
  5845.7   169.2  5855.7  169.85  5857.6  169.88  5865.7  170.01  5875.7  169.47
  5885.7  169.28  5915.7  169.58  5925.7  170.06  5927.6  170.02  5947.6   169.6
  5955.7  169.43  5985.7   170.1  5987.6  170.09  6045.7  169.81  6055.7   169.5
  6105.7     170  6125.7  170.84  6147.6  170.96  6155.7     171  6275.7  170.75
  6285.7  170.96  6307.6  170.82  6337.6  170.63  6345.7  170.58  6385.7  171.11
  6427.6  171.22  6435.7  171.24  6437.6  171.34  6445.7  171.76  6477.6  171.72
  6487.6  171.71  6525.7  171.67  6527.6  171.71  6545.7  172.12  6565.7  172.92
  6577.6  173.18  6587.6  173.41  6597.6  173.63  6607.6  173.85  6617.6  174.07
  6647.6  174.74  6657.6  174.96  6667.6  175.18  6677.6   175.4  6685.7  175.58
  6687.6  175.65  6697.6  175.99  6707.6  176.33  6777.6  178.74  6787.6  179.09
  6797.6  179.43  6855.7  181.43  6877.6  181.99  6907.6  182.76  6915.7  182.97
  6917.6  183.09  6927.6  183.71  6935.7  184.22  6937.6  184.29  6947.6  184.69
  6995.7  186.57  6997.6  186.14
BR D #Mann= 4
  4093.8     .15    4980     .05    5032     .15  6045.7      10
BR D Banks=4980,5032
BC Design=,, 0 ,, 0 ,,,,,,
BC HTab HWMax=186.82
BC Use User HTab Curves=0
BC User HTab FreeFlow(D)= 0

Type RM Length L Ch R = 1 ,63135.5 ,77.0008,77.0008,77.0008
BEGIN DESCRIPTION:
Downstream Section of Bridge/Culvert/Weir
END DESCRIPTION:
XS GIS Cut Line= 4
  2109211.221977574972.1560128562108612.68591222575543.751804657
2108230.22203684575905.105466141 2107126.7208554576993.636495885
#Sta/Elev= 30
  4093.8   183.4  4577.1  178.72  4617.1  177.68  4637.1   176.2  4717.1  174.55
  4834.8  174.21  4874.8  171.64  4914.8  170.56  4924.8  168.46  4954.8   167.7
    4980  164.73    4985  162.73    5015  162.73    5032  164.73  5044.8  164.79
  5064.8  166.86  5094.8  167.91  5164.8  168.21  5294.8  170.53  5475.7  170.03
  5535.7  168.98  5555.7  170.15  5665.7  169.15  5987.6  170.07  6055.7  169.48
  6155.7  170.98  6345.7  170.56  6525.7  171.65  6685.7  175.56  6997.6  186.12
#Mann= 4 ,-1 , 0
  4093.8     .15       0    4980     .05       0    5032     .15       0
  5987.6      10       0
#XS Ineff= 2 , 0
       0    4956     171    5044       0     171
Permanent Ineff=
       F       F
Bank Sta=4980,5032
XS Rating Curve= 0 ,0
Exp/Cntr=0.5,0.3

Type RM Length L Ch R = 1 ,63058.5 ,0,0,0
BEGIN DESCRIPTION:
Black River 49.5
END DESCRIPTION:
XS GIS Cut Line= 4
2109245.38232314574855.6048318792109072.15056783575043.296733702
2108189.21162129575858.214991014  2107176.421359576813.274668335
#Sta/Elev= 30
  4037.1  183.31  4136.4  179.02  4240.7   178.6  4288.6  175.38  4423.3  178.92
    4507  175.56  4642.5  174.57  4679.3  172.52  4730.2  172.69  4771.5  175.69
  4799.9  173.92  4846.1  173.14    4974  166.58    4976  162.58    5024  162.58
    5026  166.58  5041.8  165.96  5043.9  167.46  5077.3  169.36  5504.3  169.33
  5591.2  171.06  5925.1  169.55  5959.9  171.05    6099  172.68  6173.4  171.09
  6448.4  171.25  6727.1  173.46  6805.7  176.75  6875.1  181.14  6886.1   183.3
#Mann= 5 , 1 , 0
  4037.1      10       0  4799.9     .15       0    4974    .043       0
    5026     .15       0  5959.9      10       0
Bank Sta=4974,5026
XS Rating Curve= 0 ,0
Exp/Cntr=0.3,0.1

Chan Stop Cuts=-1
Use User Specified Reach Order=0
Composite Channel Slope=5

--- B4544BLACKRIVER.g01 (geometry) ---

Geom Title=Duplicate Effective
Program Version=4.10

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
River Reach=Black River     ,Reach - 1

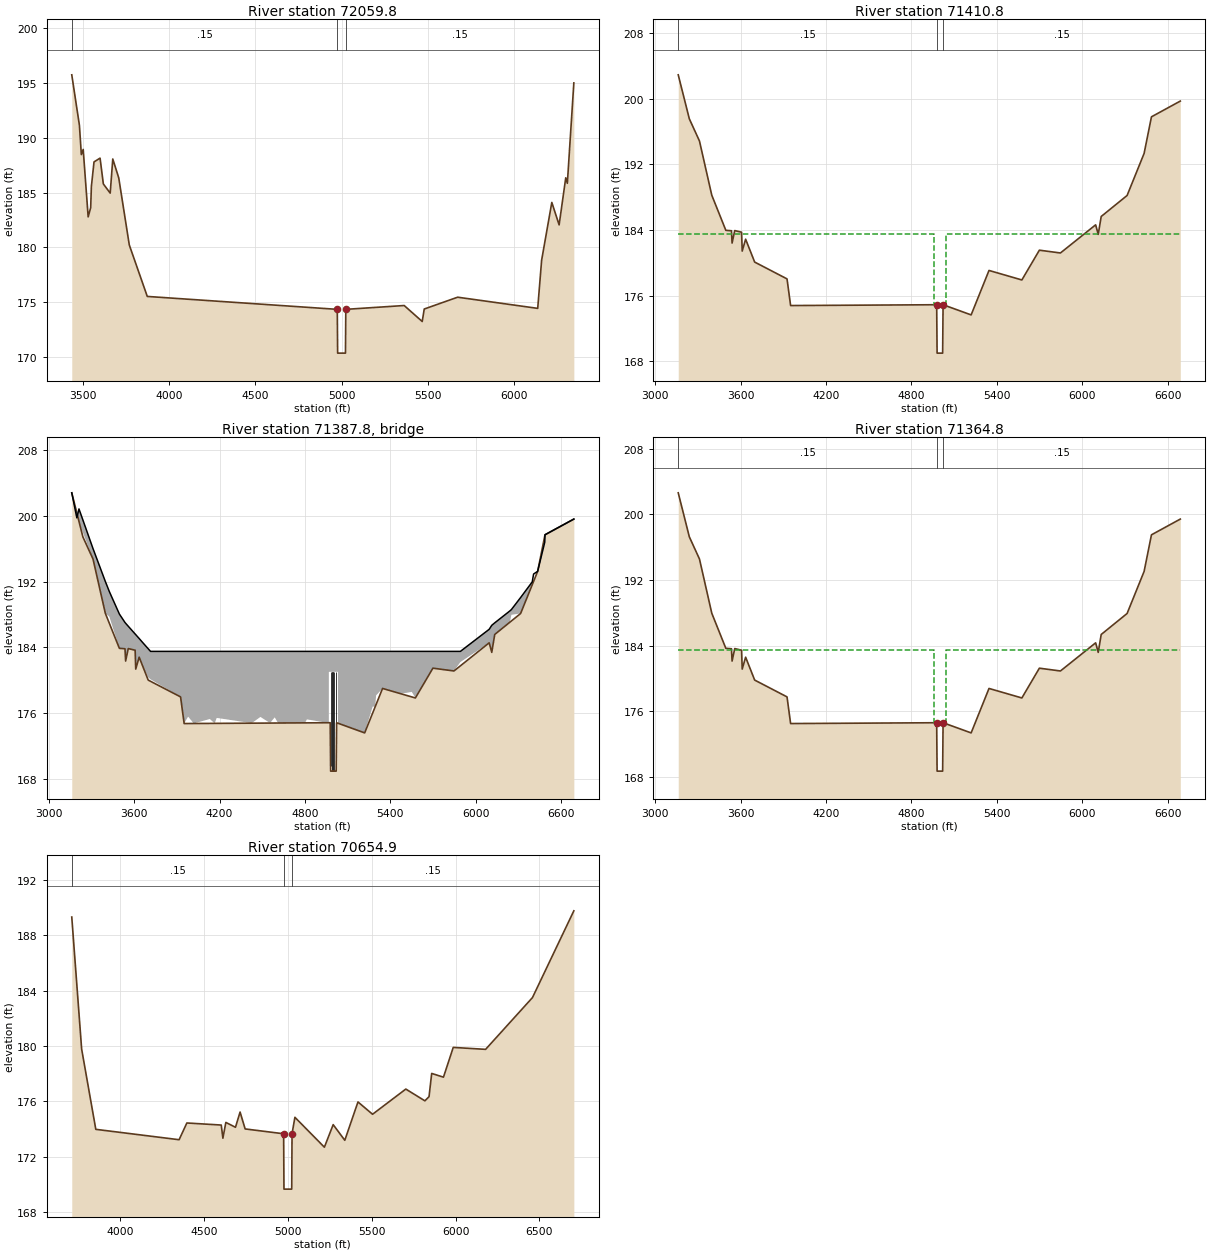
Type RM Length L Ch R = 1 ,72059.8 ,649.0066,649.0066,649.0066
BEGIN DESCRIPTION:
Black River 66.0
END DESCRIPTION:
XS GIS Cut Line= 3
2113335.52376726582162.3188685252111772.06792525582295.790220949
2110532.48536495  582806.0153909
#Sta/Elev= 30
  3436.6  195.76    3481  191.14    3492  188.47  3502.9  188.94  3531.6  182.78
  3546.2  183.62  3550.2  185.55  3565.5   187.8  3600.6  188.15  3619.6  185.79
  3659.3  184.95  3674.3  188.07  3708.9  186.34    3770  180.21  3874.2  175.51
  4975.3  174.33  4977.3  170.33  5022.7  170.33  5024.7  174.33  5363.1  174.68
  5467.5  173.22  5479.2  174.36  5672.7  175.44  6136.8  174.42  6159.5  178.82
  6218.5   184.1  6260.9  182.05  6299.3  186.35  6308.6  185.85  6346.2  195.02
#Mann= 3 , 1 , 0
  3436.6     .15       0  4975.3    .046       0  5024.7     .15       0
Bank Sta=4975.3,5024.7
XS Rating Curve= 0 ,0
Exp/Cntr=0.5,0.3

Type RM Length L Ch R = 1 ,71410.8 ,46.0005,46.0005,46.0005
BEGIN DESCRIPTION:
Upstream Section of Bridge/Culvert/Weir
END DESCRIPTION:
XS GIS Cut Line= 6
2113404.48446602581926.7564816452111559.95577599581693.954122732
2111185.26197933581621.1033845582110935.45944816581662.733806386
2110529.54533516581829.2654937992110113.21111658582255.999817765
#Sta/Elev= 30
    3161  202.91  3238.9  197.55  3310.3  194.84  3396.6  188.24  3495.7  183.95
  3535.1   183.9  3539.5   182.4  3558.2  183.92  3606.3  183.72  3610.6  181.42
  3634.7  182.87  3698.3  180.08  3925.7  178.03  3950.9  174.78  4977.5  174.88
  4980.5  168.98  5019.5  168.98  5022.5  174.88  5219.8  173.64  5345.4  179.06
  5576.3   177.9  5699.4  181.53  5847.4  181.19  6094.9  184.62  6113.1  183.46
    6134  185.64    6316   188.2  6435.6  193.33  6487.2  197.79    6690  199.71
#Mann= 3 , 1 , 0
    3161     .15       0  4977.5     .05       0  5022.5     .15       0
#XS Ineff= 2 , 0
       0    4957   183.5    5043       0   183.5
Permanent Ineff=
       F       F
Bank Sta=4977.5,5022.5
XS Rating Curve= 0 ,0
Exp/Cntr=0.5,0.3

Type RM Length L Ch R = 3 ,71387.8 ,,,
BEGIN DESCRIPTION:
Three Bridge Road TOR
Structure ID: Three Bridges Road
Approximate Survey Structure
END DESCRIPTION:
Bridge Culvert--1,0,-1,-1, 0
Deck Dist Width WeirC Skew NumUp NumDn MinLoCord MaxHiCord MaxSubmerge Is_Ogee
10,26,2.6,0, 60, 60, , , 0.95, 0, 1,1,,
    3161  3196.6  3211.6  3310.3  3396.6  3425.1  3495.7  3535.1  3539.5  3558.2
  3577.3  3606.3  3610.6  3634.7  3659.8  3714.6  3925.7  3950.9  3978.7  4018.6
  4131.3    4165  4179.7  4425.9  4487.1  4554.9  4587.6  4610.8  4798.7  4814.4
  4952.2 4967.91    4968 5031.89    5032  5219.8    5276    5294    5300  5345.4
  5464.1    5474  5551.3  5576.3  5674.8  5699.4  5847.4  5892.6  6094.9  6113.1
    6134  6240.1  6251.2    6316  6397.5  6407.1  6435.6  6485.4  6487.2    6690
  202.83  199.78  200.87  196.03  192.04  190.79  188.05  187.02  186.93  186.56
  186.19  185.62  185.54  185.07  184.57   183.5   183.5   183.5   183.5   183.5
   183.5   183.5   183.5   183.5   183.5   183.5   183.5   183.5   183.5   183.5
   183.5   183.5   183.5   183.5   183.5   183.5   183.5   183.5   183.5   183.5
   183.5   183.5   183.5   183.5   183.5   183.5   183.5   183.5  186.19  186.68
  186.98  188.43   188.6  190.07  191.97  192.93  193.26   196.8  197.72  199.63
  202.83  199.78  199.24  194.76  188.16  187.73  183.87  183.82  182.32  183.84
  182.94  183.64  181.34  182.79  180.93  180.09  177.95   174.7  175.55  174.66
  175.26  174.51  175.39  174.49  175.51  174.39  175.46  174.39  174.41  175.21
   174.1  174.53     181     181  174.18  173.56  176.77  176.35  178.13  178.98
  178.41  177.46  178.56  177.82  179.75  181.45  181.11   182.2  184.54  183.38
  185.56  186.44  187.96  188.12  191.79  192.92  193.25  196.79  197.71  199.63
    3161  3196.6  3211.6  3310.3  3396.6  3425.1  3495.7  3535.1  3539.5  3558.2
  3577.3  3606.3  3610.6  3634.7  3659.8  3714.6  3925.7  3950.9  3978.7  4018.6
  4131.3    4165  4179.7  4425.9  4487.1  4554.9  4587.6  4610.8  4798.7  4814.4
  4952.2 4967.91    4968 5031.89    5032  5219.8    5276    5294    5300  5345.4
  5464.1    5474  5551.3  5576.3  5674.8  5699.4  5847.4  5892.6  6094.9  6113.1
    6134  6240.1  6251.2    6316  6397.5  6407.1  6435.6  6485.4  6487.2    6690
  202.83  199.78  200.87  196.03  192.04  190.79  188.05  187.02  186.93  186.56
  186.19  185.62  185.54  185.07  184.57   183.5   183.5   183.5   183.5   183.5
   183.5   183.5   183.5   183.5   183.5   183.5   183.5   183.5   183.5   183.5
   183.5   183.5   183.5   183.5   183.5   183.5   183.5   183.5   183.5   183.5
   183.5   183.5   183.5   183.5   183.5   183.5   183.5   183.5  186.19  186.68
  186.98  188.43   188.6  190.07  191.97  192.93  193.26   196.8  197.72  199.63
  202.58  199.53  198.99  194.51  187.91  187.48  183.62  183.57  182.07  183.59
  182.69  183.39  181.09  182.54  180.68  179.84   177.7  174.45   175.3  174.41
  175.01  174.26  175.14  174.24  175.26  174.14  175.21  174.14  174.16  174.96
  173.85  174.28  180.75  180.75  173.93  173.31  176.52   176.1  177.88  178.73
  178.16  177.21  178.31  177.57   179.5   181.2  180.86  181.95  184.29  183.13
  185.31  186.19  187.71  187.87  191.54  192.67     193  196.54  197.46  199.38
Pier Skew, UpSta & Num, DnSta & Num=  ,4980.2, 2 ,4980.2, 2 , 0 , 0 , 0 ,,
       1       1
   167.9     182
       1       1
  167.65  181.75
Pier Skew, UpSta & Num, DnSta & Num=  ,4993.4, 2 ,4993.4, 2 , 0 , 0 , 0 ,,
       1       1
   167.9     182
       1       1
  167.65  181.75
Pier Skew, UpSta & Num, DnSta & Num=  ,5006.7, 2 ,5006.7, 2 , 0 , 0 , 0 ,,
       1       1
   167.9     182
       1       1
  167.65  181.75
Pier Skew, UpSta & Num, DnSta & Num=  ,5019.9, 2 ,5019.9, 2 , 0 , 0 , 0 ,,
       1       1
   167.9     182
       1       1
  167.65  181.75
Abutment Skew #Up #Dn= , 2 , 2
  4967.8  4973.5
     181  174.69
  4967.8  4973.5
  180.75  174.44
Abutment Skew #Up #Dn= , 2 , 2
  5026.5 5032.09
  174.33     181
  5026.5 5032.09
  174.08  180.75
BR Coef= 1 , 1 , 0 ,1.25, 0 ,,,0.8,0,2,0,
WSPro=,,,, 1 ,,,, 0 ,,,, 0 ,,,,-1 ,-1 ,-1 , 0 , 0 , 0 , 0 , 0
BR U #Sta/Elev= 30
    3161  202.83  3238.9  197.47  3310.3  194.76  3396.6  188.16  3495.7  183.87
  3535.1  183.82  3539.5  182.32  3558.2  183.84  3606.3  183.64  3610.6  181.34
  3634.7  182.79  3698.3     180  3925.7  177.95  3950.9   174.7  4977.5   174.8
  4980.5   168.9  5019.5   168.9  5022.5   174.8  5219.8  173.56  5345.4  178.98
  5576.3  177.82  5699.4  181.45  5847.4  181.11  6094.9  184.54  6113.1  183.38
    6134  185.56    6316  188.12  6435.6  193.25  6487.2  197.71    6690  199.63
BR U #Mann= 3
    3161     .15  4977.5     .05  5022.5     .15
BR U Banks=4977.5,5022.5
BR D #Sta/Elev= 30
    3161  202.58  3238.9  197.22  3310.3  194.51  3396.6  187.91  3495.7  183.62
  3535.1  183.57  3539.5  182.07  3558.2  183.59  3606.3  183.39  3610.6  181.09
  3634.7  182.54  3698.3  179.75  3925.7   177.7  3950.9  174.45  4977.5  174.55
  4980.5  168.65  5019.5  168.65  5022.5  174.55  5219.8  173.31  5345.4  178.73
  5576.3  177.57  5699.4   181.2  5847.4  180.86  6094.9  184.29  6113.1  183.13
    6134  185.31    6316  187.87  6435.6     193  6487.2  197.46    6690  199.38
BR D #Mann= 3
    3161     .15  4977.5     .05  5022.5     .15
BR D Banks=4977.5,5022.5
BC Design=,, 0 ,, 0 ,,,,,,
BC HTab HWMax=202.91
BC Use User HTab Curves=0
BC User HTab FreeFlow(D)= 0

Type RM Length L Ch R = 1 ,71364.8 ,709.9072,709.9072,709.9072
BEGIN DESCRIPTION:
Downstream Section of Bridge/Culvert/Weir
END DESCRIPTION:
XS GIS Cut Line= 6
2113412.38454607581881.4460225282111567.85585603581648.633663514
2111193.16205938 581575.782925342110943.35952821581617.413347168
2110537.44541521581783.9450345812110121.11119662582210.679358547
#Sta/Elev= 30
    3161  202.62  3238.9  197.26  3310.3  194.55  3396.6  187.95  3495.7  183.66
  3535.1  183.61  3539.5  182.11  3558.2  183.63  3606.3  183.43  3610.6  181.13
  3634.7  182.58  3698.3  179.79  3925.7  177.74  3950.9  174.49  4977.5  174.59
  4980.5  168.69  5019.5  168.69  5022.5  174.59  5219.8  173.35  5345.4  178.77
  5576.3  177.61  5699.4  181.24  5847.4   180.9  6094.9  184.33  6113.1  183.17
    6134  185.35    6316  187.91  6435.6  193.04  6487.2   197.5    6690  199.42
#Mann= 3 , 1 , 0
    3161     .15       0  4977.5     .05       0  5022.5     .15       0
#XS Ineff= 2 , 0
       0    4957   183.5    5043       0   183.5
Permanent Ineff=
       F       F
Bank Sta=4977.5,5022.5
XS Rating Curve= 0 ,0
Exp/Cntr=0.5,0.3

Type RM Length L Ch R = 1 ,70654.9 ,638.3065,638.3065,638.3065
BEGIN DESCRIPTION:
Black River 65.0
END DESCRIPTION:
XS GIS Cut Line= 3
2113148.02186736581105.6981621182111834.51855804 581005.17714357
2110233.34233383581503.702194968
#Sta/Elev= 30
  3711.4  189.31  3770.3  179.77  3854.8  173.97  4351.5  173.22  4397.8  174.43
  4602.9  174.28  4612.7  173.33  4630.3  174.47  4687.7  174.12  4715.2  175.22
  4745.4     174  4974.9  173.65  4976.9  169.65  5023.1  169.65  5025.1  173.65
  5042.2  174.84    5218  172.68  5270.4  174.31  5339.7  173.18  5418.3  175.95
  5505.3  175.06  5703.6  176.88  5817.4  176.03  5842.1  176.33  5857.9  178.01
  5928.1  177.74  5986.5  179.89  6179.5  179.75  6458.9  183.49  6705.7  189.76
#Mann= 3 , 1 , 0
  3711.4     .15       0  4974.9    .046       0  5025.1     .15       0
Bank Sta=4974.9,5025.1
XS Rating Curve= 0 ,0
Exp/Cntr=0.3,0.1

--- B4544BLACKRIVER.g03 (geometry) ---

Geom Title=Revised
Program Version=4.10

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
River Reach=Black River     ,Reach - 1

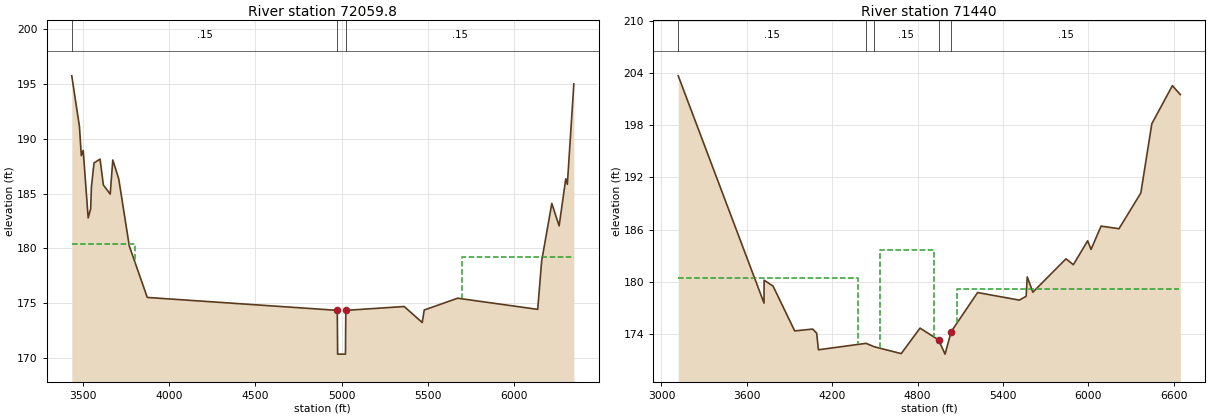
Type RM Length L Ch R = 1 ,72059.8 ,619.8,619.8,619.8
BEGIN DESCRIPTION:
Black River 66.0
END DESCRIPTION:
XS GIS Cut Line= 3
2113335.52376726582162.3188685252111772.06792525582295.790220949
2110532.48536495  582806.0153909
#Sta/Elev= 30
  3436.6  195.76    3481  191.14    3492  188.47  3502.9  188.94  3531.6  182.78
  3546.2  183.62  3550.2  185.55  3565.5   187.8  3600.6  188.15  3619.6  185.79
  3659.3  184.95  3674.3  188.07  3708.9  186.34    3770  180.21  3874.2  175.51
  4975.3  174.33  4977.3  170.33  5022.7  170.33  5024.7  174.33  5363.1  174.68
  5467.5  173.22  5479.2  174.36  5672.7  175.44  6136.8  174.42  6159.5  178.82
  6218.5   184.1  6260.9  182.05  6299.3  186.35  6308.6  185.85  6346.2  195.02
#Mann= 3 ,-1 , 0
  3436.6     .15       0  4975.3    .046       0  5024.7     .15       0
#XS Ineff= 2 , 0
          3804.5   180.4  5700.5           179.2
Permanent Ineff=
       F       F
Bank Sta=4975.3,5024.7
XS Rating Curve= 0 ,0
Exp/Cntr=0.5,0.3

Type RM Length L Ch R = 1 ,71440   ,119,119,119
XS GIS Cut Line= 6
2113403.44287169581947.9357585012111558.91670513581715.133402586
2111184.21863562581642.284466922 2110934.4166418581683.914633006
2110528.50505203581850.4461240922110112.17189521 582277.18050684
#Sta/Elev= 30
    3118  203.67    3721  177.54 3721.56  180.17 3784.62  179.49 3936.55  174.34
 4063.11  174.55 4090.97  174.08 4103.43  172.17 4437.78  172.91 4495.47  172.52
 4685.26  171.73 4817.61  174.66 4947.55  173.31 4993.49  171.67 5036.26  174.25
 5222.23  178.75 5515.67  177.88 5563.15  178.32 5571.28  180.55 5610.61  178.79
 5843.67  182.63 5895.16  181.95 5995.81   184.7 6019.59  183.71 6090.27  186.39
 6216.05  186.09 6369.59   190.2 6446.87  198.16 6591.26  202.54 6647.05  201.51
#Mann= 5 ,-1 , 0
    3118     .15       0 4437.78    .046       0 4495.47     .15       0
 4947.55    .046       0 5036.26     .15       0
#XS Ineff= 3 ,-1
    3118  4384.3   180.4  4535.7 4917.72  183.63 5079.12    6637   179.2
Permanent Ineff=
       F       F       F
Bank Sta=4947.55,5036.26
XS Rating Curve= 0 ,0
Exp/Cntr=0.5,0.3